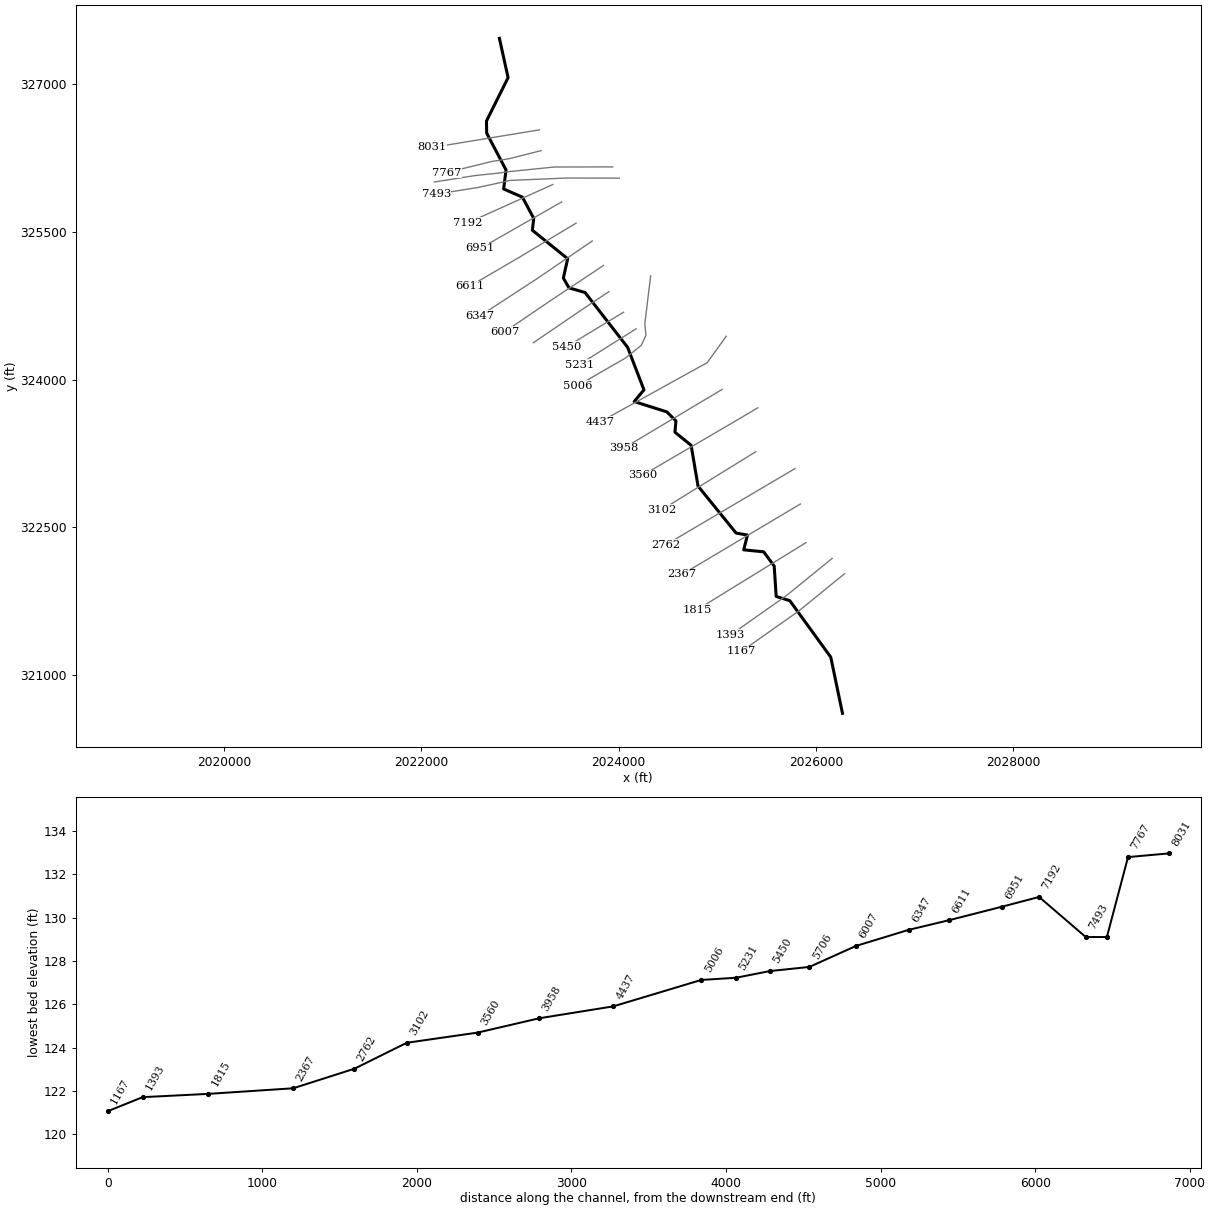
--- Jackson Swamp.prj (project) ---

Proj Title=Jackson Swamp Limited Detail Study
Current Plan=p01
Default Exp/Contr=0.3,0.1
English Units
Geom File=g11
Flow File=f01
Flow File=f02
Flow File=f04
Plan File=p01
Plan File=p02
Plan File=p04
Y Axis Title=Elevation
X Axis Title(PF)=Main Channel Distance
X Axis Title(XS)=Station
BEGIN DESCRIPTION:
Jackson Swamp
END DESCRIPTION:
DSS File=dss
DSS Export Rating Curves= 0
DSS Export Rating Curve Sorted= 0
DSS Export Volume Flow Curves= 0
DXF OffsetX= 0
DXF OffsetY= 0
DXF ScaleX= 1
DXF ScaleY= 10

--- Jackson Swamp.p01 (plan) ---

Plan Title=Multiple Profiles Effective Condition
Program Version=4.10
Short Identifier=Multi
Geom File=g11
Flow File=f01
Subcritical Flow
K Sum by GR= 0
Std Step Tol= 0.01
Critical Tol= 0.01
Num of Std Step Trials= 20
Max Error Tol= 0.3
Flow Tol Ratio= 0.001
Split Flow NTrial= 30
Split Flow Tol= 0.02
Split Flow Ratio= 0.02
Log Output Level= 0
Friction Slope Method= 1
Unsteady Friction Slope Method= 2
Unsteady Bridges Friction Slope Method= 1
Calc Critical at every XS
Parabolic Critical Depth
Global Vel Dist= 0 , 0 , 0
Global Log Level= 0
CheckData=True
Encroach Param=-1 ,0,0, 0
BEGIN DESCRIPTION:
Multiple Run
END DESCRIPTION:
Computation Interval=1HOUR
Output Interval=1HOUR
Run HTab= 0
Run UNet= 0
Run PostProcess= 0
Run WQNet= 0
UNET Theta= 1
UNET Theta Warmup= 1
UNET ZTol= 0.02
UNET ZSATol= 0.05
UNET MxIter= 20
UNET MaxInSteps= 0
UNET DtIC= 0
UNET DtMin= 0
UNET MaxCRTS= 20
UNET WFStab= 2
UNET SFStab= 1
UNET WFX= 1
UNET SFX= 1
UNET DSS MLevel= 4
UNET DZMax Abort= 100
UNET Convert EG Bridges= 0
UNET Use Existing IB Tables=-1
UNET Froude Reduction=False
UNET Froude Limit= 1
UNET Froude Power= 10
UNET Time Slicing=0,0, 5
UNET Junction Losses=0
Instantaneous Interval=1HOUR
Write IC File= 0
Write IC File at Sim End=0
Echo Input=False
Echo Parameters=False
Echo Output=False
Write Detailed= 0
WQ AD Non Conservative
WQ ULTIMATE=-1
WQ Max Comp Step=1HOUR
WQ Output Interval=15MIN
WQ Output Selected Increments= 0
WQ Output face flow=0
WQ Output face velocity=0
WQ Output face area=0
WQ Output face dispersion=0
WQ Output cell volume=0
WQ Output cell surface area=0
WQ Output cell continuity=0
WQ Output cumulative cell continuity=0
WQ Output face conc=0
WQ Output face dconc_dx=0
WQ Output face courant=0
WQ Output face peclet=0
WQ Output face adv mass=0
WQ Output face disp mass=0
WQ Output cell mass=0
WQ Output cell source sink temp=0
WQ Output cell source sink nsm=0
WQ Output MaxMinRange=-1
WQ Daily Max Min Mean=-1
WQ Daily Range=0
WQ Daily Time=0
WQ Create Restart=0
WQ Fixed Restart=0
WQ System Summary=0
WQ Use Fixed Temperature=0
Sorting and Armoring Iterations= 10
XS Update Threshold= 0.02
Hydraulics Update Threshold= 0.02
Energy Slope Method= 1
Volume Change Method= 0
XS Weighting Method= 0
Number of US Weighted Cross Sections= 1
Number of DS Weighted Cross Sections= 1
Upstream XS Weight=0.25
Main XS Weight=0.5
Downstream XS Weight=0.25
Number of DS XS's Weighted with US Boundary= 1
Upstream Boundary Weight= 1
Weight of XSs Associated with US Boundary= 0
Number of US XS's Weighted with DS Boundary= 1
Downstream Boundary Weight= 0.5
Weight of XSs Associated with DS Boundary= 0.5
Sediment Output Level= 4
Mass or Volume Output= 0
Output Increment Type= 1
Profile and TS Output Increment= 10
XS Output Flag= 0
XS Output Increment= 10
Disregard all LS=0
Disregard all Conn=0
Disregard all Breaches=0
Disregard all Pumps=0

--- Jackson Swamp.p02 (plan) ---

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Plan Title=Non-Encroachments
Program Version=4.00
Short Identifier=NonEncroachments
Geom File=g11
Flow File=f02
Encroach Param=-1 ,0,0, 2
Encroach River=Jackson Swamp
Encroach Reach=Reach-1
Encroach Node=8031
       1     443     609
Encroach Node=7767
       1     361     543
Encroach Node=7630
       1     987    1107
Encroach Node=7493
       1    1099    1219
Encroach Node=7192
       1     310     490
Encroach Node=6951
       1     300     440
Encroach Node=6611
       1     285     445
Encroach Node=6347
       1     280     450
Encroach Node=6007
       1     310     445
Encroach Node=5706
       1     166     316
Encroach Node=5450
       1     150     345
Encroach Node=5231
       1     135     340
Encroach Node=5006
       1     838    1037
Encroach Node=4437
       1     970    1200
Encroach Node=3958
       1     542     803
Encroach Node=3560
       1     651     909
Encroach Node=3102
       1     400     710
Encroach Node=2762
       1     530     930
Encroach Node=2367
       1     377     745
Encroach Node=1815
       1     316     612
Encroach Node=1393
       1     546     761
Encroach Node=1167
       1     550     765
Encroach Node=922
       1     555     753
Encroach Node=580
       1     879    1134
Encroach Node=29
       1    1050 1295.33
Non-Encroachment Run
Detailed Automatic Start=False, 10
WQ System Summary=False

--- Jackson Swamp.p04 (plan) ---

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Plan Title=Defined Future Conditions Profile
Program Version=4.00
Short Identifier=DFC
Geom File=g11
Flow File=f04
Defined Future Condtion Profiles
Detailed Automatic Start=False, 10
WQ System Summary=False

--- Jackson Swamp.f01 (steady flow) ---

Flow Title=2009 USGS Rural Regression, SIR 09-5158
Program Version=4.00
Number of Profiles= 5
Profile Names=10%,4%,2%,1%,0.2%
River Rch & RM=Jackson Swamp,Reach-1         ,8031
     267     374     468     574     823
River Rch & RM=Jackson Swamp,Reach-1         ,4437
     396     551     688     840    1200
Boundary for River Rch & Prof#=Jackson Swamp,Reach-1         , 1
Up Type= 0
Dn Type= 1
Dn Known WS=123.78
Boundary for River Rch & Prof#=Jackson Swamp,Reach-1         , 2
Up Type= 0
Dn Type= 1
Dn Known WS=124.09
Boundary for River Rch & Prof#=Jackson Swamp,Reach-1         , 3
Up Type= 0
Dn Type= 1
Dn Known WS=124.34
Boundary for River Rch & Prof#=Jackson Swamp,Reach-1         , 4
Up Type= 0
Dn Type= 1
Dn Known WS=124.58
Boundary for River Rch & Prof#=Jackson Swamp,Reach-1         , 5
Up Type= 0
Dn Type= 1
Dn Known WS=125.12
DSS Import GetInterval= 0
DSS Import GetPeak= 0
DSS Import FillOption= 0

--- Jackson Swamp.f02 (steady flow) ---

Flow Title=Non-Encroachments
Program Version=4.00
Number of Profiles= 2
Profile Names=1%,1%FW
River Rch & RM=Jackson Swamp,Reach-1         ,8031
     574     574
River Rch & RM=Jackson Swamp,Reach-1         ,4437
     840     840
Boundary for River Rch & Prof#=Jackson Swamp,Reach-1         , 1
Up Type= 0
Dn Type= 1
Dn Known WS=124.58
Boundary for River Rch & Prof#=Jackson Swamp,Reach-1         , 2
Up Type= 0
Dn Type= 1
Dn Known WS=125.14
DSS Import GetInterval= 0
DSS Import GetPeak= 0
DSS Import FillOption= 0

--- Jackson Swamp.f04 (steady flow) ---

Flow Title=DFC 01 USGS Urban Regression, FS-007-00
Program Version=4.00
Number of Profiles= 3
Profile Names=1% @ 10% imperv,1% @ 20% imperv,1% @ 35% imperv
River Rch & RM=Jackson Swamp,Reach-1         ,8031
     766     981    1200
River Rch & RM=Jackson Swamp,Reach-1         ,4437
    1150    1470    1800
Boundary for River Rch & Prof#=Jackson Swamp,Reach-1         , 1
Up Type= 0
Dn Type= 1
Dn Known WS=126.47
Boundary for River Rch & Prof#=Jackson Swamp,Reach-1         , 2
Up Type= 0
Dn Type= 1
Dn Known WS=127
Boundary for River Rch & Prof#=Jackson Swamp,Reach-1         , 3
Up Type= 0
Dn Type= 1
Dn Known WS=127.52
DSS Import GetInterval= 0
DSS Import GetPeak= 0
DSS Import FillOption= 0

--- Jackson Swamp.g11 (geometry) ---

Geom Title=NCFMP LiDAR, Est. Structures & Channel
Program Version=4.00

River Reach=Jackson Swamp   ,Reach-1
Reach XY= 30
        2022792.         327463.        2022880.         327064.
        2022661.         326624.        2022663.         326501.
        2022859.         326127.        2022835.         325934.
        2023025.         325851.        2023140.         325635.
        2023126.         325515.        2023484.         325226.
        2023440.         325030.        2023497.         324930.
        2023660.         324883.        2024091.         324327.
        2024257.         323895.        2024158.         323776.
        2024490.         323671.        2024581.         323579.
        2024571.         323465.        2024735.         323332.
        2024805.         322918.        2025191.         322441.
        2025306.         322421.        2025268.         322271.
        2025470.         322251.        2025577.         322106.
        2025597.         321798.        2025735.         321755.
        2026150.         321182.        2026269.         320611.

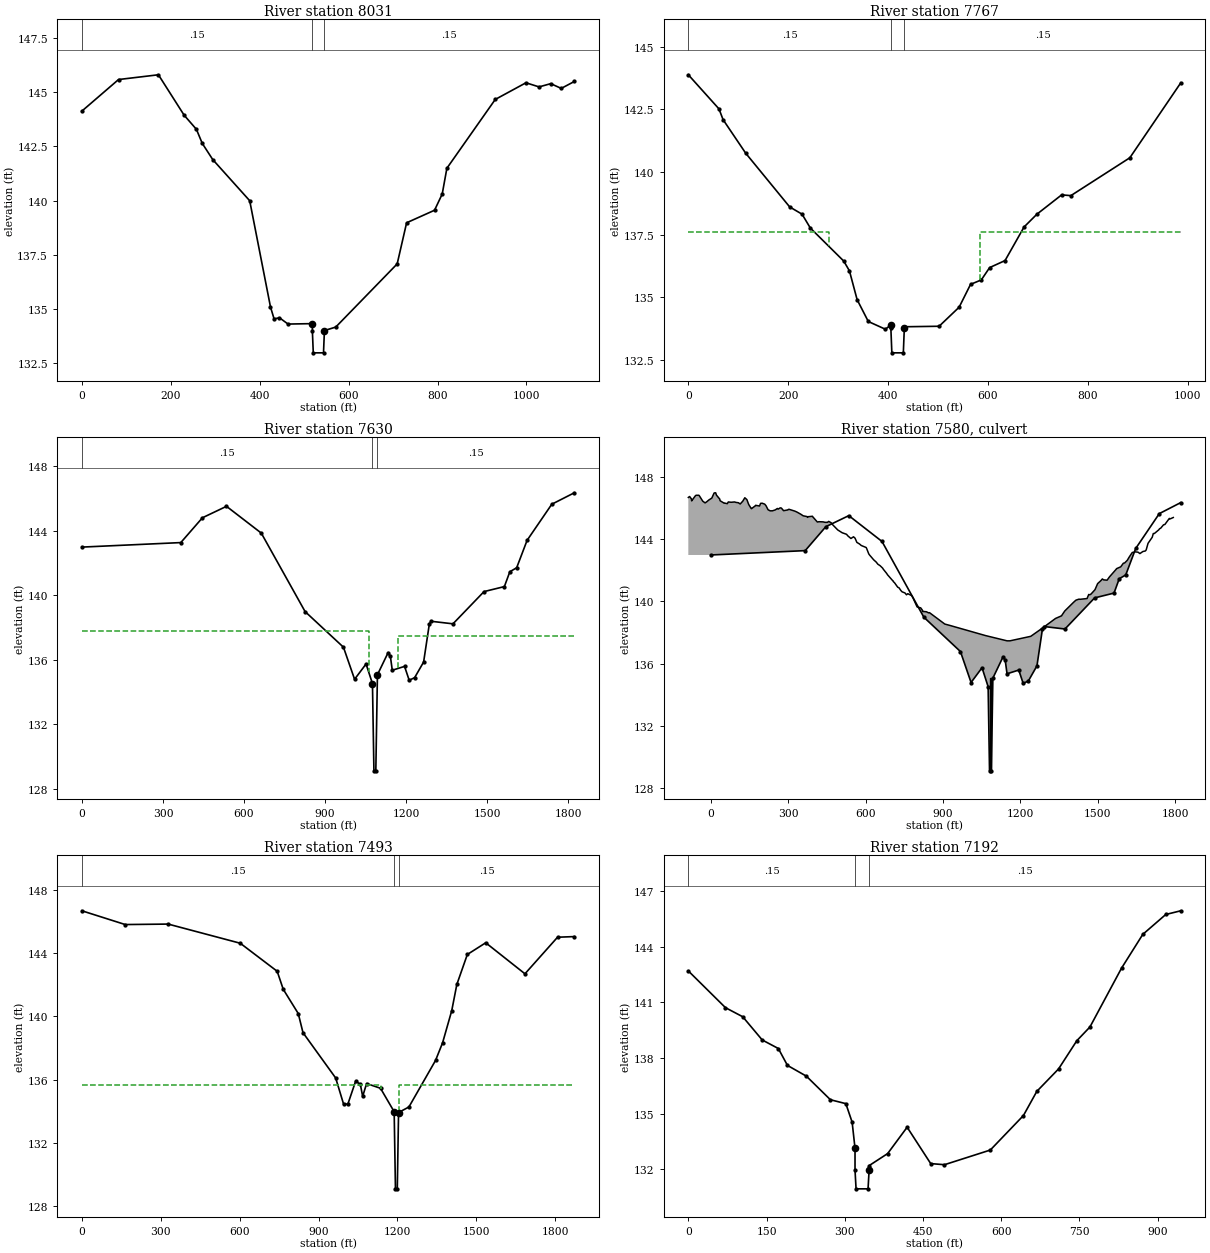
Type RM Length L Ch R = 1 ,8031    ,250.35,264,255.91
BEGIN DESCRIPTION:
8031 -
Lidar Points representing vegatation were removed at station 688.81
END DESCRIPTION:
XS GIS Cut Line= 2
        2023197.         326534.        2022108.         326355.
#Sta/Elev= 30
       0  144.13   82.49  145.59   172.2  145.81  230.12  143.94  257.67  143.29
  270.82  142.64  294.46  141.89  377.54  139.99  424.29  135.08  432.35  134.53
  444.52  134.58  463.75  134.29  518.53  134.31  518.53  133.96  520.53  132.96
  543.53  132.96  545.53  133.96  545.53  133.99  571.03  134.15  709.24  137.07
  730.45  138.97  793.29  139.55  810.56   140.3  821.03  141.49  929.82  144.67
  998.88  145.44 1028.37  145.25 1054.75   145.4 1078.24  145.18 1107.69   145.5
#Mann= 3 ,-1 , 0
       0     .15       0  518.53     .14       0  545.53     .15       0
Bank Sta=518.53,545.53
XS Rating Curve= 0 ,0
Exp/Cntr=0.3,0.1

Type RM Length L Ch R = 1 ,7767    ,139.09,136.88,117.74
BEGIN DESCRIPTION:
7767
END DESCRIPTION:
XS GIS Cut Line= 4
        2023214.         326323.        2022890.         326241.
        2022715.         326213.        2022256.         326100.
#Sta/Elev= 30
       0  143.88   61.36  142.52   69.61  142.09  114.98  140.75  202.94  138.61
  227.75  138.32  244.24  137.77  311.21  136.45  322.61  136.06  338.01  134.91
  360.38  134.04  394.74  133.73  405.53  133.91  405.53  133.79  407.53  132.79
  430.53  132.79  432.53  133.79  432.53  133.83  502.16  133.85  542.24  134.61
  565.09  135.52  586.71   135.7  603.32  136.19   634.2  136.47  672.28  137.81
  698.01  138.32  747.49  139.09  766.01  139.06  884.07  140.57  986.08  143.56
#Mann= 3 ,-1 , 0
       0     .15       0  405.53     .14       0  432.53     .15       0
#XS Ineff= 2 , 0
       0  281.59   137.6  583.93       0   137.6
Permanent Ineff=
       F       F
Bank Sta=405.53,432.53
XS Rating Curve= 0 ,0
Exp/Cntr=0.5,0.3

Type RM Length L Ch R = 1 ,7630    ,101.97,136.48,111.49
BEGIN DESCRIPTION:
7630
END DESCRIPTION:
XS GIS Cut Line= 6
        2023941.         326158.        2023351.         326157.
        2022898.         326111.        2022763.         326093.
        2022545.         326070.        2022133.         326005.
#Sta/Elev= 30
       0  142.98  366.06  143.26  446.06   144.8  535.06  145.51   663.7  143.85
  825.84  138.98  967.73  136.77 1008.94  134.78  1051.4  135.73 1075.08  134.51
 1080.49   129.1 1087.49   129.1 1093.45  135.06 1133.15  136.44 1141.39   136.2
 1148.39  135.34 1193.81  135.58 1210.94  134.72 1231.04  134.88  1264.3  135.85
 1285.42   138.2 1291.42  138.38 1372.94  138.22 1487.77  140.22 1563.07  140.53
 1583.25  141.45 1608.57   141.7 1647.12   143.4 1738.51  145.64 1821.84  146.35
#Mann= 3 ,-1 , 0
       0     .15       0 1075.08     .14       0 1093.45     .15       0
#XS Ineff= 2 , 0
       0 1061.37   137.8 1169.68       0  137.46
Permanent Ineff=
       F       F
Bank Sta=1075.08,1093.45
XS Rating Curve= 0 ,0
Exp/Cntr=0.5,0.3

Type RM Length L Ch R = 2 ,7580    ,,,
BEGIN DESCRIPTION:
Judge Rd, SR 2105, LDS_JS_01
Reinforced Concrete Box Culvert
END DESCRIPTION:
Bridge Culvert--1,0,-1,-1, 0
Deck Dist Width WeirC Skew NumUp NumDn MinLoCord MaxHiCord MaxSubmerge Is_Ogee
31.4,34.8,2.6,0, 188, 188, 137.22, , 0.98, 0, 0,0,,
 -87.005 -82.005 -75.005 -74.005 -60.005 -57.005 -57.005 -46.005 -44.005 -31.005
 -22.005 -15.005  -8.005   4.035  13.035  19.035  22.035  35.035  36.035  52.035
  53.035  64.035  68.035  73.035  79.035  92.035  98.035 107.035 114.035 124.035
 132.035 140.035 145.035 147.035 157.035 158.035 174.035 174.035 175.035 189.075
 193.075 199.075 209.075 214.075 222.075 230.075 239.075 250.075 258.075 261.075
 269.075 273.075 274.075 282.075 283.075 299.075 300.075 303.075 319.075 326.075
 334.075 349.075 358.125 373.125 375.125 376.125 394.125 395.125 413.125 416.125
 419.125 435.125 443.125 443.125 452.125 457.125 466.185 472.185 491.205 492.205
 510.205 510.205 511.205 526.245 531.245 543.245 553.295 559.295 566.295 576.295
 583.365 601.365 602.365 604.365 612.425 615.425 631.425 641.475 647.475 656.475
 666.475 668.475 682.515 684.515 704.535 706.535 707.535 712.535 724.535 729.635
 736.635 741.635 752.635 758.635 763.735 773.735 778.735 780.735 782.735 798.765
 799.765 813.765 819.845 821.845 822.845 835.845 843.915 847.915 906.995 929.065
1064.5151148.4451159.6251240.2751288.2251322.9451336.3551359.9151359.9151361.915
1371.1351372.1351381.1951398.6551405.7251414.9451417.9451427.1651431.2951458.585
1464.9051468.9051474.0051489.3051499.5051512.6551517.7551522.8551536.1951545.255
1558.5951571.7451572.7451589.0251599.2251604.3251614.5151621.5951633.7551645.925
1656.1151663.4051674.5851684.6351687.7951694.8651711.1451715.2651719.3851736.655
1739.6551743.7751754.9551760.0551774.3751777.3751780.5351792.695
  146.68  146.74  146.59  146.46  146.78  146.82  146.82  146.82  146.78  146.44
  146.33  146.41  146.51  146.64  146.97  146.98  146.83  146.57  146.47  146.31
  146.32  146.28  146.39  146.38  146.37  146.39  146.36  146.34  146.26  146.44
  146.66  146.54  146.31  146.23  145.96  145.96  146.16  146.18  146.17  146.13
   146.3  146.31  146.25  146.15  145.89  145.82  145.82  145.88  145.97  145.93
  146.01     146  145.99  145.83  145.83  145.88   145.9  145.92  145.84   145.8
  145.74   145.6   145.5  145.45   145.4  145.44  145.47  145.44   145.1  145.11
  145.12  145.11  145.08  145.08  145.08  145.14  145.06  144.93   144.6  144.59
   144.4   144.4   144.4  144.31  144.21  144.04  144.15  144.06  143.79  143.69
  143.59  143.47  143.46  143.39  143.05  142.98  142.67  142.52  142.39  142.29
  142.13  142.07  141.78  141.72  141.34  141.32  141.27  141.19  140.91  140.87
   140.7  140.61  140.54  140.42  140.49  140.41  140.37   140.3  140.26  139.68
  139.64  139.58  139.44  139.34  139.35  139.33  139.26  139.27  138.54  138.44
   137.8  137.46  137.46  137.75  138.31  138.74   138.9  139.07  139.08  139.13
  139.36  139.38  139.53  139.82  139.93  140.07  140.09  140.14  140.13  140.18
  140.44  140.42  140.47  140.75  141.14  141.34  141.44  141.38  141.36  141.57
  141.82  142.07   142.1  142.22  142.45  142.47  142.64  142.84  143.14  143.18
  143.16  143.07   143.2  143.24  143.31  143.73  144.12  144.36  144.36   144.6
  144.67   144.7  144.92  144.94  145.26  145.33   145.3  145.39
                                                                                
                                                                                
                                                                                
                                                                                
                                                                                
                                                                                
                                                                                
                                                                                
                                                                                
                                                                                
                                                                                
                                                                                
                                                                                
                                                                                
                                                                                
                                                                                
                                                                                
                                                                                
                                                                
 -87.005 -82.005 -75.005 -74.005 -60.005 -57.005 -57.005 -46.005 -44.005 -31.005
 -22.005 -15.005  -8.005   4.035  13.035  19.035  22.035  35.035  36.035  52.035
  53.035  64.035  68.035  73.035  79.035  92.035  98.035 107.035 114.035 124.035
 132.035 140.035 145.035 147.035 157.035 158.035 174.035 174.035 175.035 189.075
 193.075 199.075 209.075 214.075 222.075 230.075 239.075 250.075 258.075 261.075
 269.075 273.075 274.075 282.075 283.075 299.075 300.075 303.075 319.075 326.075
 334.075 349.075 358.125 373.125 375.125 376.125 394.125 395.125 413.125 416.125
 419.125 435.125 443.125 443.125 452.125 457.125 466.185 472.185 491.205 492.205
 510.205 510.205 511.205 526.245 531.245 543.245 553.295 559.295 566.295 576.295
 583.365 601.365 602.365 604.365 612.425 615.425 631.425 641.475 647.475 656.475
 666.475 668.475 682.515 684.515 704.535 706.535 707.535 712.535 724.535 729.635
 736.635 741.635 752.635 758.635 763.735 773.735 778.735 780.735 782.735 798.765
 799.765 813.765 819.845 821.845 822.845 835.845 843.915 847.915 906.995 929.065
1064.5151148.4451159.6251240.2751288.2251322.9451336.3551359.9151359.9151361.915
1371.1351372.1351381.1951398.6551405.7251414.9451417.9451427.1651431.2951458.585
1464.9051468.9051474.0051489.3051499.5051512.6551517.7551522.8551536.1951545.255
1558.5951571.7451572.7451589.0251599.2251604.3251614.5151621.5951633.7551645.925
1656.1151663.4051674.5851684.6351687.7951694.8651711.1451715.2651719.3851736.655
1739.6551743.7751754.9551760.0551774.3751777.3751780.5351792.695
  146.68  146.74  146.59  146.46  146.78  146.82  146.82  146.82  146.78  146.44
  146.33  146.41  146.51  146.64  146.97  146.98  146.83  146.57  146.47  146.31
  146.32  146.28  146.39  146.38  146.37  146.39  146.36  146.34  146.26  146.44
  146.66  146.54  146.31  146.23  145.96  145.96  146.16  146.18  146.17  146.13
   146.3  146.31  146.25  146.15  145.89  145.82  145.82  145.88  145.97  145.93
  146.01     146  145.99  145.83  145.83  145.88   145.9  145.92  145.84   145.8
  145.74   145.6   145.5  145.45   145.4  145.44  145.47  145.44   145.1  145.11
  145.12  145.11  145.08  145.08  145.08  145.14  145.06  144.93   144.6  144.59
   144.4   144.4   144.4  144.31  144.21  144.04  144.15  144.06  143.79  143.69
  143.59  143.47  143.46  143.39  143.05  142.98  142.67  142.52  142.39  142.29
  142.13  142.07  141.78  141.72  141.34  141.32  141.27  141.19  140.91  140.87
   140.7  140.61  140.54  140.42  140.49  140.41  140.37   140.3  140.26  139.68
  139.64  139.58  139.44  139.34  139.35  139.33  139.26  139.27  138.54  138.44
   137.8  137.46  137.46  137.75  138.31  138.74   138.9  139.07  139.08  139.13
  139.36  139.38  139.53  139.82  139.93  140.07  140.09  140.14  140.13  140.18
  140.44  140.42  140.47  140.75  141.14  141.34  141.44  141.38  141.36  141.57
  141.82  142.07   142.1  142.22  142.45  142.47  142.64  142.84  143.14  143.18
  143.16  143.07   143.2  143.24  143.31  143.73  144.12  144.36  144.36   144.6
  144.67   144.7  144.92  144.94  145.26  145.33   145.3  145.39
                                                                                
                                                                                
                                                                                
                                                                                
                                                                                
                                                                                
                                                                                
                                                                                
                                                                                
                                                                                
                                                                                
                                                                                
                                                                                
                                                                                
                                                                                
                                                                                
                                                                                
                                                                                
                                                                
BR Coef=-1 , 0 , 0 ,, 0 ,,,0.8,-1,,0,
WSPro=,,,, 1 ,,,, 0 ,,,, 0 ,,,,-1 ,-1 ,-1 , 0 , 0 , 0 , 0 , 0
Culvert=2,6,7,52.1,0.012,0.4,1,8,1,129.1,1083.995,129.1,1195.77,Culvert #1  , 0 ,8.4
Culvert Bottom n=0.012
BC Design=,, 0 ,, 0 ,,,,,,
BC Use User HTab Curves=0
BC User HTab FreeFlow(D)= 0

Type RM Length L Ch R = 1 ,7493    ,182.59,301.75,252.8
BEGIN DESCRIPTION:
7493
END DESCRIPTION:
XS GIS Cut Line= 6
        2024007.         326044.        2023478.         326045.
        2022900.         326021.        2022731.         325983.
        2022569.         325948.        2022151.         325882.
#Sta/Elev= 30
       0  146.66     165  145.79  328.05  145.82  602.23  144.61  742.61  142.84
  765.69   141.7  822.75  140.17   840.8  138.96  965.03   136.1  995.44  134.43
  1011.5  134.46 1040.54  135.88 1058.59  135.72 1067.59  134.94 1082.63  135.75
 1135.46  135.45  1187.4  133.97 1192.27   129.1 1199.27   129.1 1204.09  133.92
 1243.45  134.27 1344.73  137.21 1371.43  138.32 1406.24  140.35  1425.7  142.01
 1465.55   143.9 1535.52  144.64 1684.63  142.68 1808.53  144.99 1872.34  145.03
#Mann= 3 ,-1 , 0
       0     .15       0  1187.4     .14       0 1204.09     .15       0
#XS Ineff= 2 , 0
       0 1137.55  135.65 1204.48       0  135.65
Permanent Ineff=
       F       F
Bank Sta=1187.4,1204.09
XS Rating Curve= 0 ,0
Exp/Cntr=0.5,0.3

Type RM Length L Ch R = 1 ,7192    ,229.15,240.16,252.2
BEGIN DESCRIPTION:
7192
END DESCRIPTION:
XS GIS Cut Line= 2
        2023333.         325979.        2022474.         325591.
#Sta/Elev= 30
       0  142.69   71.28  140.71  104.42  140.22  141.76  138.97  172.68  138.51
  190.15   137.6  226.47  137.02  272.57  135.75  302.18  135.54  314.26  134.54
  319.78  133.13  319.78  131.95  321.78  130.95  344.78  130.95  346.78  131.95
  346.78   132.2  382.38  132.85  419.74  134.27  464.95  132.31  491.36  132.25
  579.28  133.04  642.85   134.9  668.48   136.2  710.21  137.41  745.24  138.93
   770.4  139.67  831.03  142.84  871.82  144.66  915.85  145.73  944.68  145.93
#Mann= 3 ,-1 , 0
       0     .15       0  319.78     .14       0  346.78     .15       0
Bank Sta=319.78,346.78
XS Rating Curve= 0 ,0
Exp/Cntr=0.3,0.1

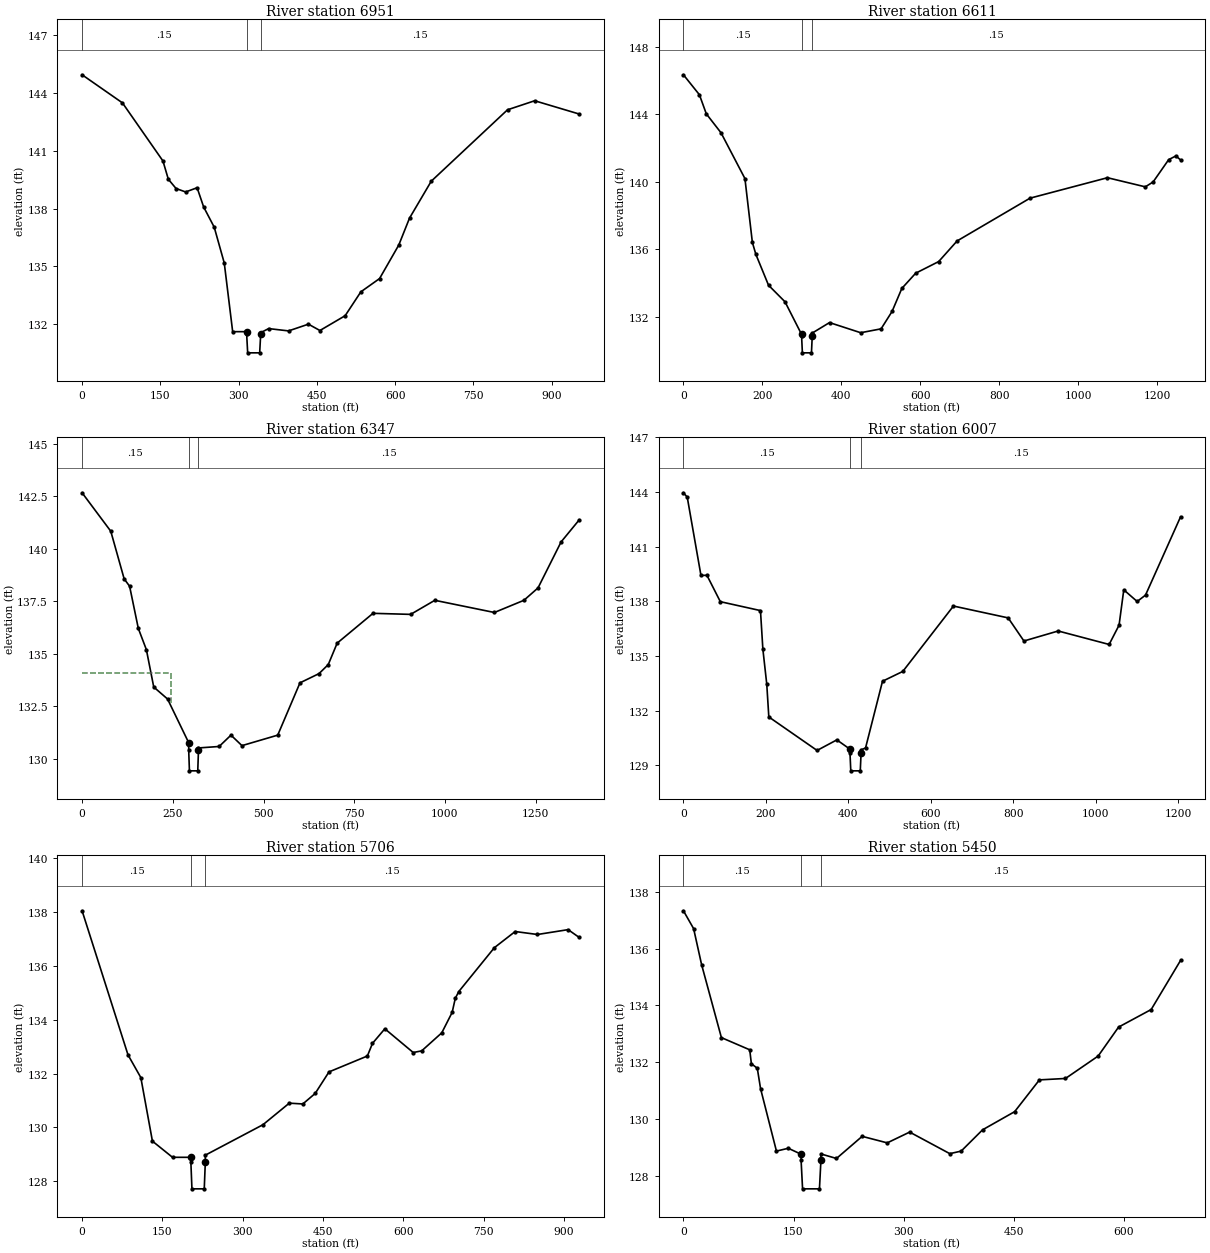
Type RM Length L Ch R = 1 ,6951    ,270.95,340.87,272.62
BEGIN DESCRIPTION:
6951
END DESCRIPTION:
XS GIS Cut Line= 2
        2023422.         325802.        2022597.         325330.
#Sta/Elev= 30
       0  144.95   77.33  143.49  154.96  140.47  165.27  139.52  180.06  139.04
  198.43  138.86  220.41  139.08  232.94  138.08  253.19  137.03  272.43  135.17
  288.55   131.6  315.29   131.6  315.29   131.5  317.29   130.5  340.29   130.5
  342.29   131.5  342.29  131.55  357.54  131.76  395.62  131.64  433.72  131.99
   455.7  131.66  504.09  132.43  534.16  133.67  570.02  134.36   606.8   136.1
   627.4   137.5  669.09  139.42  815.17  143.13  867.23   143.6  952.58  142.91
#Mann= 3 ,-1 , 0
       0     .15       0  315.29     .14       0  342.29     .15       0
Bank Sta=315.29,342.29
XS Rating Curve= 0 ,0
Exp/Cntr=0.3,0.1

Type RM Length L Ch R = 1 ,6611    ,257.91,263.25,276.38
BEGIN DESCRIPTION:
6611
END DESCRIPTION:
XS GIS Cut Line= 3
        2023569.         325587.        2022998.         325243.
        2022488.         324945.
#Sta/Elev= 30
       0  146.33   40.47  145.15   57.97  144.02   95.21   142.9  155.84  140.19
  174.71  136.41  183.65   135.7  215.63  133.88  257.38   132.9  299.41  130.97
  299.41  130.88  301.41  129.88  324.41  129.88  326.41  130.88  326.41  131.05
  370.18  131.67   449.2  131.07  500.84   131.3   528.7  132.33   553.4  133.69
  588.41  134.59  646.81  135.28  693.48   136.5  878.23  139.03 1074.41  140.24
 1170.41   139.7 1190.15  139.99  1229.6  141.31 1247.96  141.53 1259.67  141.29
#Mann= 3 ,-1 , 0
       0     .15       0  299.41     .14       0  326.41     .15       0
Bank Sta=299.41,326.41
XS Rating Curve= 0 ,0
Exp/Cntr=0.3,0.1

Type RM Length L Ch R = 1 ,6347    ,266.1,340.02,264.8
BEGIN DESCRIPTION:
6347
END DESCRIPTION:
XS GIS Cut Line= 3
        2023733.         325406.        2023182.         325029.
        2022597.         324647.
#Sta/Elev= 30
       0  142.67   79.07  140.84  115.97  138.57  130.97  138.22     155  136.21
  177.21   135.2   197.5  133.42  235.57  132.85  293.83  130.77  293.83  130.43
  295.83  129.43  318.83  129.43  320.83  130.43  320.83  130.52  377.73  130.59
  410.36  131.13  440.63  130.63  539.22  131.13  600.54  133.62  653.07  134.06
  678.51  134.49     703  135.51  801.81  136.93  905.56  136.88  972.18  137.55
 1136.36  136.97 1217.71  137.55 1256.61  138.14  1320.2  140.33 1370.16  141.38
#Mann= 3 ,-1 , 0
       0     .15       0  293.83     .14       0  320.83     .15       0
#XS Ineff= 2 , 0
          244.04   134.1
Permanent Ineff=
       F       F
Bank Sta=293.83,320.83
XS Rating Curve= 0 ,0
Exp/Cntr=0.3,0.1

Type RM Length L Ch R = 1 ,6007    ,252.07,301.46,260.55
BEGIN DESCRIPTION:
6007
END DESCRIPTION:
XS GIS Cut Line= 3
        2023847.         325157.        2023330.         324814.
        2022849.         324487.
#Sta/Elev= 30
       0  143.96    9.25  143.72   42.53  139.42   56.97  139.43   89.48  137.98
  186.84  137.49  192.67  135.37   202.1  133.45   207.1  131.65  324.12  129.81
  372.07  130.39  403.89  129.88  403.89  129.69  405.89  128.69  428.89  128.69
  430.89  129.69  430.89  129.84  441.71  129.95   482.8  133.61  532.05  134.15
  654.83  137.74  787.51  137.09  825.78  135.82  908.87  136.37 1032.43  135.63
 1056.52  136.69 1067.94  138.63  1100.4  137.99 1120.66  138.34 1205.65  142.64
#Mann= 3 ,-1 , 0
       0     .15       0  403.89     .14       0  430.89     .15       0
Bank Sta=403.89,430.89
XS Rating Curve= 0 ,0
Exp/Cntr=0.3,0.1

Type RM Length L Ch R = 1 ,5706    ,253.81,255.39,239.3
BEGIN DESCRIPTION:
5706
END DESCRIPTION:
XS GIS Cut Line= 3
        2023902.         324892.        2023590.         324683.
        2023136.         324373.
#Sta/Elev= 30
       0  138.04   85.78  132.69  109.67  131.85  131.33  129.49  168.84  128.89
   203.1  128.89   203.1  128.72   205.1  127.72   228.1  127.72   230.1  128.72
   230.1  128.97  337.72   130.1  386.86   130.9  412.13  130.87  435.21  131.26
  461.02  132.06  532.66  132.65  542.23  133.12  565.29  133.66  618.24  132.78
  634.05  132.84  671.57  133.51  690.99  134.27  696.82  134.79  703.26  135.04
  769.77  136.67  808.64  137.27   850.3  137.16  907.48  137.34  928.21  137.05
#Mann= 3 ,-1 , 0
       0     .15       0   203.1     .14       0   230.1     .15       0
Bank Sta=203.1,230.1
XS Rating Curve= 0 ,0
Exp/Cntr=0.3,0.1

Type RM Length L Ch R = 1 ,5450    ,213.36,219.93,220.11
BEGIN DESCRIPTION:
5450
END DESCRIPTION:
XS GIS Cut Line= 2
        2024050.         324683.        2023472.         324332.
#Sta/Elev= 30
       0  137.33    13.9   136.7   24.77  135.43   51.74  132.86   90.35  132.43
   92.59  131.94  100.65  131.78  105.12  131.06  126.75  128.86   142.9  128.96
  160.35  128.75  160.35  128.53  162.35  127.53  185.35  127.53  187.35  128.53
  187.35  128.76  208.55   128.6  243.55  129.38  277.72  129.15  308.27  129.53
  362.98  128.77  378.47  128.86  407.63  129.61  451.33  130.25  485.09  131.37
  520.61  131.42  565.12  132.21  592.92  133.23  637.38  133.85  677.41  135.58
#Mann= 3 ,-1 , 0
       0     .15       0  160.35     .14       0  187.35     .15       0
Bank Sta=160.35,187.35
XS Rating Curve= 0 ,0
Exp/Cntr=0.3,0.1

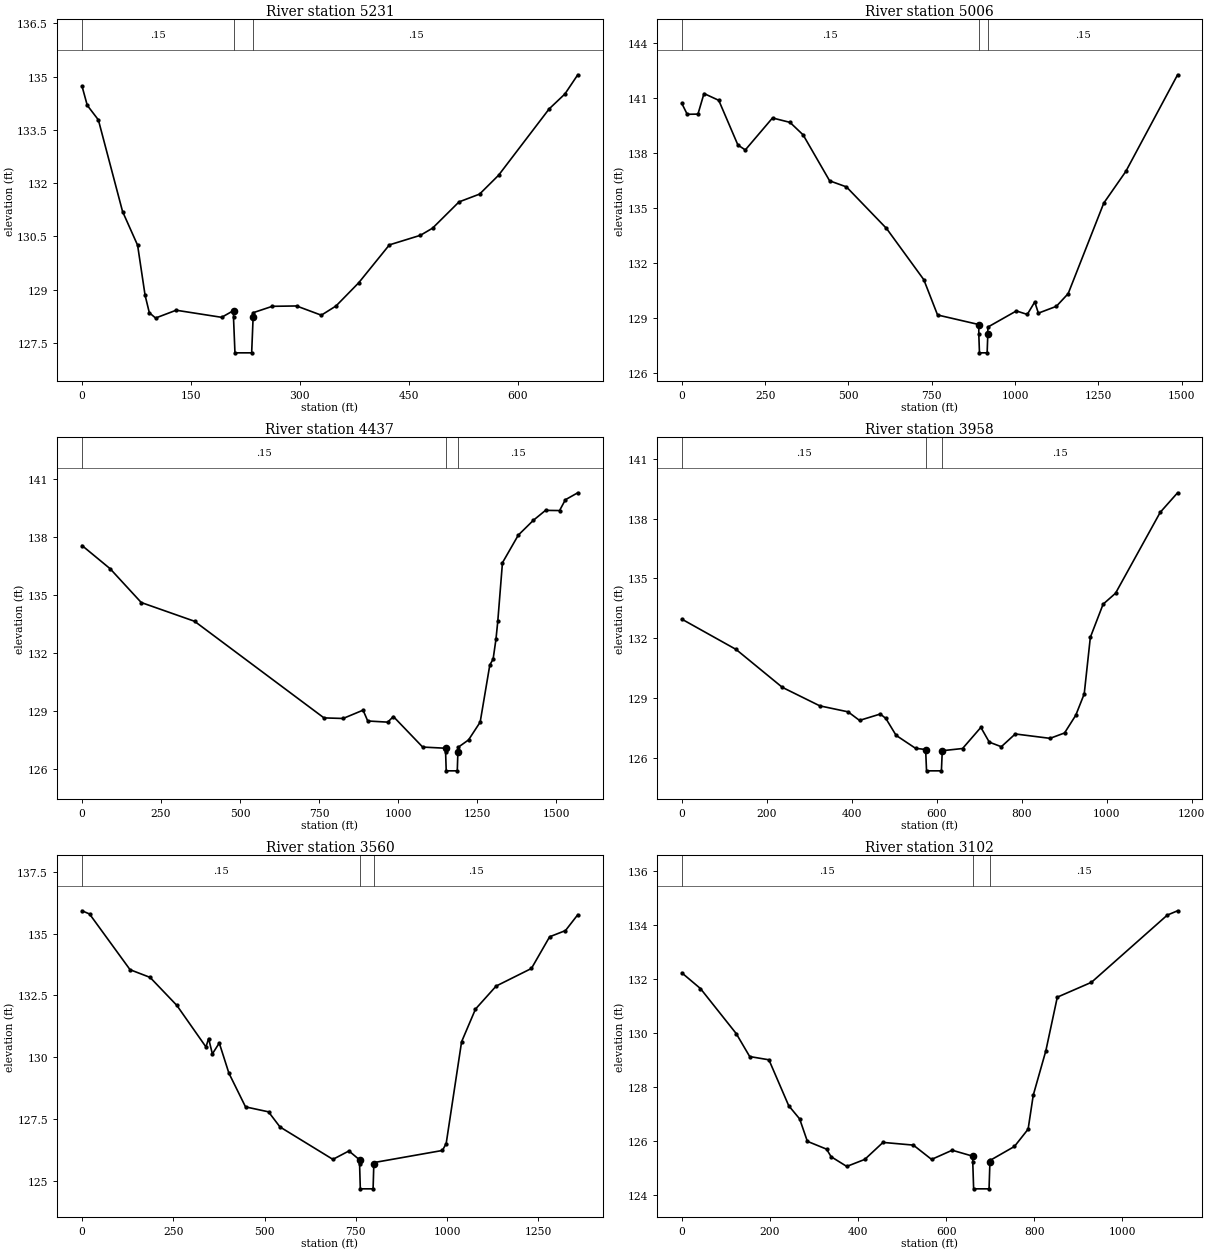
Type RM Length L Ch R = 1 ,5231    ,177.65,224.09,194.45
BEGIN DESCRIPTION:
5231
END DESCRIPTION:
XS GIS Cut Line= 2
        2024178.         324515.        2023602.         324152.
#Sta/Elev= 30
       0  134.73    7.21  134.19   22.51  133.78   55.81   131.2   76.53  130.25
   86.83  128.84   92.66  128.35  101.26   128.2   129.6  128.42  192.22  128.22
  208.55  128.41  208.55  128.22  210.55  127.22  233.55  127.22  235.55  128.22
  235.55  128.35  261.96  128.53  295.31  128.54  329.45  128.28  349.69  128.54
   380.8  129.19  423.14  130.26  465.89  130.53  482.54  130.73     519  131.47
  547.34  131.69  573.43  132.22  643.13  134.09  664.81  134.51  682.49  135.05
#Mann= 3 ,-1 , 0
       0     .15       0  208.55     .14       0  235.55     .15       0
Bank Sta=208.55,235.55
XS Rating Curve= 0 ,0
Exp/Cntr=0.3,0.1

Type RM Length L Ch R = 1 ,5006    ,483.01,569.25,433.85
BEGIN DESCRIPTION:
5006
END DESCRIPTION:
XS GIS Cut Line= 6
        2024325.         325053.        2024266.         324567.
        2024277.         324449.        2024230.         324347.
        2024070.         324218.        2023586.         323939.
#Sta/Elev= 30
       0  140.69   16.12   140.1   48.39  140.11   66.51  141.23   110.8  140.86
  168.23  138.43  190.43  138.16   272.1   139.9   324.6  139.66  363.97  138.98
  443.54  136.48  493.93  136.15  614.14  133.89  726.17   131.1  767.43  129.18
   891.2  128.66   891.2  128.12   893.2  127.12   916.2  127.12   918.2  128.12
   918.2  128.52 1003.91   129.4 1036.66  129.21 1059.14  129.89 1069.98  129.28
 1123.84  129.65 1159.35  130.34 1266.28  135.27 1332.32  136.99 1487.74  142.25
#Mann= 3 ,-1 , 0
       0     .15       0   891.2     .14       0   918.2     .15       0
Bank Sta=891.2,918.2
XS Rating Curve= 0 ,0
Exp/Cntr=0.3,0.1

Type RM Length L Ch R = 1 ,4437    ,328.28,479.18,344.93
BEGIN DESCRIPTION:
4437
END DESCRIPTION:
XS GIS Cut Line= 3
        2025091.         324439.        2024898.         324171.
        2023819.         323573.
#Sta/Elev= 30
       0  137.56   88.96  136.36  187.44  134.61  356.04  133.64  765.54  128.64
  825.99  128.61   889.2  129.04  903.97  128.48  967.23  128.42  985.12  128.71
 1077.81  127.13 1150.26  127.07 1150.26   126.9 1152.26   125.9 1187.26   125.9
 1189.26   126.9 1189.26  127.11 1222.88   127.5 1259.67  128.42 1290.21  131.38
 1300.64  131.68 1309.58   132.7 1315.43  133.64 1330.19  136.67 1380.38   138.1
 1428.29  138.87 1466.49  139.38 1510.86  139.37 1529.28  139.93 1568.47  140.29
#Mann= 3 ,-1 , 0
       0     .15       0 1150.26     .14       0 1189.26     .15       0
Bank Sta=1150.26,1189.26
XS Rating Curve= 0 ,0
Exp/Cntr=0.3,0.1

Type RM Length L Ch R = 1 ,3958    ,340.8,397.65,350.18
BEGIN DESCRIPTION:
3958
END DESCRIPTION:
XS GIS Cut Line= 2
        2025049.         323899.        2024050.         323302.
#Sta/Elev= 30
       0  132.96  127.68  131.44  236.41  129.54  324.77  128.61  391.22  128.31
  418.18  127.88  467.06   128.2  480.09  127.98  504.28  127.13  550.08  126.48
  573.92  126.42  573.92  126.35  575.92  125.35  610.92  125.35  612.92  126.35
  612.92  126.36  660.68  126.47   703.8  127.53  723.57  126.79   751.9  126.56
  784.74   127.2  866.59  126.98  900.74  127.25  927.16  128.14  947.03  129.21
  961.45  132.05  991.47  133.71 1020.73  134.26 1125.91  138.32 1166.77   139.3
#Mann= 3 ,-1 , 0
       0     .15       0  573.92     .14       0  612.92     .15       0
Bank Sta=573.92,612.92
XS Rating Curve= 0 ,0
Exp/Cntr=0.3,0.1

Type RM Length L Ch R = 1 ,3560    ,389.25,458.42,391.31
BEGIN DESCRIPTION:
3560
END DESCRIPTION:
XS GIS Cut Line= 3
        2025411.         323713.        2025144.         323555.
        2024242.         323027.
#Sta/Elev= 30
       0  135.92   20.61  135.79  131.58  133.54  186.35  133.23  259.62   132.1
  339.47  130.42  346.68  130.76  356.97  130.14  375.87  130.58   402.3  129.36
  447.78     128  510.71   127.8   542.1  127.19  687.04  125.88  730.98  126.22
  760.12  125.86  760.12  125.69  762.12  124.69  797.12  124.69  799.12  125.69
  799.12  125.75  986.99  126.24  997.29  126.52 1039.48  130.63 1077.56  131.95
 1134.15  132.88 1230.73  133.59 1280.59  134.87  1323.9  135.12 1357.63  135.76
#Mann= 3 ,-1 , 0
       0     .15       0  760.12     .14       0  799.12     .15       0
Bank Sta=760.12,799.12
XS Rating Curve= 0 ,0
Exp/Cntr=0.3,0.1

Type RM Length L Ch R = 1 ,3102    ,351.89,339.71,335.39
BEGIN DESCRIPTION:
3102
END DESCRIPTION:
XS GIS Cut Line= 2
        2025390.         323267.        2024435.         322676.
#Sta/Elev= 30
       0  132.22   42.22  131.64  123.53  129.97   154.1  129.12  197.72     129
  242.66   127.3  267.51  126.81  285.01  125.98  328.63  125.69  338.93  125.41
  374.48  125.05  415.33  125.31  456.79  125.94  525.67  125.84  567.12  125.31
  613.84  125.65  660.57  125.43  660.57  125.22  662.57  124.22  697.57  124.22
  699.57  125.22  699.57  125.27  755.22  125.79  786.28  126.43  797.95  127.69
  826.48  129.33  852.56  131.32  930.07  131.87 1102.29  134.36 1125.67  134.52
#Mann= 3 ,-1 , 0
       0     .15       0  660.57     .14       0  699.57     .15       0
Bank Sta=660.57,699.57
XS Rating Curve= 0 ,0
Exp/Cntr=0.3,0.1

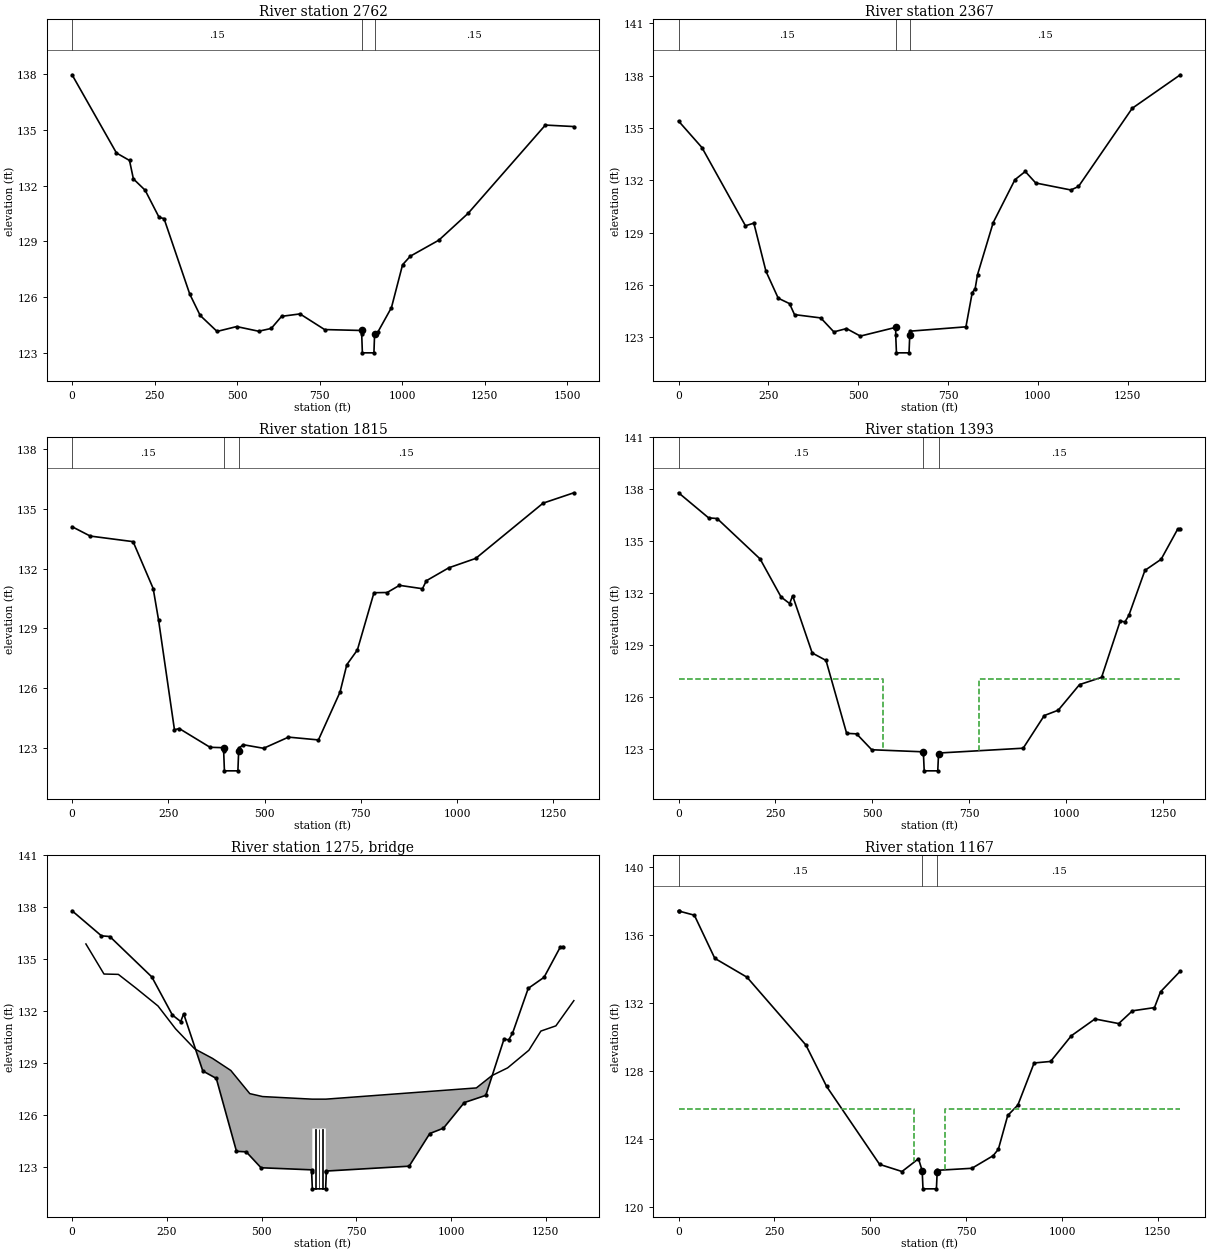
Type RM Length L Ch R = 1 ,2762    ,336.76,394.87,341.3
BEGIN DESCRIPTION:
2762
END DESCRIPTION:
XS GIS Cut Line= 2
        2025788.         323096.        2024483.         322325.
#Sta/Elev= 30
       0  137.95  134.47  133.75  173.94  133.35  185.71  132.36  221.33  131.75
  263.68  130.29  278.46  130.23  356.49  126.17  387.89  125.03  439.05  124.17
   498.5  124.43  565.01  124.18  603.18  124.33  634.58  124.98  690.31  125.11
  764.81  124.27  877.18  124.22  877.18  124.02  879.18  123.02  914.18  123.02
  916.18  124.02  916.18  124.11  925.58  124.12  967.26  125.45 1000.93  127.75
 1024.41  128.21 1110.82  129.07 1199.39  130.51  1433.4  135.25 1519.67  135.17
#Mann= 3 ,-1 , 0
       0     .15       0  877.18     .14       0  916.18     .15       0
Bank Sta=877.18,916.18
XS Rating Curve= 0 ,0
Exp/Cntr=0.3,0.1

Type RM Length L Ch R = 1 ,2367    ,378.45,552.45,378.22
BEGIN DESCRIPTION:
2367
END DESCRIPTION:
XS GIS Cut Line= 2
        2025842.         322736.        2024644.         322022.
#Sta/Elev= 30
       0   135.4   65.14  133.88  186.27   129.4  209.64  129.55  243.36  126.79
  277.49  125.25  308.89  124.94  322.79  124.31  395.86  124.12   432.3  123.32
  467.45  123.51  506.08  123.08  604.51  123.58  604.51  123.12  606.51  122.12
  641.51  122.12  643.51  123.12  643.51  123.36  799.91  123.61  817.41  125.57
  825.47  125.79  832.18   126.6  875.75  129.58  936.33  132.04  964.99  132.51
  994.21  131.85 1092.03  131.45 1113.17  131.65 1262.69  136.13 1396.61  138.05
#Mann= 3 ,-1 , 0
       0     .15       0  604.51     .14       0  643.51     .15       0
Bank Sta=604.51,643.51
XS Rating Curve= 0 ,0
Exp/Cntr=0.3,0.1

Type RM Length L Ch R = 1 ,1815    ,345.86,421.63,367.21
BEGIN DESCRIPTION:
1815
END DESCRIPTION:
XS GIS Cut Line= 2
        2025899.         322344.        2024792.         321661.
#Sta/Elev= 30
       0   134.1   47.17  133.63  158.48  133.35  210.65     131  224.54  129.43
  265.88  123.92  278.41  123.98  358.39  123.04  393.65  123.02  393.65  122.86
  395.65  121.86  430.65  121.86  432.65  122.86  432.65  122.99  444.35  123.17
  497.38  122.99  562.05  123.55   639.8  123.41  695.91  125.81  713.47  127.18
  740.94  127.92  784.03  130.79  818.27   130.8  850.26  131.16  909.98  130.99
  919.99  131.39  978.47  132.04 1048.25  132.51 1223.21  135.28 1303.12   135.8
#Mann= 3 ,-1 , 0
       0     .15       0  393.65     .14       0  432.65     .15       0
Bank Sta=393.65,432.65
XS Rating Curve= 0 ,0
Exp/Cntr=0.5,0.3

Type RM Length L Ch R = 1 ,1393    ,203.85,226.41,200.68
BEGIN DESCRIPTION:
1393
END DESCRIPTION:
XS GIS Cut Line= 4
        2026164.         322184.        2025726.         321827.
        2025662.         321779.        2025133.         321406.
#Sta/Elev= 30
       0   137.8    77.5  136.35   99.59  136.31  210.48  133.97  264.57  131.77
  286.62  131.39  294.43  131.84  344.87  128.53  380.49   128.1  433.75  123.88
  459.43  123.85   498.5  122.93   631.9  122.81   631.9  122.71   633.9  121.71
   668.9  121.71   670.9  122.71   670.9  122.74  889.28  123.02  943.75  124.91
  979.81  125.22 1034.68   126.7 1091.59  127.12 1139.62  130.38 1151.83  130.33
 1161.83   130.7 1203.45  133.31 1245.16  133.95 1287.77  135.69 1294.76  135.73
#Mann= 3 ,-1 , 0
       0     .15       0   631.9     .14       0   670.9     .15       0
#XS Ineff= 2 , 0
       0  526.85     127     775       0  127.05
Permanent Ineff=
       F       F
Bank Sta=631.9,670.9
XS Rating Curve= 0 ,0
Exp/Cntr=0.5,0.3

Type RM Length L Ch R = 3 ,1275    ,,,
BEGIN DESCRIPTION:
NC State Highway 41, LDS_JS_02
Bridge with 3 Piers
END DESCRIPTION:
Bridge Culvert--1,0,-1,-1, 0
Deck Dist Width WeirC Skew NumUp NumDn MinLoCord MaxHiCord MaxSubmerge Is_Ogee
111.85,20.3,2.6,0, 22, 21, 126.9, , 0.98, 0, 0,0,,
   36.52   84.18  122.05  167.71  226.76  273.03  323.51  370.37   418.8  468.84
  502.53   633.8   633.8   669.4   669.4  1066.6 1107.44 1149.11 1205.15 1236.84
 1276.33 1323.82
  135.88  134.14  134.12  133.34  132.29  130.97  129.81  129.26  128.56  127.22
  127.05   126.9   126.9   126.9   126.9  127.55  128.26  128.71  129.73  130.84
  131.14   132.6
     100     100     100     100     100     100     100     100     100     100
     100     100   125.2   125.2     100     100     100     100     100     100
     100     100
   39.99   87.65  125.52  171.18  240.23  302.77  373.84  407.27  472.31   512.4
  637.27  637.27  672.87  672.87 1081.48 1112.33 1169.78 1213.62 1251.71 1282.63
  1340.1
  135.88  134.14  134.12  133.34  131.63  130.39  129.27  128.69  127.22  126.96
   126.9   126.9   126.9   126.9  127.84  128.28  129.01  129.85  130.81  131.21
   132.9
     100     100     100     100     100     100     100     100     100     100
     100   125.2   125.2     100     100     100     100     100     100     100
     100
Pier Skew, UpSta & Num, DnSta & Num=  ,642.7, 2 ,646.2, 2 , 0 , 0 , 0 ,,
       1       1
     120   125.3
       1       1
     120   125.3
Pier Skew, UpSta & Num, DnSta & Num=  ,651.6, 2 ,655.1, 2 , 0 , 0 , 0 ,,
       1       1
     120   125.3
       1       1
     120   125.3
Pier Skew, UpSta & Num, DnSta & Num=  ,660.5, 2 ,664, 2 , 0 , 0 , 0 ,,
       1       1
     120   125.3
       1       1
     120   125.3
BR Coef=-1 , 1 , 0 ,, 0 ,,,0.8,0,2,0,
WSPro=,,,, 1 ,,,, 0 ,,,, 0 ,,,,-1 ,-1 ,-1 , 0 , 0 , 0 , 0 , 0
BC Design=,, 0 ,, 0 ,,,,,,
BC Use User HTab Curves=0
BC User HTab FreeFlow(D)= 0

Type RM Length L Ch R = 1 ,1167    ,239.65,245.17,242.36
BEGIN DESCRIPTION:
1167
END DESCRIPTION:
XS GIS Cut Line= 4
        2026290.         322029.        2025849.         321669.
        2025779.         321617.        2025248.         321242.
#Sta/Elev= 30
       0  137.43       0  137.42   41.26  137.17   94.56  134.63  178.48  133.52
  332.07  129.53  386.14  127.09  524.42   122.5  582.78  122.08  625.83  122.83
  635.57  122.12  635.57  122.06  637.57  121.06  672.57  121.06  674.57  122.06
  674.57  122.15  765.15  122.27   820.5  123.01  834.11  123.39  858.55  125.38
  884.96  125.99   927.4  128.47  970.43  128.56 1024.35  130.07 1086.04  131.06
 1147.97  130.79 1183.79  131.54 1241.23  131.73 1257.04  132.66  1308.7  133.88
#Mann= 3 ,-1 , 0
       0     .15       0  635.57     .14       0  674.57     .15       0
#XS Ineff= 2 , 0
       0  615.27  125.75  694.87       0  125.75
Permanent Ineff=
       F       F
Bank Sta=635.57,674.57
XS Rating Curve= 0 ,0
Exp/Cntr=0.5,0.3