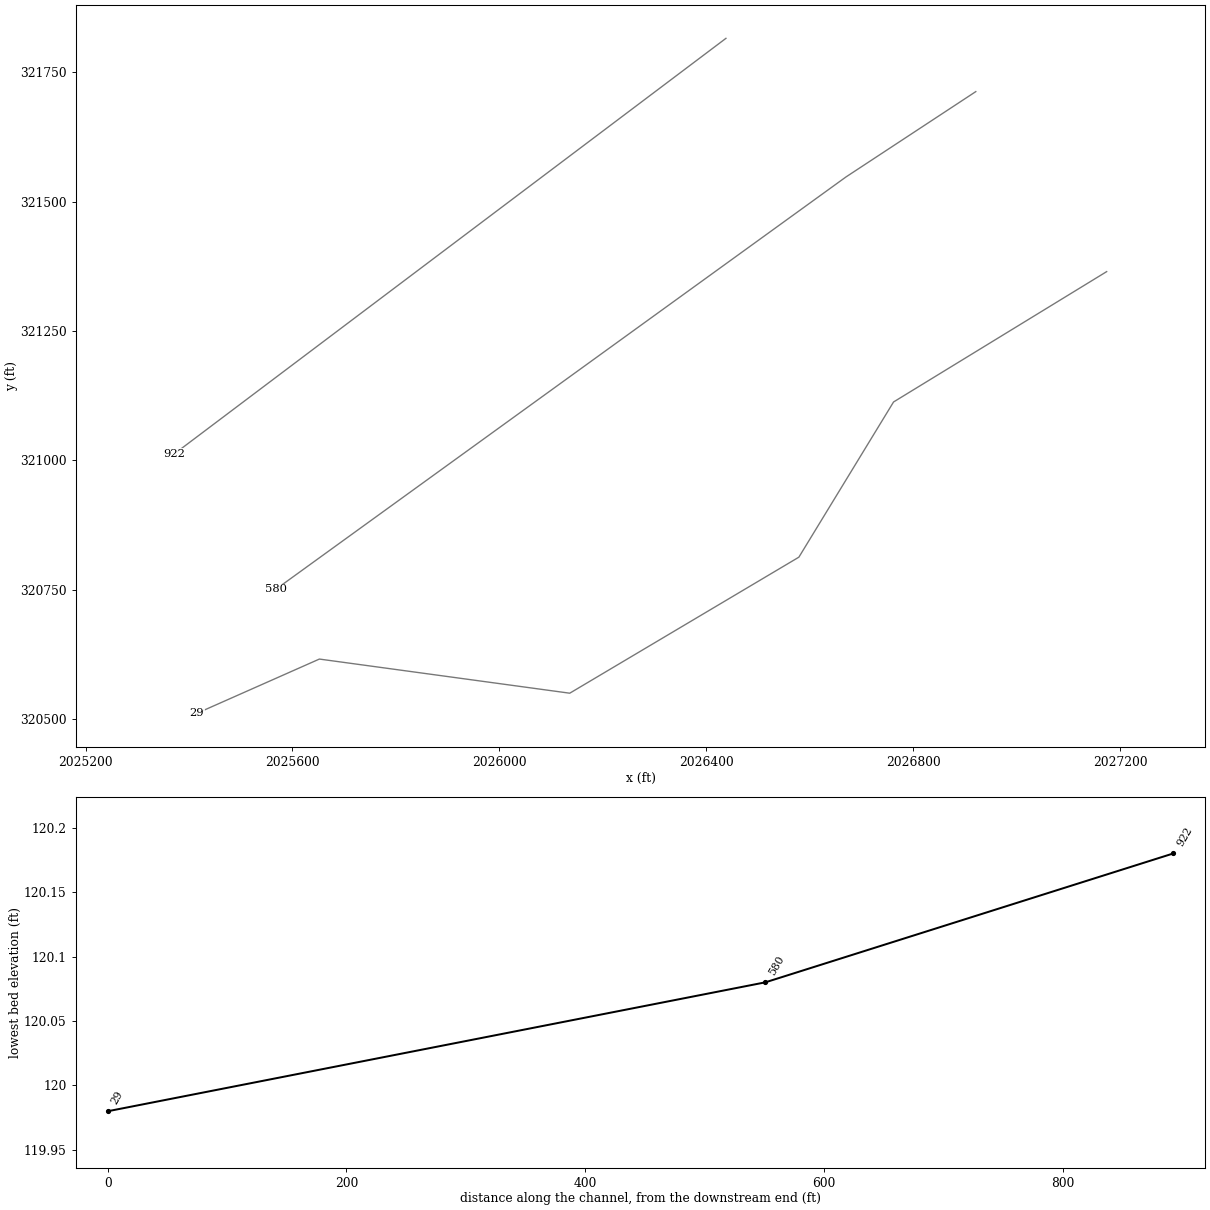
HEC-RAS study Jackson Swamp.prj: Jackson Swamp Limited Detail Study

--- Jackson Swamp.g11 (geometry) --- (continued)

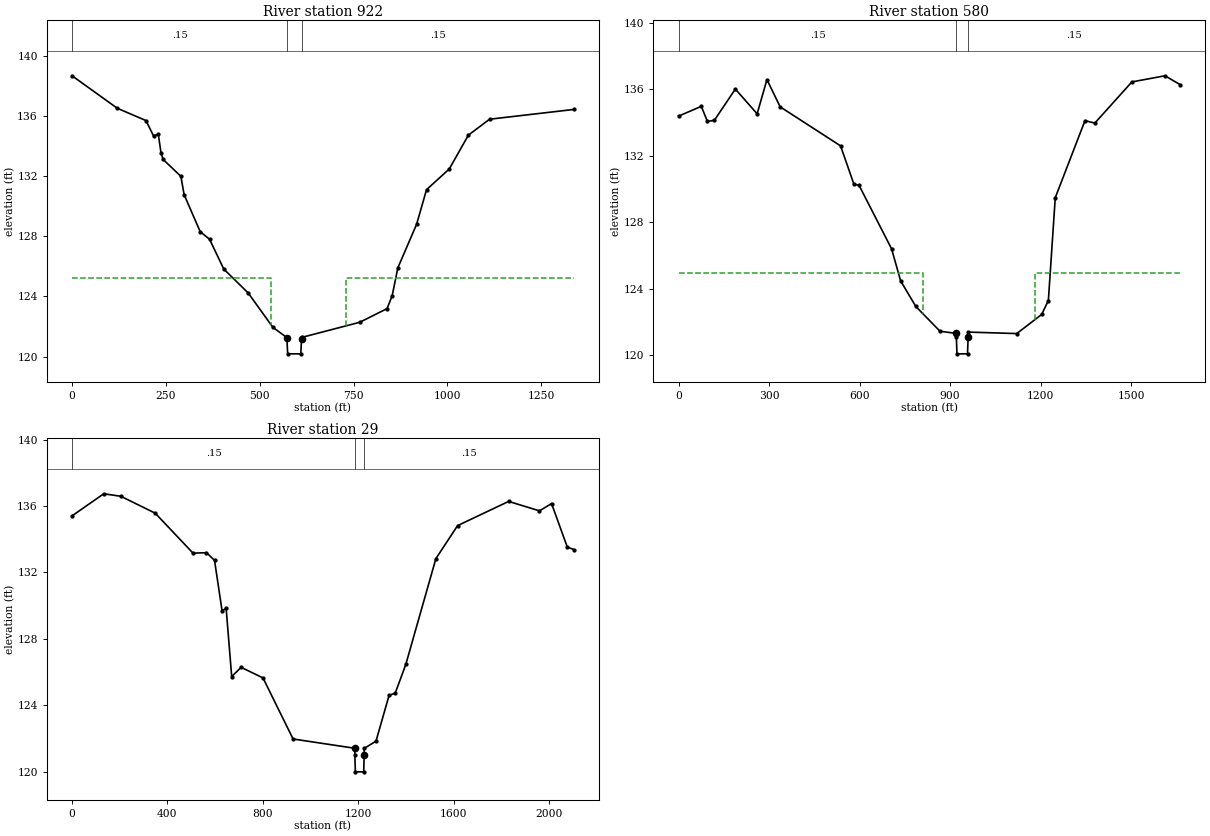
Type RM Length L Ch R = 1 ,922     ,345.3,341.91,344.46
BEGIN DESCRIPTION:
922
END DESCRIPTION:
XS GIS Cut Line= 2
        2026438.         321816.        2025372.         321013.
#Sta/Elev= 30
       0  138.68  120.38  136.52  196.96   135.7  217.05  134.68  229.86  134.78
  237.07  133.53  242.72  133.11  289.97  131.99  298.57  130.77   341.4  128.31
   366.4   127.8  404.27  125.82  469.31  124.23  535.21  121.94  572.49  121.26
  572.49  121.18  574.49  120.18  609.49  120.18  611.49  121.18  611.49  121.27
  766.52  122.28  839.36  123.19     853  124.05  868.04   125.9  918.06   128.8
  944.47   131.1  1005.1  132.48 1056.01  134.73 1112.47  135.79 1337.09  136.44
#Mann= 3 ,-1 , 0
       0     .15       0  572.49     .14       0  611.49     .15       0
#XS Ineff= 2 , 0
       0     530  125.25     730       0  125.25
Permanent Ineff=
       F       F
Bank Sta=572.49,611.49
XS Rating Curve= 0 ,0
Exp/Cntr=0.3,0.1

Type RM Length L Ch R = 1 ,580     ,543.62,551,498.82
BEGIN DESCRIPTION:
580
END DESCRIPTION:
XS GIS Cut Line= 3
        2026921.         321713.        2026670.         321548.
        2025568.         320751.
#Sta/Elev= 30
       0  134.39   75.46  134.98   95.74  134.07  118.77  134.14  188.24  136.02
   260.5  134.53  292.95  136.59  336.85  134.95  536.99   132.6   581.4  130.28
   597.8  130.24   706.1   126.4  736.11  124.47  786.39  122.93  866.61  121.44
  920.72  121.31  920.72  121.08  922.72  120.08  957.72  120.08  959.72  121.08
  959.72  121.39 1120.92   121.3 1203.35  122.45 1225.63  123.29 1248.49  129.48
 1346.98  134.12  1379.6  133.97 1502.29  136.45 1612.09  136.82 1662.95  136.28
#Mann= 3 ,-1 , 0
       0     .15       0  920.72     .14       0  959.72     .15       0
#XS Ineff= 2 , 0
       0     810  124.95    1180       0  124.95
Permanent Ineff=
       F       F
Bank Sta=920.72,959.72
XS Rating Curve= 0 ,0
Exp/Cntr=0.3,0.1

Type RM Length L Ch R = 1 ,29      ,102.58,28.79,95.41
BEGIN DESCRIPTION:
29
END DESCRIPTION:
XS GIS Cut Line= 6
        2027174.         321365.        2026762.         321113.
        2026579.         320813.        2026136.         320550.
        2025652.         320616.        2025415.         320511.
#Sta/Elev= 30
       0  135.41  132.93  136.74  204.47  136.59  348.77  135.57  507.45  133.16
  563.69  133.19   597.5  132.73  629.45  129.66   646.1  129.86  669.52  125.72
  708.99  126.28  800.87  125.64  927.01  121.96 1186.16   121.4 1186.16  120.98
 1188.16  119.98 1223.16  119.98 1225.16  120.98 1225.16  121.39 1274.81  121.83
 1329.64  124.59 1355.28  124.72 1399.69  126.45 1525.92  132.83 1616.86  134.82
 1831.16  136.28 1960.49  135.71 2011.09  136.15 2077.34  133.52 2104.66  133.38
#Mann= 3 ,-1 , 0
       0     .15       0 1186.16     .14       0 1225.16     .15       0
Bank Sta=1186.16,1225.16
XS Rating Curve= 0 ,0
Exp/Cntr=0.3,0.1
Stream Node=Jackson Swamp   ,Reach-1         , 0 , 0 ,Upstream end
Stream Node=Jackson Swamp   ,Reach-1         , 0 , 1 ,Downstream end

Chan Stop Cuts=-1
CM Template=Culvert,False, 0 , 1
 CM Simple Trapezoid=6,7,1,0.14
CM Template=US Channel,False, 0 , 1
 CM Simple Trapezoid=1,23,2,0.14
CM Template=DS Channel,False, 0 , 1
 CM Simple Trapezoid=1,35,2,0.14
Use User Specified Reach Order=0