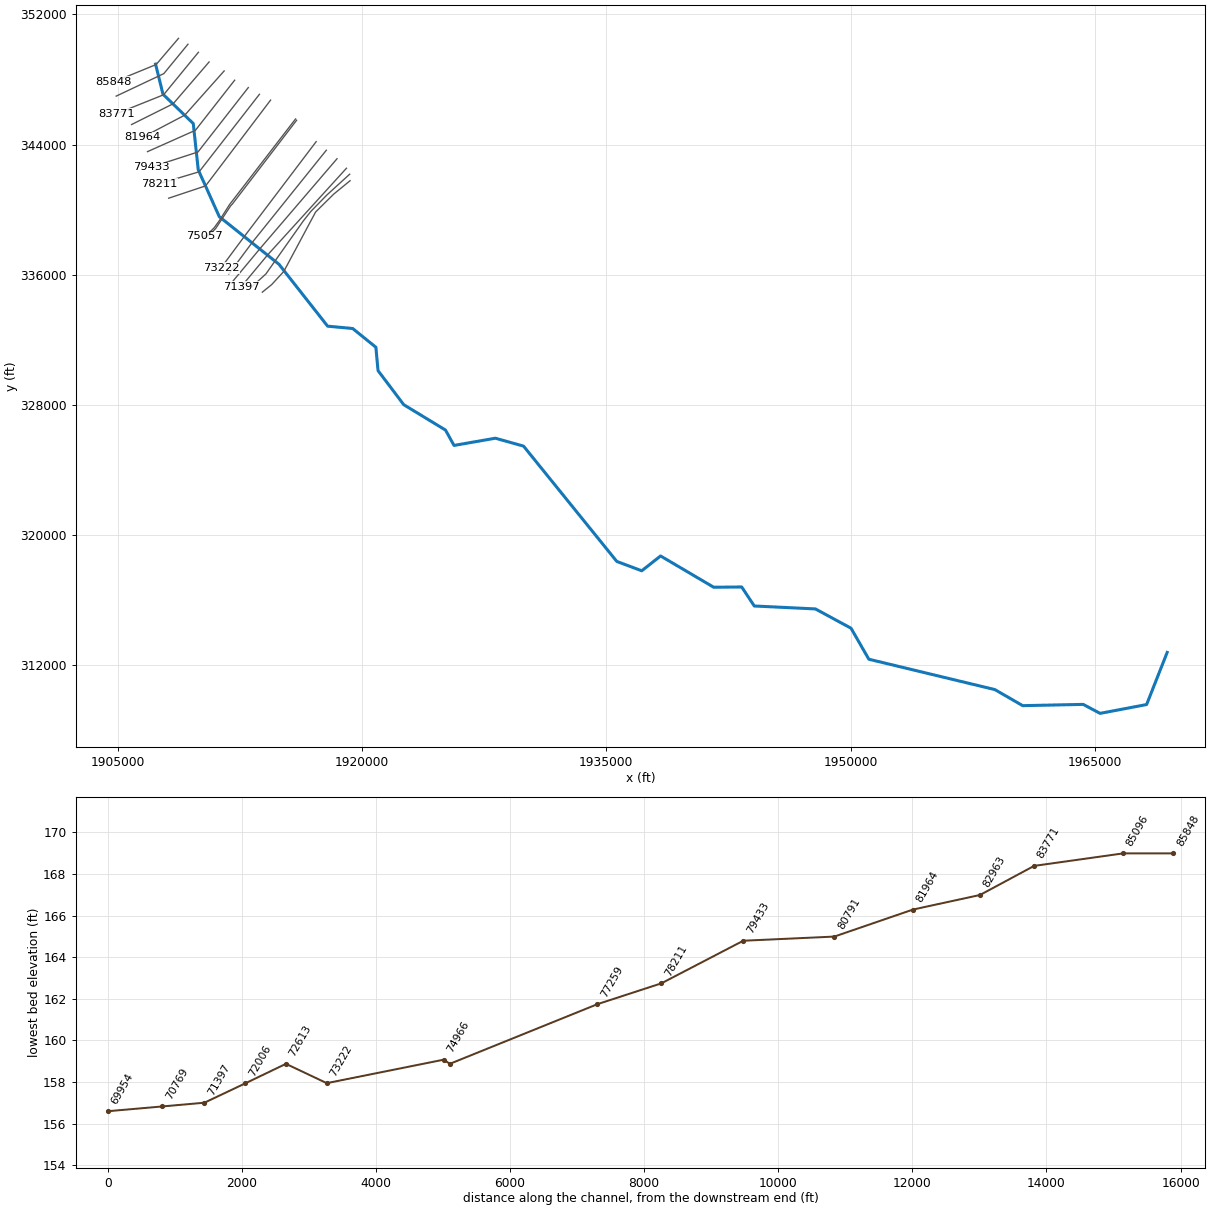
--- BackSwamp.prj (project) ---

Proj Title=Back Swamp Detailed Study
Current Plan=p02
Default Exp/Contr=0.3,0.1
English Units
Geom File=g01
Flow File=f01
Flow File=f02
Flow File=f03
Plan File=p01
Plan File=p02
Plan File=p03
Y Axis Title=Elevation
X Axis Title(PF)=Main Channel Distance
X Axis Title(XS)=Station
BEGIN DESCRIPTION:
Back Swamp
END DESCRIPTION:
DSS Export Rating Curves= 0
DSS Export Rating Curve Sorted= 0
DSS Export Volume Flow Curves= 0
DXF Filename=..\BackSwamp4.
DXF OffsetX= 0
DXF OffsetY= 0
DXF ScaleX= 1
DXF ScaleY= 10

--- BackSwamp.p02 (plan) ---

Plan Title=Floodway Run
Program Version=4.00
Short Identifier=FW
Geom File=g01
Flow File=f02
Subcritical Flow
K Sum by GR= 0
Std Step Tol= 0.01
Critical Tol= 0.01
Num of Std Step Trials= 20
Max Error Tol= 0.3
Flow Tol Ratio= 0.001
Split Flow NTrial= 30
Split Flow Tol= 0.02
Split Flow Ratio= 0.02
Log Output Level= 1
Friction Slope Method= 1
Unsteady Friction Slope Method= 2
Unsteady Bridges Friction Slope Method= 1
Calc Critical at every XS
Parabolic Critical Depth
Global Vel Dist= 0 , 0 , 0
Global Log Level= 1
Log Level Location=Back Swamp      ,Reach-1         ,85848   , 1 , 1
Log Level Location=Back Swamp      ,Reach-1         ,85096   , 1 , 1
Log Level Location=Back Swamp      ,Reach-1         ,83771   , 1 , 1
Log Level Location=Back Swamp      ,Reach-1         ,82963   , 1 , 1
Log Level Location=Back Swamp      ,Reach-1         ,81964   , 1 , 1
Log Level Location=Back Swamp      ,Reach-1         ,80791   , 1 , 1
Log Level Location=Back Swamp      ,Reach-1         ,79433   , 1 , 1
Log Level Location=Back Swamp      ,Reach-1         ,78211   , 1 , 1
Log Level Location=Back Swamp      ,Reach-1         ,77259   , 1 , 1
Log Level Location=Back Swamp      ,Reach-1         ,75057   , 1 , 1
Log Level Location=Back Swamp      ,Reach-1         ,75016   , 1 , 1
Log Level Location=Back Swamp      ,Reach-1         ,74966   , 1 , 1
Log Level Location=Back Swamp      ,Reach-1         ,73222   , 1 , 1
Log Level Location=Back Swamp      ,Reach-1         ,72613   , 1 , 1
Log Level Location=Back Swamp      ,Reach-1         ,72006   , 1 , 1
Log Level Location=Back Swamp      ,Reach-1         ,71397   , 1 , 1
Log Level Location=Back Swamp      ,Reach-1         ,70769   , 1 , 1
Log Level Location=Back Swamp      ,Reach-1         ,69954   , 1 , 1
Log Level Location=Back Swamp      ,Reach-1         ,69122   , 1 , 1
Log Level Location=Back Swamp      ,Reach-1         ,69096   , 1 , 1
Log Level Location=Back Swamp      ,Reach-1         ,69046   , 1 , 1
Log Level Location=Back Swamp      ,Reach-1         ,67447   , 1 , 1
Log Level Location=Back Swamp      ,Reach-1         ,65004   , 1 , 1
Log Level Location=Back Swamp      ,Reach-1         ,63505   , 1 , 1
Log Level Location=Back Swamp      ,Reach-1         ,62767   , 1 , 1
Log Level Location=Back Swamp      ,Reach-1         ,61788   , 1 , 1
Log Level Location=Back Swamp      ,Reach-1         ,60681   , 1 , 1
Log Level Location=Back Swamp      ,Reach-1         ,58284   , 1 , 1
Log Level Location=Back Swamp      ,Reach-1         ,56361   , 1 , 1
Log Level Location=Back Swamp      ,Reach-1         ,55632   , 1 , 1
Log Level Location=Back Swamp      ,Reach-1         ,54856   , 1 , 1
Log Level Location=Back Swamp      ,Reach-1         ,53953   , 1 , 1
Log Level Location=Back Swamp      ,Reach-1         ,53299   , 1 , 1
Log Level Location=Back Swamp      ,Reach-1         ,53248   , 1 , 1
Log Level Location=Back Swamp      ,Reach-1         ,53183   , 1 , 1
Log Level Location=Back Swamp      ,Reach-1         ,52675   , 1 , 1
Log Level Location=Back Swamp      ,Reach-1         ,52201   , 1 , 1
Log Level Location=Back Swamp      ,Reach-1         ,51840   , 1 , 1
Log Level Location=Back Swamp      ,Reach-1         ,51468   , 1 , 1
Log Level Location=Back Swamp      ,Reach-1         ,51180   , 1 , 1
Log Level Location=Back Swamp      ,Reach-1         ,49348   , 1 , 1
Log Level Location=Back Swamp      ,Reach-1         ,47592   , 1 , 1
Log Level Location=Back Swamp      ,Reach-1         ,45735   , 1 , 1
Log Level Location=Back Swamp      ,Reach-1         ,45705   , 1 , 1
Log Level Location=Back Swamp      ,Reach-1         ,45628   , 1 , 1
Log Level Location=Back Swamp      ,Reach-1         ,43638   , 1 , 1
Log Level Location=Back Swamp      ,Reach-1         ,41702   , 1 , 1
Log Level Location=Back Swamp      ,Reach-1         ,40192   , 1 , 1
Log Level Location=Back Swamp      ,Reach-1         ,40170   , 1 , 1
Log Level Location=Back Swamp      ,Reach-1         ,40119   , 1 , 1
Log Level Location=Back Swamp      ,Reach-1         ,38807   , 1 , 1
Log Level Location=Back Swamp      ,Reach-1         ,36756   , 1 , 1
Log Level Location=Back Swamp      ,Reach-1         ,35290   , 1 , 1
Log Level Location=Back Swamp      ,Reach-1         ,34027   , 1 , 1
Log Level Location=Back Swamp      ,Reach-1         ,32617   , 1 , 1
Log Level Location=Back Swamp      ,Reach-1         ,32567   , 1 , 1
Log Level Location=Back Swamp      ,Reach-1         ,32517   , 1 , 1
Log Level Location=Back Swamp      ,Reach-1         ,30593   , 1 , 1
Log Level Location=Back Swamp      ,Reach-1         ,28739   , 1 , 1
Log Level Location=Back Swamp      ,Reach-1         ,27056   , 1 , 1
Log Level Location=Back Swamp      ,Reach-1         ,25391   , 1 , 1
Log Level Location=Back Swamp      ,Reach-1         ,23635   , 1 , 1
Log Level Location=Back Swamp      ,Reach-1         ,23595   , 1 , 1
Log Level Location=Back Swamp      ,Reach-1         ,23534   , 1 , 1
Log Level Location=Back Swamp      ,Reach-1         ,21301   , 1 , 1
Log Level Location=Back Swamp      ,Reach-1         ,19549   , 1 , 1
Log Level Location=Back Swamp      ,Reach-1         ,17293   , 1 , 1
Log Level Location=Back Swamp      ,Reach-1         ,15415   , 1 , 1
Log Level Location=Back Swamp      ,Reach-1         ,13639   , 1 , 1
Log Level Location=Back Swamp      ,Reach-1         ,11889   , 1 , 1
Log Level Location=Back Swamp      ,Reach-1         ,11861   , 1 , 1
Log Level Location=Back Swamp      ,Reach-1         ,11810   , 1 , 1
Log Level Location=Back Swamp      ,Reach-1         ,11742   , 1 , 1
Log Level Location=Back Swamp      ,Reach-1         ,11681   , 1 , 1
Log Level Location=Back Swamp      ,Reach-1         ,11660   , 1 , 1
Log Level Location=Back Swamp      ,Reach-1         ,11629   , 1 , 1
Log Level Location=Back Swamp      ,Reach-1         ,10275   , 1 , 1
Log Level Location=Back Swamp      ,Reach-1         ,9032    , 1 , 1
Log Level Location=Back Swamp      ,Reach-1         ,7821    , 1 , 1
Log Level Location=Back Swamp      ,Reach-1         ,6112    , 1 , 1
Log Level Location=Back Swamp      ,Reach-1         ,5145    , 1 , 1
Log Level Location=Back Swamp      ,Reach-1         ,4016    , 1 , 1
Log Level Location=Back Swamp      ,Reach-1         ,3982    , 1 , 1
Log Level Location=Back Swamp      ,Reach-1         ,3927    , 1 , 1
Log Level Location=Back Swamp      ,Reach-1         ,3660    , 1 , 1
Log Level Location=Back Swamp      ,Reach-1         ,3397    , 1 , 1
Log Level Location=Back Swamp      ,Reach-1         ,3189    , 1 , 1
Log Level Location=Back Swamp      ,Reach-1         ,3117    , 1 , 1
Log Level Location=Back Swamp      ,Reach-1         ,2993    , 1 , 1
Log Level Location=Back Swamp      ,Reach-1         ,2872    , 1 , 1
Log Level Location=Back Swamp      ,Reach-1         ,2727    , 1 , 1
Log Level Location=Back Swamp      ,Reach-1         ,2700    , 1 , 1
Log Level Location=Back Swamp      ,Reach-1         ,2643    , 1 , 1
Log Level Location=Back Swamp      ,Reach-1         ,1851    , 1 , 1
Log Level Location=Back Swamp      ,Reach-1         ,1577    , 1 , 1
Log Level Location=Back Swamp      ,Reach-1         ,1347    , 1 , 1
CheckData=True
Encroach Param=-1 ,10,10, 2
Encroach River=Back Swamp
Encroach Reach=Reach-1
Encroach Node=85848
       1    4960  5032.6
Encroach Node=85096
       1    4799    5066
Encroach Node=83771
       1    4900    5143
Encroach Node=82963
       1    4783    5235
Encroach Node=81964
       1    4751    5115
Encroach Node=80791
       1    4656    5495
Encroach Node=79433
       1    4546    5350
Encroach Node=78211
       1    4550    5300
Encroach Node=77259
       1  4532.3    5256
Encroach Node=75057
       1    4580    5210
Encroach Node=74966
       1    4590    5210
Encroach Node=73222
       1    4300    5100
Encroach Node=72613
       1    4400    5350
Encroach Node=72006
       1    4500    5400
Encroach Node=71397
       1    4700    5400
Encroach Node=70769
       1    4500    5500
Encroach Node=69954
       1 4052.62    5100
Encroach Node=69122
       1    4600    5200
Encroach Node=69046
       1    4585    5209
Encroach Node=67447
       1    3853    5134
Encroach Node=65004
       1    4150    5500
Encroach Node=63505
       1    4150    5500
Encroach Node=62767
       1    4200    5600
Encroach Node=61788
       1    4100    5250
Encroach Node=60681
       1    4300    5250
Encroach Node=58284
       1    4500    5700
Encroach Node=56361
       1    4900    6300
Encroach Node=55632
       1    4900    6400
Encroach Node=54856
       1    4850    6300
Encroach Node=53953
       1    4800    5600
Encroach Node=53299
       1    4920    5080
Encroach Node=53183
       1    4842    5152
Encroach Node=52675
       1    4800    5310
Encroach Node=52201
       1    4800    5370
Encroach Node=51840
       1    4778    5210
Encroach Node=51180
       1    4824    5175
Encroach Node=49348
       1    4050    5640
Encroach Node=47592
       1    4250    5560
Encroach Node=45735
       1    4969    5031
Encroach Node=45628
       1    4966    5039
Encroach Node=43638
       1    4074    5378
Encroach Node=41702
       1    3822    5273
Encroach Node=40192
       1    4572    5550
Encroach Node=40119
       1    4572    5500
Encroach Node=38807
       1 3651.73  5023.5
Encroach Node=36756
       1    3200  5108.5
Encroach Node=35290
       1    3000    5028
Encroach Node=34027
       1    3500    5028
Encroach Node=32617
       1    3280    5430
Encroach Node=32517
       1    3220    5500
Encroach Node=30593
       1    3250    5300
Encroach Node=28739
       1    3000    5400
Encroach Node=27056
       1    3500    5200
Encroach Node=25391
       1    4505    5300
Encroach Node=23635
       1    4600    5200
Encroach Node=23534
       1    4600    5200
Encroach Node=21301
       1    4465    5820
Encroach Node=19549
       1 3125.23  5041.3
Encroach Node=17293
       1  2766.2  5051.7
Encroach Node=15415
       1  3580.6  5038.4
Encroach Node=13639
       1 3991.48  5032.7
Encroach Node=11889
       1 3179.42 5149.82
Encroach Node=11810
       1 3176.12 5146.52
Encroach Node=11742
       1 3176.12    5150
Encroach Node=11681
       1 3120.41  5038.1
Encroach Node=11629
       1 3120.41  5038.1
Encroach Node=10275
       1 3638.12 5088.03
Encroach Node=9032
       1 3330.59  5028.7
Encroach Node=7821
       1 3757.13 5312.11
Encroach Node=6112
       1 3823.63 5378.03
Encroach Node=5145
       1 3767.95 5488.48
Encroach Node=4016
       1    3620    5066
Encroach Node=3927
       1    3578    5100
Encroach Node=3660
       1    3644    5200
Encroach Node=3397
       1    3694    5180
Encroach Node=3189
       1    3790    5075
Encroach Node=2993
       1  3815.4  5057.2
Encroach Node=2872
       1    3785    5150
Encroach Node=2727
       1    3767    5075
Encroach Node=2643
       1    3970    5114
Encroach Node=2394
       1    4500    5162
Encroach Node=1851
       1    4775    5380
Encroach Node=1585
       1    4623    5225
Encroach Node=1347
       1    4498    5157
BEGIN DESCRIPTION:
Floodway Profiles
END DESCRIPTION:
Computation Interval=1HOUR
Output Interval=1HOUR
Run HTab= 0
Run UNet= 0
Run PostProcess= 0
Run WQNet= 0
UNET Theta= 1
UNET Theta Warmup= 1
UNET ZTol= 0.02
UNET ZSATol= 0.05
UNET MxIter= 20
UNET MaxInSteps= 0
UNET DtIC= 0
UNET DtMin= 0
UNET MaxCRTS= 20
UNET WFStab= 2
UNET SFStab= 1
UNET WFX= 1
UNET SFX= 1
UNET DSS MLevel= 4
UNET DZMax Abort= 100
UNET Convert EG Bridges= 0
UNET Use Existing IB Tables=-1
UNET Froude Reduction=False
UNET Froude Limit= 1
UNET Froude Power= 10
UNET Time Slicing=0,0, 5
Instantaneous Interval=1HOUR
Write IC File= 0
Echo Input=False
Echo Output=False
Write Detailed= 0
Detailed Automatic Start=False, 10
WQ ULTIMATE=-1
WQ Max Comp Step=1HOUR
WQ Output Interval=15MIN
WQ Output Selected Increments= 0
WQ Output face flow=0
WQ Output face velocity=0
WQ Output face area=0
WQ Output face dispersion=0
WQ Output cell volume=0
WQ Output cell surface area=0
WQ Output cell continuity=0
WQ Output face conc=0
WQ Output face dconc_dx=0
WQ Output face courant=0
WQ Output face peclet=0
WQ Output face adv mass=0
WQ Output face disp mass=0
WQ Output cell mass=0
WQ Output cell source sink temp=0
WQ Output cell source sink nsm=0
WQ Output MaxMinRange=-1
WQ Daily Max Min Mean=-1
WQ Daily Range=0
WQ Daily Time=0
WQ Create Restart=0
WQ Fixed Restart=0
WQ System Summary=False
Sorting and Armoring Iterations= 10
XS Update Threshold= 0.02
Hydraulics Update Threshold= 0.02
Energy Slope Method= 1
Volume Change Method= 0
XS Weighting Method= 0
Number of US Weighted Cross Sections= 1
Number of DS Weighted Cross Sections= 1
Upstream XS Weight=0.25
Main XS Weight=0.5
Downstream XS Weight=0.25
Number of DS XS's Weighted with US Boundary= 1
Upstream Boundary Weight= 1
Weight of XSs Associated with US Boundary= 0
Number of US XS's Weighted with DS Boundary= 1
Downstream Boundary Weight= 0.5
Weight of XSs Associated with DS Boundary= 0.5
Sediment Output Level= 4
Mass or Volume Output= 0
Output Increment Type= 1
Profile and TS Output Increment= 10
XS Output Flag= 0
XS Output Increment= 10
Disregard all LS=0
Disregard all Conn=0
Disregard all Breaches=0
Disregard all Pumps=0

--- BackSwamp.p01 (plan) ---

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Plan Title=Multi Profiles Effective Condition
Short Identifier=Multi
Geom File=g01
Flow File=f01
Log Output Level= 0
Global Log Level= 0
Encroach Param=-1 ,0,0, 0
Multiple Profiles

--- BackSwamp.p03 (plan) ---

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Plan Title=Defined Future Condition Profiles
Short Identifier=DFC
Geom File=g01
Flow File=f03
Log Output Level= 0
Global Log Level= 0
Encroach Param=-1 ,0,0, 0
Defined Future Condition Profiles
DSS File=dss

--- BackSwamp.f02 (steady flow) ---

Flow Title=FW 09 USGS Rural Regression, SIR 09-5158
Program Version=4.00
Number of Profiles= 2
Profile Names=1%,1%FW
River Rch & RM=Back Swamp,Reach-1         ,85848
     281     281
River Rch & RM=Back Swamp,Reach-1         ,83771
     444     444
River Rch & RM=Back Swamp,Reach-1         ,77259
     624     624
River Rch & RM=Back Swamp,Reach-1         ,71397
     814     814
River Rch & RM=Back Swamp,Reach-1         ,69954
     929     929
River Rch & RM=Back Swamp,Reach-1         ,65004
    1070    1070
River Rch & RM=Back Swamp,Reach-1         ,53953
    1620    1620
River Rch & RM=Back Swamp,Reach-1         ,47592
    1830    1830
River Rch & RM=Back Swamp,Reach-1         ,41702
    2180    2180
River Rch & RM=Back Swamp,Reach-1         ,28739
    2440    2440
River Rch & RM=Back Swamp,Reach-1         ,17293
    2830    2830
River Rch & RM=Back Swamp,Reach-1         ,7821
    3130    3130
Boundary for River Rch & Prof#=Back Swamp,Reach-1         , 1
Up Type= 0
Dn Type= 3
Dn Slope=0.0005
Boundary for River Rch & Prof#=Back Swamp,Reach-1         , 2
Up Type= 0
Dn Type= 3
Dn Slope=0.0005
DSS Import GetInterval= 0
DSS Import GetPeak= 0
DSS Import FillOption= 0

--- BackSwamp.f01 (steady flow) ---

Flow Title=2009 USGS Rural Regression, SIR 09-5158
Program Version=4.00
Number of Profiles= 5
Profile Names=10%,4%,2%,1%,0.2%
River Rch & RM=Back Swamp,Reach-1         ,85848
     127     180     227     281     408
River Rch & RM=Back Swamp,Reach-1         ,83771
     204     288     362     444     640
River Rch & RM=Back Swamp,Reach-1         ,77259
     291     407     509     624     893
River Rch & RM=Back Swamp,Reach-1         ,71397
     383     533     666     814    1160
River Rch & RM=Back Swamp,Reach-1         ,69954
     440     611     762     929    1320
River Rch & RM=Back Swamp,Reach-1         ,65004
     509     705     878    1070    1520
River Rch & RM=Back Swamp,Reach-1         ,53953
     784    1080    1340    1620    2280
River Rch & RM=Back Swamp,Reach-1         ,47592
     889    1220    1510    1830    2570
River Rch & RM=Back Swamp,Reach-1         ,41702
    1070    1460    1800    2180    3050
River Rch & RM=Back Swamp,Reach-1         ,28739
    1200    1630    2020    2440    3400
River Rch & RM=Back Swamp,Reach-1         ,17293
    1400    1900    2350    2830    3940
River Rch & RM=Back Swamp,Reach-1         ,7821
    1550    2110    2600    3130    4350
Boundary for River Rch & Prof#=Back Swamp,Reach-1         , 1
Up Type= 0
Dn Type= 3
Dn Slope=0.001
Boundary for River Rch & Prof#=Back Swamp,Reach-1         , 2
Up Type= 0
Dn Type= 3
Dn Slope=0.001
Boundary for River Rch & Prof#=Back Swamp,Reach-1         , 3
Up Type= 0
Dn Type= 3
Dn Slope=0.001
Boundary for River Rch & Prof#=Back Swamp,Reach-1         , 4
Up Type= 0
Dn Type= 3
Dn Slope=0.001
Boundary for River Rch & Prof#=Back Swamp,Reach-1         , 5
Up Type= 0
Dn Type= 3
Dn Slope=0.001
DSS Import GetInterval= 0
DSS Import GetPeak= 0
DSS Import FillOption= 0

--- BackSwamp.f03 (steady flow) ---

Flow Title=DFC 01 USGS Urban Regression, FS 007-00
Program Version=4.00
Number of Profiles= 3
Profile Names=1% @ 10% imperv,1% @ 20% imperv,1% @ 35% imperv
River Rch & RM=Back Swamp,Reach-1         ,85848
     359     460     562
River Rch & RM=Back Swamp,Reach-1         ,83771
     584     748     914
River Rch & RM=Back Swamp,Reach-1         ,77259
     836    1070    1310
River Rch & RM=Back Swamp,Reach-1         ,71397
    1110    1420    1740
River Rch & RM=Back Swamp,Reach-1         ,69954
    1280    1640    2000
River Rch & RM=Back Swamp,Reach-1         ,65004
    1480    1900    2320
River Rch & RM=Back Swamp,Reach-1         ,53953
    2310    2950    3610
River Rch & RM=Back Swamp,Reach-1         ,47592
    2620    3360    4100
River Rch & RM=Back Swamp,Reach-1         ,41702
    3150    4040    4940
River Rch & RM=Back Swamp,Reach-1         ,28739
    3550    4550    5560
River Rch & RM=Back Swamp,Reach-1         ,17293
    4160    5340    6520
River Rch & RM=Back Swamp,Reach-1         ,7821
    4630    5940    7250
Boundary for River Rch & Prof#=Back Swamp,Reach-1         , 1
Up Type= 0
Dn Type= 3
Dn Slope=0.0005
Boundary for River Rch & Prof#=Back Swamp,Reach-1         , 2
Up Type= 0
Dn Type= 3
Dn Slope=0.0005
Boundary for River Rch & Prof#=Back Swamp,Reach-1         , 3
Up Type= 0
Dn Type= 3
Dn Slope=0.0005
DSS Import GetInterval= 0
DSS Import GetPeak= 0
DSS Import FillOption= 0

--- BackSwamp.g01 (geometry) ---

Geom Title=NCFMP LiDAR, Survey Structures_Channel
Program Version=4.00

River Reach=Back Swamp      ,Reach-1
Reach XY= 30
      1907326.36       348940.75      1907780.25        347090.9
       1909640.2        345287.8      1909946.65       342446.65
      1911238.55        339564.9      1914903.25       336639.25
      1917891.85       332836.45       1919430.3        332693.9
       1920853.7        331540.7       1920986.6        330104.1
       1922565.4        328012.3      1925130.55       326451.45
      1925652.75       325508.45      1928192.11       325952.32
      1929922.35       325465.75       1935646.3        318380.5
       1937179.5        317806.1       1938334.7        318717.8
       1941597.5        316794.2       1943315.6        316811.5
       1944089.2        315642.5       1947843.6        315461.8
      1950030.05       314276.85       1951122.5        312371.6
       1958863.9        310504.8       1960568.5        309518.2
       1964284.8        309595.9       1965323.4        309043.8
       1968179.6        309586.4      1969441.85       312789.75

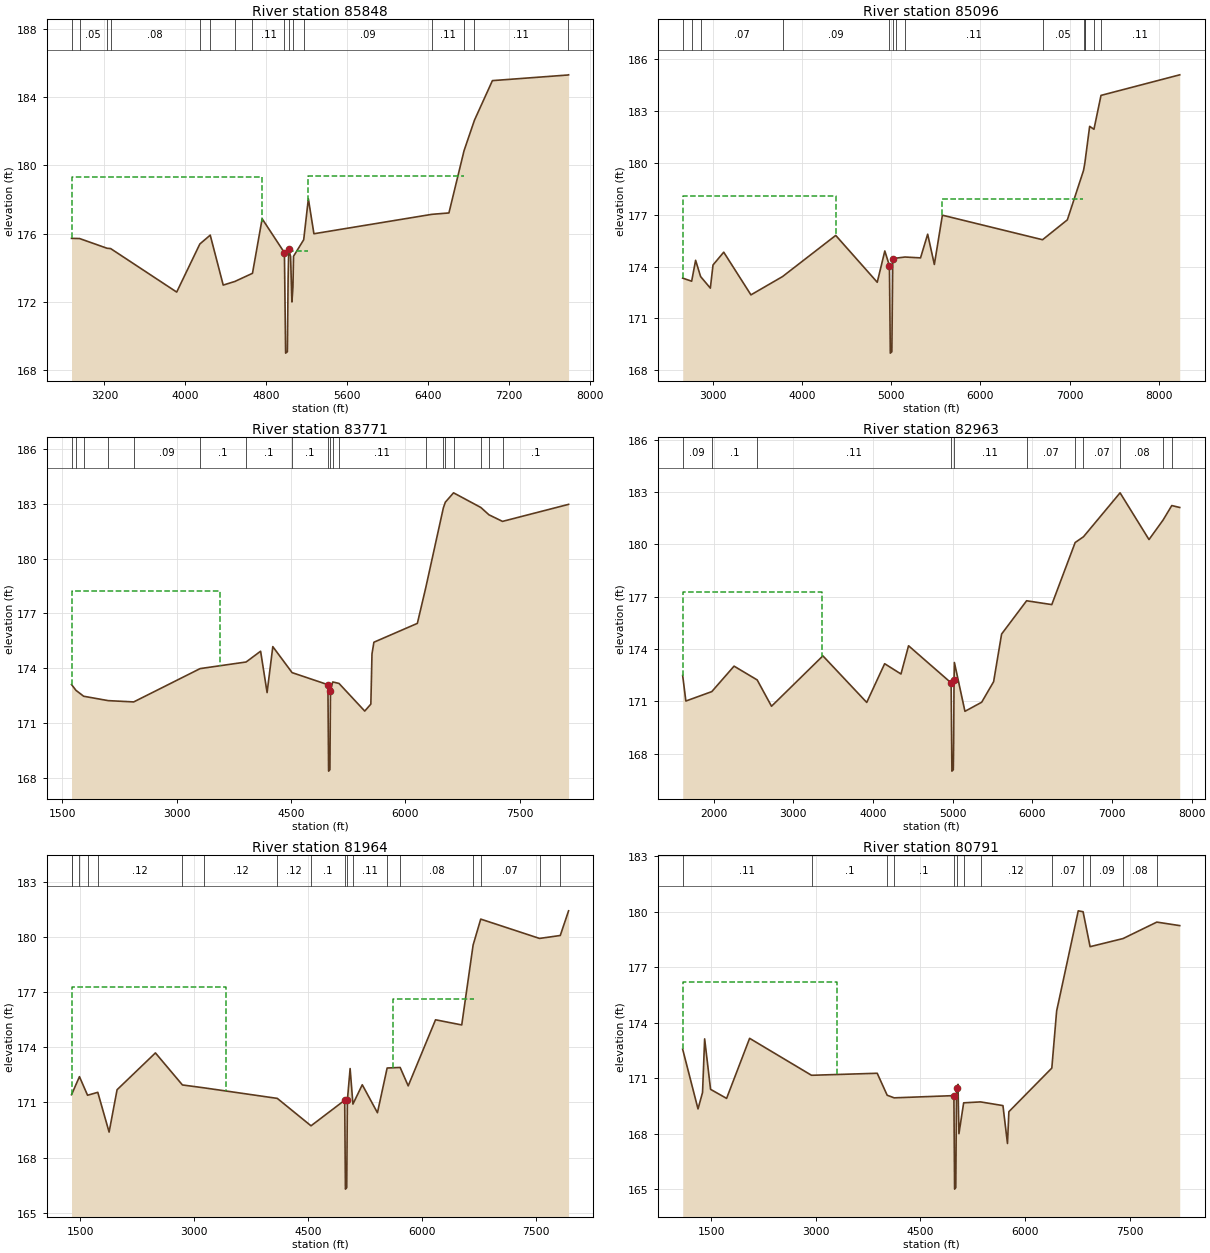
Type RM Length L Ch R = 1 ,85848   ,771,752,740
BEGIN DESCRIPTION:
85848
END DESCRIPTION:
XS GIS Cut Line= 4
       1908734.7       350524.36      1907404.04       348964.34
      1907273.22       348878.35      1904767.93       347850.08
#Sta/Elev= 30
  2874.3  175.72  2953.8  175.71  3225.5  175.14  3261.6  175.12  3914.3  172.57
  4143.3  175.39  4245.9  175.91  4374.3  172.98  4488.4  173.19  4663.7  173.67
  4759.3  176.87  4979.6  174.88  4991.5  168.99  5008.8  169.07  5016.1  173.37
 5022.02  175.08  5040.5  174.66  5053.7  171.99  5063.9  172.88  5069.7  174.67
  5170.3  175.64  5216.3  178.04  5271.3  175.99  6438.7  177.13  6606.3  177.21
  6755.7  180.86  6858.7  182.65  7036.3  184.97  7783.6   185.3  7789.4  185.31
#Mann= 16 ,-1 , 0
  2874.3     .06       0  2953.8     .05       0  3225.5     .06       0
  3261.6     .08       0  4143.3     .05       0  4245.9     .08       0
  4488.4     .09       0  4663.7     .11       0  4979.6     .08       0
 5022.02     .11       0  5063.9     .05       0  5170.3     .09       0
  6438.7     .11       0  6755.7     .05       0  6858.7     .11       0
  7783.6      .1       0
#XS Ineff= 3 ,-1
 5214.29 6757.14  179.38  2874.3 4753.57  179.32 5030.71 5209.01  174.99
Permanent Ineff=
       F       F       F
Bank Sta=4979.6,5022.02
XS Rating Curve= 0 ,0
Exp/Cntr=0.3,0.1

Type RM Length L Ch R = 1 ,85096   ,1340,1325,1335
BEGIN DESCRIPTION:
85096
END DESCRIPTION:
XS GIS Cut Line= 3
      1909314.18       350161.69      1907833.25        348356.4
      1904909.22       346974.11
#Sta/Elev= 30
    2665  173.33  2765.6  173.15    2810  174.36    2866  173.42    2975  172.75
    3005  174.09    3125  174.83    3430  172.36  3784.3  173.42    4380   175.8
    4845  173.09    4930   174.9  4981.6  174.05  4991.5  168.99  5008.8  169.07
  5019.1  174.46  5156.1  174.55    5330   174.5    5410  175.87    5485  174.12
    5575  176.97  6697.2  175.55    6975   176.7  7156.6  179.56  7168.6  179.91
    7170  179.94    7225  182.11  7273.1  181.94  7352.2   183.9  8234.3  185.09
#Mann= 14 ,-1 , 0
    2665     .06       0  2765.6     .05       0    2866     .07       0
  3784.3     .09       0  4981.6     .08       0  5019.1     .09       0
  5055.8     .05       0  5156.1     .11       0  6697.2     .05       0
  7156.6     .08       0  7168.6     .09       0    7170     .05       0
  7273.1      .1       0  7352.2     .11       0
#XS Ineff= 2 ,-1
    2665 4384.92   178.1    5575    7150  177.93
Permanent Ineff=
       F       F
Bank Sta=4981.6,5019.1
XS Rating Curve= 0 ,0
Exp/Cntr=0.3,0.1

Type RM Length L Ch R = 1 ,83771   ,809,808,829
BEGIN DESCRIPTION:
83771
END DESCRIPTION:
XS GIS Cut Line= 3
      1909956.86       349668.56      1907819.15       347055.82
       1904902.5       345883.95
#Sta/Elev= 30
  1619.8  173.12  1678.7   172.8    1779  172.48  2100.8  172.24  2435.7  172.17
  3306.7  173.99  3909.7  174.35  4099.8  174.94  4184.8  172.68  4259.8  175.19
  4512.7  173.77 4982.46  173.11  4991.5  168.39  5008.8  168.47  5016.1  172.77
  5045.6  173.26  5127.9  173.18  5465.6  171.67  5545.6  172.05  5560.6  174.79
  5585.6  175.43  6155.6  176.46  6266.4  178.42  6496.7  182.77  6522.6  183.08
  6630.4  183.59  6988.1  182.79  7094.7  182.39  7272.3  182.03  8138.9  182.96
#Mann= 19 ,-1 , 0
  1619.8     .08       0  1678.7     .05       0    1779     .09       0
  2100.8      .1       0  2435.7     .09       0  3306.7      .1       0
  3909.7      .1       0  4512.7      .1       0 4982.46     .08       0
  5016.1     .05       0  5045.6      .1       0  5127.9     .11       0
  6266.4     .09       0  6496.7     .08       0  6522.6     .05       0
  6630.4     .07       0  6988.1     .05       0  7094.7     .08       0
  7272.3      .1       0
#XS Ineff= 1 ,-1
  1619.8 3572.86  178.24
Permanent Ineff=
       F
Bank Sta=4982.46,5016.1
XS Rating Curve= 0 ,0
Exp/Cntr=0.3,0.1

Type RM Length L Ch R = 1 ,82963   ,1002,999,1049
BEGIN DESCRIPTION:
82963
END DESCRIPTION:
XS GIS Cut Line= 3
      1910611.66       349072.46       1908404.4        346502.4
      1905854.26        345228.1
#Sta/Elev= 30
  1612.2  172.47  1652.2  171.01  1977.6  171.55  2257.2  173.01  2547.5  172.22
  2727.2  170.71  3372.2   173.6  3922.2  170.93  4147.2  173.15  4352.2  172.56
  4447.2  174.18  4981.6  172.05  4991.5  166.99  5008.8  167.07  5013.4  168.72
 5018.21  172.24  5022.6  173.22    5155  170.42    5365  170.94    5515  172.12
    5615  174.85    5929  176.76    6245  176.54  6538.3   180.1  6642.7  180.43
    7102  182.95    7465  180.27  7641.9  181.39  7750.9  182.22  7850.8  182.11
#Mann= 11 ,-1 , 0
  1612.2     .09       0  1977.6      .1       0  2547.5     .11       0
  4981.6     .08       0 5018.21     .11       0    5929     .07       0
  6538.3     .05       0  6642.7     .07       0    7102     .08       0
  7641.9     .05       0  7750.9     .08       0
#XS Ineff= 1 ,-1
 1464.32 3356.78  177.25
Permanent Ineff=
       F
Bank Sta=4981.6,5018.21
XS Rating Curve= 0 ,0
Exp/Cntr=0.3,0.1

Type RM Length L Ch R = 1 ,81964   ,1169,1173,1152
BEGIN DESCRIPTION:
81964
DELETED LIDAR ARTIFACTS IN LEFT OVERANK 750 FEET BANK STATION
END DESCRIPTION:
XS GIS Cut Line= 3
      1911536.91       348520.78      1909121.24       345805.82
      1906543.12       344451.65
#Sta/Elev= 30
  1384.3  171.42  1387.7  171.45  1488.8   172.4  1595.6  171.39  1730.3  171.55
  1879.3  169.39  1984.3  171.69  2489.3  173.69  2844.9  171.95  3134.4  171.79
  4094.3  171.22  4538.6  169.73 4982.06  171.12  4991.5  166.29  5008.8  166.37
 5017.32  171.12  5053.4  172.84  5090.5  170.91  5213.4  171.96  5413.4  170.44
    5541  172.87  5712.4   172.9  5818.4   171.9  6178.4  175.49  6523.4  175.21
  6673.2  179.55  6773.7  180.96  7548.2  179.91    7821  180.07  7930.5  181.41
#Mann= 18 ,-1 , 0
  1384.3     .08       0  1387.7     .05       0  1488.8     .08       0
  1595.6     .11       0  1730.3     .12       0  2844.9     .11       0
  3134.4     .12       0  4094.3     .12       0  4538.6      .1       0
 4982.06     .08       0 5017.32      .1       0  5090.5     .11       0
    5541     .12       0  5712.4     .08       0  6673.2     .05       0
  6773.7     .07       0  7548.2     .07       0    7821     .09       0
#XS Ineff= 2 ,-1
  1384.3 3420.51  177.25 5618.75  6687.5  176.64
Permanent Ineff=
       F       F
Bank Sta=4982.06,5017.32
XS Rating Curve= 0 ,0
Exp/Cntr=0.3,0.1

Type RM Length L Ch R = 1 ,80791   ,1312,1358,1358
BEGIN DESCRIPTION:
80791
END DESCRIPTION:
XS GIS Cut Line= 3
      1912181.47        347951.2      1909772.47       344873.87
       1906831.4       343562.22
#Sta/Elev= 30
  1091.9  172.56  1311.9  169.33  1376.9  170.22  1406.9  173.12  1491.9  170.39
  1721.9   169.9  2051.9  173.15  2939.7  171.15  3881.9  171.26  4024.8  170.07
  4125.1  169.93  4981.6  170.05  4991.5  164.99  5008.8  165.07  5019.1  170.46
  5040.5  170.66  5053.7  167.99  5121.6  169.66  5363.8  169.71    5685  169.51
    5750  167.46    5770  169.18  6385.8  171.54    6455  174.63    6765  180.05
  6834.1     180  6934.8  178.11  7407.8  178.55  7891.7  179.44  8220.3  179.25
#Mann= 13 ,-1 , 0
  1091.9     .11       0  2939.7      .1       0  4024.8     .12       0
  4125.1      .1       0  4981.6     .08       0  5019.1      .1       0
  5121.6     .11       0  5363.8     .12       0  6385.8     .07       0
  6834.1     .05       0  6934.8     .09       0  7407.8     .08       0
  7891.7     .07       0
#XS Ineff= 1 ,-1
 1064.32    3300  176.21
Permanent Ineff=
       F
Bank Sta=4981.6,5019.1
XS Rating Curve= 0 ,0
Exp/Cntr=0.3,0.1

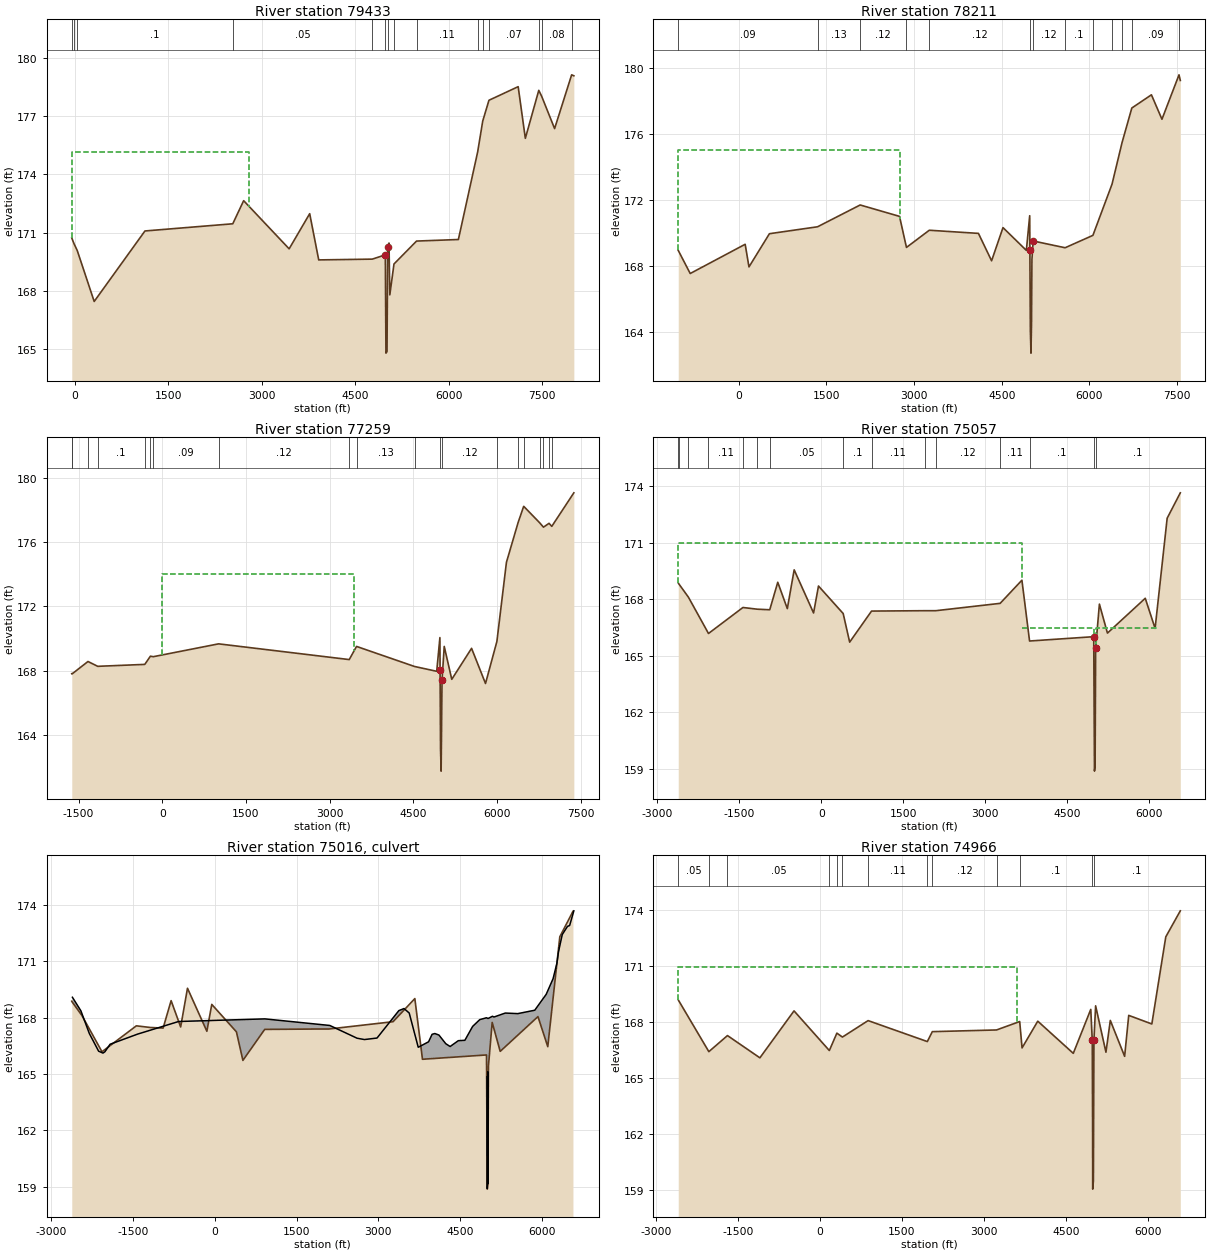
Type RM Length L Ch R = 1 ,79433   ,1147,1222,1199
BEGIN DESCRIPTION:
79433
END DESCRIPTION:
XS GIS Cut Line= 3
      1913019.04       347499.11      1909928.53       343540.19
      1907037.93        342602.7
#Sta/Elev= 30
   -52.8  170.72   -17.3  170.43    35.4  170.07   307.2  167.45  1122.2  171.08
  2532.2  171.45  2707.2  172.64  3437.2  170.16  3767.2  171.97  3912.2  169.59
  4771.9  169.63  4981.6  169.85  4991.5  164.79  5008.8  164.87  5019.1  170.26
  5040.5  170.46  5053.7  167.79  5120.7  169.38    5483  170.56  6154.6  170.64
  6464.2  175.15  6545.6  176.74  6645.6  177.81  7114.6  178.51  7229.6  175.85
  7445.5  178.32  7489.9  178.03  7699.6  176.35  7973.1  179.12  8008.4  179.07
#Mann= 15 ,-1 , 0
   -52.8     .05       0   -17.3     .08       0    35.4      .1       0
  2532.2     .05       0  4771.9     .09       0  4981.6     .08       0
  5019.1     .05       0  5120.7      .1       0    5483     .11       0
  6464.2     .08       0  6545.6     .05       0  6645.6     .07       0
  7445.5     .07       0  7489.9     .08       0  7973.1     .05       0
#XS Ineff= 1 ,-1
   -52.8    2800  175.15
Permanent Ineff=
       F
Bank Sta=4981.6,5019.1
XS Rating Curve= 0 ,0
Exp/Cntr=0.3,0.1

Type RM Length L Ch R = 1 ,78211   ,909,952,961
BEGIN DESCRIPTION:
78211
END DESCRIPTION:
XS GIS Cut Line= 3
       1913703.2       347086.22      1909999.41       342322.84
      1907552.21       341591.97
#Sta/Elev= 30
 -1033.9  168.96  -828.9  167.56   111.1  169.33   176.1  167.96   526.1  169.97
  1349.3  170.39  2078.2  171.71  2751.1  171.02  2869.9  169.14  3260.5  170.18
  4101.1  169.99  4326.1  168.33  4521.1  170.34  4920.7  168.96  4977.8  171.06
  4980.9  169.01    4989  164.12  4999.7  162.74  5008.8  164.54    5016  168.41
  5036.8  169.53  5583.6  169.12  6059.1  169.87  6386.1  172.97  6557.7  175.49
  6724.7  177.58    7060  178.38    7240   176.9  7531.9  179.59    7554  179.25
#Mann= 13 ,-1 , 0
 -1033.9     .09       0  1349.3     .13       0  2078.2     .12       0
  2869.9     .13       0  3260.5     .12       0  4980.9     .08       0
  5036.8     .12       0  5583.6      .1       0  6059.1     .05       0
  6386.1     .06       0  6557.7     .07       0  6724.7     .09       0
  7531.9     .12       0
#XS Ineff= 1 ,-1
-1179.49  2761.9  175.05
Permanent Ineff=
       F
Bank Sta=4980.9,5036.8
XS Rating Curve= 0 ,0
Exp/Cntr=0.3,0.1

Type RM Length L Ch R = 1 ,77259   ,2050,2202,2307
BEGIN DESCRIPTION:
77259 - DELETED LIDAR ARTIFACTS AT IMMEDIATE LEFT OVERBANK
END DESCRIPTION:
XS GIS Cut Line= 3
       1914387.8       346727.91      1910397.28       341456.86
      1908131.65       340701.65
#Sta/Elev= 30
 -1620.8  167.81   -1618  167.79 -1330.2  168.57 -1155.7  168.27  -312.2  168.39
  -211.4   168.9  -159.5  168.87  1011.2  169.67  3352.6  168.69  3483.4  169.51
  4523.3  168.26  4920.7  167.96  4977.8  170.06  4980.9  168.01    4989  163.12
  4999.7  161.74    5016  167.41  5055.4  169.51  5190.4  167.46  5545.4  169.39
  5795.4   167.2  5999.3  169.82  6170.4  174.75  6379.7  177.23  6479.7  178.24
  6764.3  177.22  6834.2  176.94  6934.2  177.18  6983.2  176.99  7378.6  179.08
#Mann= 20 ,-1 , 0
 -1620.8     .05       0   -1618     .08       0 -1330.2     .11       0
 -1155.7      .1       0  -312.2     .05       0  -211.4      .1       0
  -159.5     .09       0  1011.2     .12       0  3352.6     .12       0
  3483.4     .13       0  4523.3     .12       0  4980.9     .08       0
    5016     .12       0  5999.3     .09       0  6379.7     .05       0
  6479.7     .07       0  6764.3     .08       0  6834.2     .05       0
  6934.2     .08       0  6983.2      .1       0
#XS Ineff= 2 , 0
       0    3440     174               0
Permanent Ineff=
       F       F
Bank Sta=4980.9,5016
XS Rating Curve= 0 ,0
Exp/Cntr=0.5,0.3

Type RM Length L Ch R = 1 ,75057   ,103,91,84
BEGIN DESCRIPTION:
75057
END DESCRIPTION:
XS GIS Cut Line= 6
      1915920.09       345568.61      1911863.43       340303.59
      1911251.24         339336.      1910934.69       338896.14
      1910640.13       338596.83      1910294.07       338350.28
#Sta/Elev= 30
 -2617.3  168.87   -2610  168.83 -2431.5  168.11 -2063.9  166.18 -1434.1  167.56
   -1171  167.47  -943.7  167.44  -797.3   168.9  -622.3   167.5  -497.3  169.56
  -142.3  167.27   -52.3   168.7   399.1  167.24   517.7  165.72   917.6  167.37
  1898.3  167.39  2093.4  167.39  3269.3  167.78  3667.7  169.01  3807.5  165.78
  4980.9  166.01  4994.5  158.87    5006  159.16    5016  165.41  5084.6  167.74
  5231.6   166.2  5923.2  168.05  6103.2  166.45  6323.7   172.3  6564.2  173.65
#Mann= 15 ,-1 , 0
 -2617.3     .11       0   -2610     .11       0 -2431.5     .05       0
 -2063.9     .11       0 -1434.1      .1       0   -1171     .11       0
  -943.7     .05       0   399.1      .1       0   917.6     .11       0
  1898.3     .11       0  2093.4     .12       0  3269.3     .11       0
  3807.5      .1       0  4980.9     .08       0    5016      .1       0
#XS Ineff= 3 ,-1
 -2617.3 3665.93     171 3674.76  4980.8  166.46 5019.47  6138.4166.4582
Permanent Ineff=
       F       F       F
Bank Sta=4980.9,5016
XS Rating Curve= 0 ,0
Exp/Cntr=0.5,0.3

Type RM Length L Ch R = 2 ,75016   ,,,
BEGIN DESCRIPTION:
Jacobs Rd (SR 1188),  R_BAS_14
END DESCRIPTION:
Bridge Culvert--1,0,-1,-1, 0
Deck Dist Width WeirC Skew NumUp NumDn MinLoCord MaxHiCord MaxSubmerge Is_Ogee
30,20,3,0, 43, 43, 166.5, , 0.95, 0, 1,1,,
 -2605.3 -2450.3 -2295.3 -2125.3 -2045.3 -2010.3 -1915.3 -1410.3  -660.3   919.7
  2109.7  2609.7  2744.7  2974.7  3374.7  3469.7  3564.7  3729.7  3918.8  3983.8
    4034    4109    4234    4314    4464    4584  4726.5  4856.9  4979.4  5009.1
  5089.5  5117.1  5324.1  5554.1  5864.1  6074.5  6200.2  6270.2  6300.2  6368.6
  6463.6  6503.6  6580.6
  169.08  168.36  167.15  166.21  166.11  166.18  166.58  167.12  167.79  167.93
  167.58   166.9  166.83  166.91  168.37  168.48  168.24  166.42  166.71  167.11
  167.15  167.07  166.61  166.46  166.77  166.79  167.53  167.89  167.99  167.95
  168.07  168.03  168.24  168.21  168.39  169.24  170.07  170.89  171.51  172.42
  172.85   172.9  173.68
   138.5   138.5   138.5   138.5   138.5   138.5   138.5   138.5   138.5   138.5
   138.5   138.5   138.5   138.5   138.5   138.5   138.5   138.5   138.5   138.5
   138.5   138.5   138.5   138.5   138.5   138.5   138.5   138.5   138.5   138.5
   138.5   138.5   138.5   138.5   138.5   138.5   138.5   138.5   138.5   138.5
   138.5   138.5   138.5
 -2605.3 -2450.3 -2295.3 -2125.3 -2045.3 -2010.3 -1915.3 -1410.3  -660.3   919.7
  2109.7  2609.7  2744.7  2974.7  3374.7  3469.7  3564.7  3729.7  3918.8  3983.8
    4034    4109    4234    4314    4464    4584  4726.5  4856.9  4979.4  5009.1
  5089.5  5117.1  5324.1  5554.1  5864.1  6074.5  6200.2  6270.2  6300.2  6368.6
  6463.6  6503.6  6580.6
  169.08  168.36  167.15  166.21  166.11  166.18  166.58  167.12  167.79  167.93
  167.58   166.9  166.83  166.91  168.37  168.48  168.24  166.42  166.71  167.11
  167.15  167.07  166.61  166.46  166.77  166.79  167.53  167.89  167.99  167.95
  168.07  168.03  168.24  168.21  168.39  169.24  170.07  170.89  171.51  172.42
  172.85   172.9  173.68
   140.3   140.3   140.3   140.3   140.3   140.3   140.3   140.3   140.3   140.3
   140.3   140.3   140.3   140.3   140.3   140.3   140.3   140.3   140.3   140.3
   140.3   140.3   140.3   140.3   140.3   140.3   140.3   140.3   140.3   140.3
   140.3   140.3   140.3   140.3   140.3   140.3   140.3   140.3   140.3   140.3
   140.3   140.3   140.3
Culvert=1,6,,59,0.024,0.9,1,2,3,158.9,4995.3,159.12,4995.3,Culvert #1  , 0 ,11.5
Culvert Bottom n=0.024
Culvert=1,6,,59,0.024,0.9,1,2,3,159.13,5004.5,159.46,5004.5,Culvert #2  , 0 ,11.5
Culvert Bottom n=0.024
BC Design=,, 0 ,, 0 ,,,,,,
BC HTab HWMax=173.65
BC Use User HTab Curves=0
BC User HTab FreeFlow(D)= 0

Type RM Length L Ch R = 1 ,74966   ,1785,1744,1734
BEGIN DESCRIPTION:
74966
END DESCRIPTION:
XS GIS Cut Line= 6
      1915987.28       345491.89       1912035.6       340334.34
      1911941.08       340239.82      1911013.74       338834.59
      1910704.51       338520.18      1910349.87        338267.3
#Sta/Elev= 30
 -2594.9  169.19 -2034.5  166.42 -1693.3  167.28 -1099.9  166.09  -474.9   168.6
   171.6  166.48   309.5  167.41   411.2   167.2   881.2  168.08  1965.5  166.96
  2057.1  167.49  3232.9  167.58  3656.6  168.03  3700.1  166.62  3987.5  168.05
  4637.9  166.33    4958  168.68 4985.54  167.03  4991.2  162.82  4993.5  159.07
    5006  159.51 5016.07  167.04  5046.8  168.87  5235.8  166.39  5315.8  168.09
  5577.9  166.17  5652.9  168.36    6076   167.9  6331.5  172.56  6597.3  173.95
#Mann= 13 ,-1 , 0
 -2594.9     .05       0 -2034.5     .11       0 -1693.3     .05       0
   171.6     .09       0   309.5     .05       0   411.2      .1       0
   881.2     .11       0  1965.5     .11       0  2057.1     .12       0
  3232.9     .11       0  3656.6      .1       0 4985.54     .08       0
 5016.07      .1       0
#XS Ineff= 3 ,-1
 -2594.9  3604.4  170.94  3604.4 4931.56  165.13    5019    6160  165.13
Permanent Ineff=
       F       F       F
Bank Sta=4985.54,5016.07
XS Rating Curve= 0 ,0
Exp/Cntr=0.5,0.3

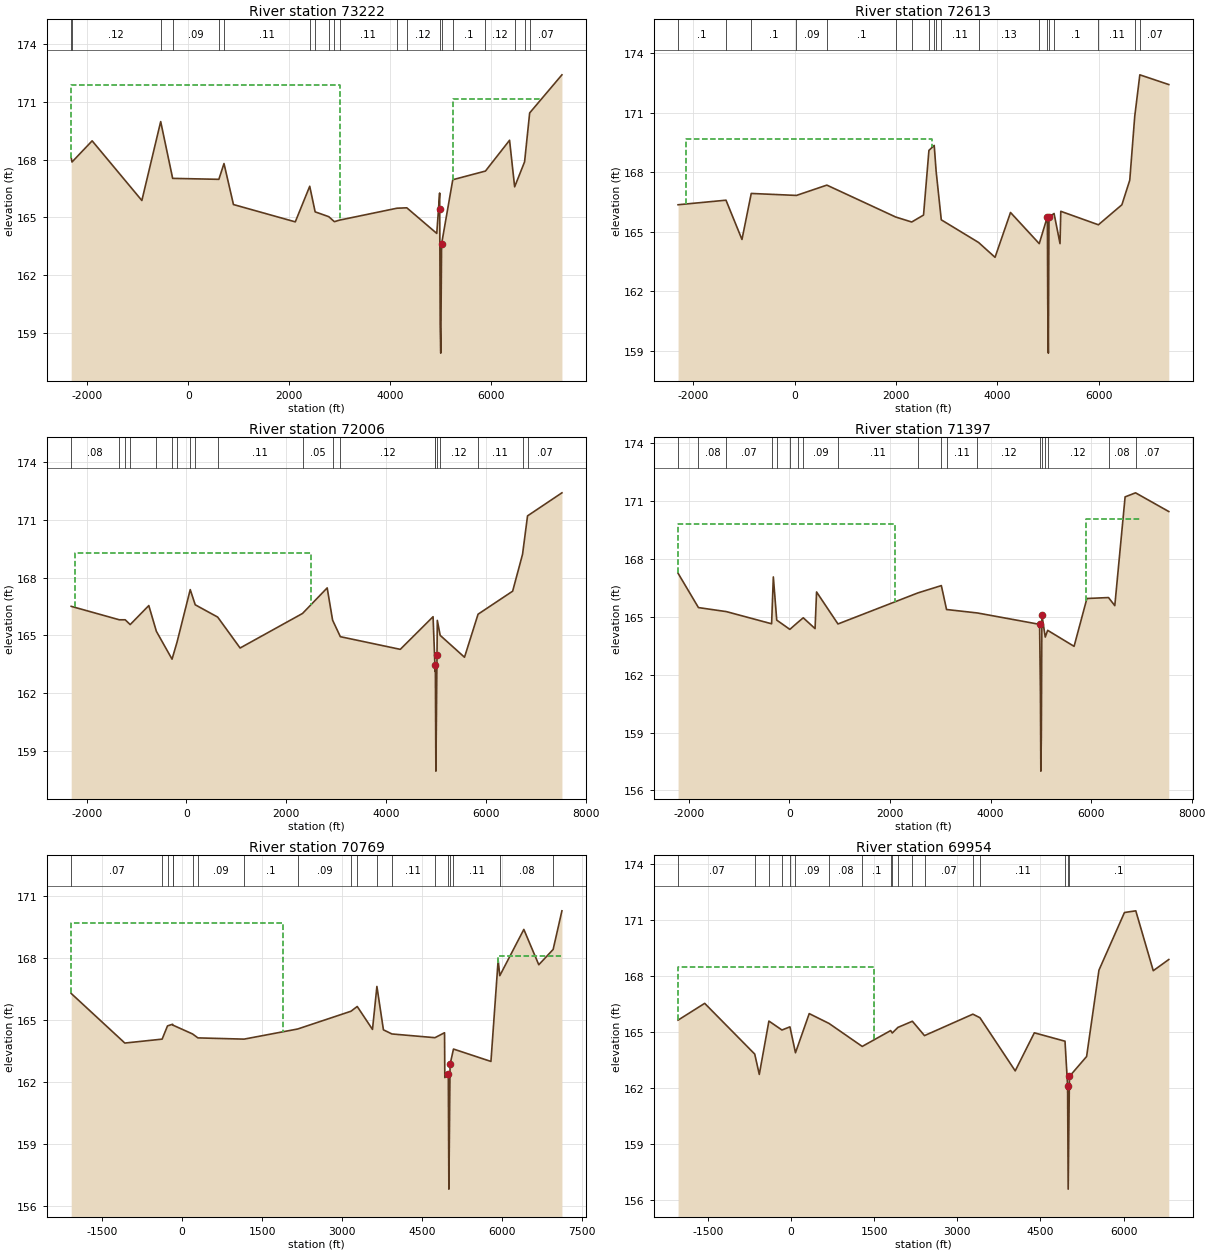
Type RM Length L Ch R = 1 ,73222   ,631,609,608
BEGIN DESCRIPTION:
73222
DELETED LIDAR ARTIFACTS FROM IMMEDIATE OVERBANKS
END DESCRIPTION:
XS GIS Cut Line= 3
      1917187.13        344176.4      1912774.88       338347.48
      1911337.38       336409.97
#Sta/Elev= 30
 -2322.5  168.09 -2306.8  167.87 -1907.5  168.97  -922.5  165.87  -549.4  169.97
  -312.2  167.02   603.2  166.97   704.9  167.79   892.5  165.66  2117.5  164.76
  2403.6  166.61    2511  165.28  2780.8  165.03  2892.3  164.77  2993.6  164.85
  4133.1  165.47  4327.3  165.49  4920.7  164.16  4977.8  166.26 4979.03  165.41
    4989  159.32  4999.7  157.94    5016  163.61  5238.1  166.95  5885.2   167.4
  6363.1     169  6463.7  166.58  6660.8  167.88  6761.4  170.42  7400.6   172.4
#Mann= 20 ,-1 , 0
 -2322.5     .05       0 -2306.8     .12       0  -549.4      .1       0
  -312.2     .09       0   603.2     .05       0   704.9     .11       0
  2403.6     .05       0    2511      .1       0  2780.8     .12       0
  2892.3     .05       0  2993.6     .11       0  4133.1     .13       0
  4327.3     .12       0  4977.8     .08       0    5016     .12       0
  5238.1      .1       0  5885.2     .12       0  6463.7     .09       0
  6660.8     .05       0  6761.4     .07       0
#XS Ineff= 2 ,-1
 -2322.5    3000  171.88 5243.86 7013.23  171.15
Permanent Ineff=
       F       F
Bank Sta=4979.03,5016
XS Rating Curve= 0 ,0
Exp/Cntr=0.3,0.1

Type RM Length L Ch R = 1 ,72613   ,660,607,603
BEGIN DESCRIPTION:
72613
END DESCRIPTION:
XS GIS Cut Line= 3
       1917810.6       343648.72      1913261.42       337982.86
      1911825.64       336047.68
#Sta/Elev= 30
 -2297.8  166.35 -1352.9  166.58 -1037.8   164.6  -854.9  166.92    35.5  166.82
     636  167.34  1994.8  165.73  2309.1  165.48  2542.2  165.83  2648.6  169.09
  2752.6  169.34  2790.8  168.03    2892  165.59  3626.6  164.45  3952.2   163.7
  4257.2  165.96  4823.6  164.39 4984.41  165.75  4991.2  161.39  5003.2  158.87
 5016.12  165.73  5115.6  165.91  5233.4  164.39  5248.4  166.02    5990  165.34
  6453.4  166.35  6608.4  167.59  6706.2   170.8  6806.9   172.9    7378  172.41
#Mann= 19 ,-1 , 0
 -2297.8      .1       0 -1352.9     .12       0  -854.9      .1       0
    35.5     .09       0     636      .1       0  1994.8     .05       0
  2309.1     .11       0  2648.6     .05       0  2752.6     .07       0
  2790.8     .05       0    2892     .11       0  3626.6     .13       0
  4823.6     .12       0 4984.41     .08       0 5016.12     .12       0
  5115.6      .1       0    5990     .11       0  6706.2     .05       0
  6806.9     .07       0
#XS Ineff= 1 ,-1
-2141.03 2716.74169.6561
Permanent Ineff=
       F
Bank Sta=4984.41,5016.12
XS Rating Curve= 0 ,0
Exp/Cntr=0.3,0.1

Type RM Length L Ch R = 1 ,72006   ,625,609,614
BEGIN DESCRIPTION:
72006
END DESCRIPTION:
XS GIS Cut Line= 3
      1918467.44       343125.65      1913753.46       337621.52
      1912099.08       335632.08
#Sta/Elev= 30
 -2308.7  166.51 -1345.1  165.81 -1226.7  165.81 -1126.5  165.56  -753.7  166.55
  -601.9  165.21  -287.9  163.76  -187.3  164.65    76.7  167.38     177  166.59
     627  165.95  1076.3  164.34  2327.7  166.14  2821.3  167.47  2929.8  165.79
  3084.9  164.93  4286.3  164.27  4943.2  165.97  4985.4  163.12  4989.1  163.48
  4999.6  157.93  5022.2  163.97  5028.2  165.78  5085.5     165  5573.2  163.86
  5844.9   166.1  6538.2   167.3  6736.4  169.22  6836.5  171.22  7525.6  172.42
#Mann= 20 ,-1 , 0
 -2308.7     .08       0 -1345.1     .09       0 -1226.7     .05       0
 -1126.5     .12       0  -601.9      .1       0  -287.9     .05       0
  -187.3      .1       0    76.7     .05       0     177     .09       0
     627     .11       0  2327.7     .05       0  2929.8     .11       0
  3084.9     .12       0  4985.4     .05       0  4989.1     .08       0
  5022.2     .05       0  5085.5     .12       0  5844.9     .11       0
  6736.4     .05       0  6836.5     .07       0
#XS Ineff= 1 ,-1
-2227.14    2500  169.28
Permanent Ineff=
       F
Bank Sta=4989.1,5022.2
XS Rating Curve= 0 ,0
Exp/Cntr=0.3,0.1

Type RM Length L Ch R = 1 ,71397   ,611,628,658
BEGIN DESCRIPTION:
71397
END DESCRIPTION:
XS GIS Cut Line= 3
      1919046.61       342541.21      1914212.38       337222.48
      1912566.53       335243.29
#Sta/Elev= 30
 -2216.4  167.26 -1811.1  165.48 -1254.4  165.27  -355.7  164.64  -321.4  167.07
  -253.7  164.83       7  164.35   173.2  164.73   273.4  164.95   508.6  164.39
   538.6  166.29   964.4  164.63  2553.6  166.24  3020.6  166.62    3124  165.38
  3739.8   165.2 4975.08  164.61  4991.4  161.07  4999.6     157  5009.6  158.75
    5021  165.09  5087.6  163.95  5135.7   164.3    5661  163.47    5916  165.95
    6346     166    6471  165.58    6676  171.22  6883.6  171.43  7545.1  170.46
#Mann= 19 ,-1 , 0
 -2216.4     .07       0 -1811.1     .08       0 -1254.4     .07       0
  -355.7     .05       0  -253.7      .1       0       7     .09       0
   173.2     .05       0   273.4     .09       0   964.4     .11       0
  2553.6     .09       0  3020.6     .05       0    3124     .11       0
  3739.8     .12       0 4975.08     .08       0    5021     .05       0
  5087.6     .11       0  5135.7     .12       0    6346     .08       0
  6883.6     .07       0
#XS Ineff= 2 ,-1
  5901.7    7000  170.09 -2216.4    2100  169.82
Permanent Ineff=
       F       F
Bank Sta=4975.08,5021
XS Rating Curve= 0 ,0
Exp/Cntr=0.3,0.1

Type RM Length L Ch R = 1 ,70769   ,805,815,779
BEGIN DESCRIPTION:
70769 LiDAR artifacts removed from left overbank
END DESCRIPTION:
XS GIS Cut Line= 6
      1919245.94       342176.88      1917847.07       340899.65
       1916861.8       339890.05      1916399.57       339306.18
      1914100.59       336046.26      1913249.14       335267.79
#Sta/Elev= 30
 -2076.4  166.29 -1071.4  163.89  -372.8  164.08  -272.2  164.72  -176.8   164.8
  -173.1  164.76   197.8  164.33   297.8  164.14  1161.6  164.08  2166.6  164.57
  3165.5  165.43  3282.6  165.66  3568.5  164.55  3651.1  166.63  3773.5  164.53
  3932.7  164.33  4738.5  164.15  4918.5  164.39  4923.5  162.22  4989.1  162.37
  4999.6  156.82  5022.2  162.86  5086.1   163.6  5787.7     163  5922.7   167.9
  5953.4  167.15    6404  169.39    6684  167.68    6953  168.42  7117.7  170.29
#Mann= 19 ,-1 , 0
 -2076.4     .07       0  -372.8     .05       0  -272.2      .1       0
  -176.8     .11       0  -173.1     .09       0   197.8     .05       0
   297.8     .09       0  1161.6      .1       0  2166.6     .09       0
  3165.5     .05       0  3282.6     .11       0  3651.1     .05       0
  3932.7     .11       0  4738.5     .12       0  4989.1     .08       0
  5022.2     .05       0  5086.1     .11       0  5953.4     .08       0
    6953     .06       0
#XS Ineff= 2 ,-1
 -2076.4    1900 169.711 5929.14 7094.86  168.11
Permanent Ineff=
       F       F
Bank Sta=4989.1,5022.2
XS Rating Curve= 0 ,0
Exp/Cntr=0.3,0.1

Type RM Length L Ch R = 1 ,69954   ,847,832,782
BEGIN DESCRIPTION:
69954 - LiDAR artifacts removed from left overbank
END DESCRIPTION:
XS GIS Cut Line= 6
      1919270.23       341775.44      1918260.64       340948.31
      1917153.73       339853.56      1915198.28        336198.6
      1914453.35       335389.41      1913881.64       334927.18
#Sta/Elev= 30
 -2037.4  165.65 -1557.4  166.55  -654.6  163.83  -572.2  162.74  -398.9   165.6
  -163.2  165.12   -19.5  165.29    80.5   163.9   328.5     166   687.1  165.47
  1284.6  164.24  1797.4  165.09  1826.7  164.96  1928.3  165.26  2189.3  165.59
  2407.9  164.82  3280.6  165.97  3407.8  165.78  4044.2  162.93  4389.2  164.97
  4942.5  164.52  4989.1  162.14  4999.6  156.59  5022.2  162.63    5332   163.7
  5554.9  168.33  6014.9  171.42  6219.4  171.51  6534.4   168.3  6814.6   168.9
#Mann= 18 ,-1 , 0
 -2037.4     .07       0  -654.6     .08       0  -398.9     .11       0
  -163.2     .09       0   -19.5     .05       0    80.5     .09       0
   687.1     .08       0  1284.6      .1       0  1797.4     .07       0
  1826.7     .05       0  1928.3     .08       0  2189.3     .05       0
  2407.9     .07       0  3280.6     .05       0  3407.8     .11       0
  4942.5     .09       0  4989.1     .08       0  5022.2      .1       0
#XS Ineff= 1 ,-1
-2094.47    1500  168.51
Permanent Ineff=
       F
Bank Sta=4989.1,5022.2
XS Rating Curve= 0 ,0
Exp/Cntr=0.5,0.3