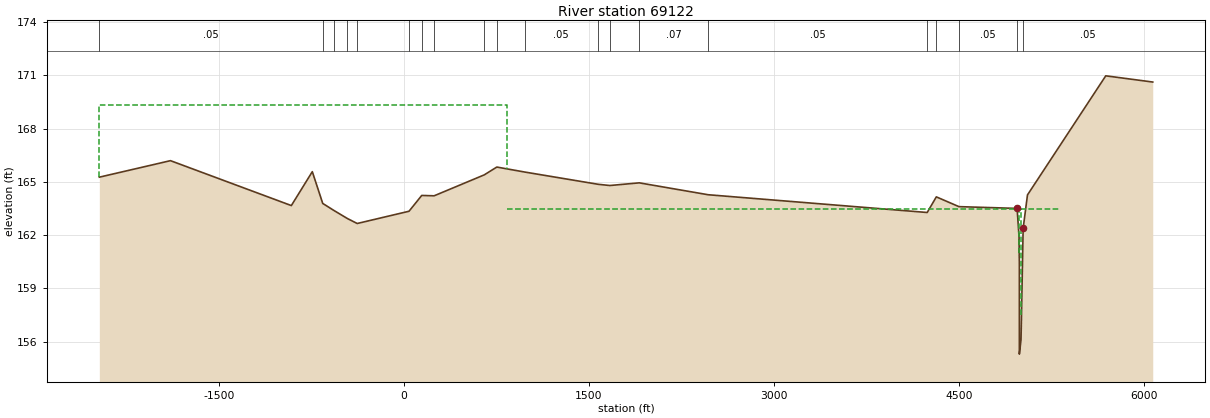
HEC-RAS study BackSwamp.prj: Back Swamp Detailed Study

--- BackSwamp.g01 (geometry) --- (continued)

Type RM Length L Ch R = 1 ,69122   ,93,76,82
BEGIN DESCRIPTION:
69122
END DESCRIPTION:
XS GIS Cut Line= 6
      1919486.42       341550.95      1917515.77       339922.69
       1916920.6       338804.51      1916101.01       336226.24
      1915606.85       335466.15      1914673.86       334906.94
#Sta/Elev= 30
   -2468  165.27 -1891.2   166.2  -911.2  163.67  -741.2  165.58  -656.6  163.79
  -562.7  163.38  -456.7  162.94  -377.1  162.66    42.9  163.35     146  164.24
   246.6  164.22     653   165.4   754.8  165.84   980.3  165.56    1575  164.87
  1670.7   164.8  1910.2  164.95  2468.5  164.28  4244.2  163.28  4318.4  164.16
  4501.5  163.61  4973.4  163.51  4989.1  161.89  4991.4  160.41  4991.5   155.3
    5005   156.1  5022.2  162.38  5057.4  164.27  5692.1  170.98    6073  170.63
#Mann= 20 ,-1 , 0
   -2468     .05       0  -656.6     .07       0  -562.7     .05       0
  -456.7     .07       0  -377.1     .09       0    42.9     .08       0
     146     .05       0   246.6     .08       0     653     .05       0
   754.8     .08       0   980.3     .05       0    1575     .07       0
  1670.7     .05       0  1910.2     .07       0  2468.5     .05       0
  4244.2     .07       0  4318.4     .09       0  4501.5     .05       0
  4973.4     .08       0  5022.2     .05       0
#XS Ineff= 3 ,-1
   -2468  836.96  169.32  5008.8    5314  163.49  836.96 4990.71163.4852
Permanent Ineff=
       F       F       F
Bank Sta=4973.4,5022.2
XS Rating Curve= 0 ,0
Exp/Cntr=0.5,0.3