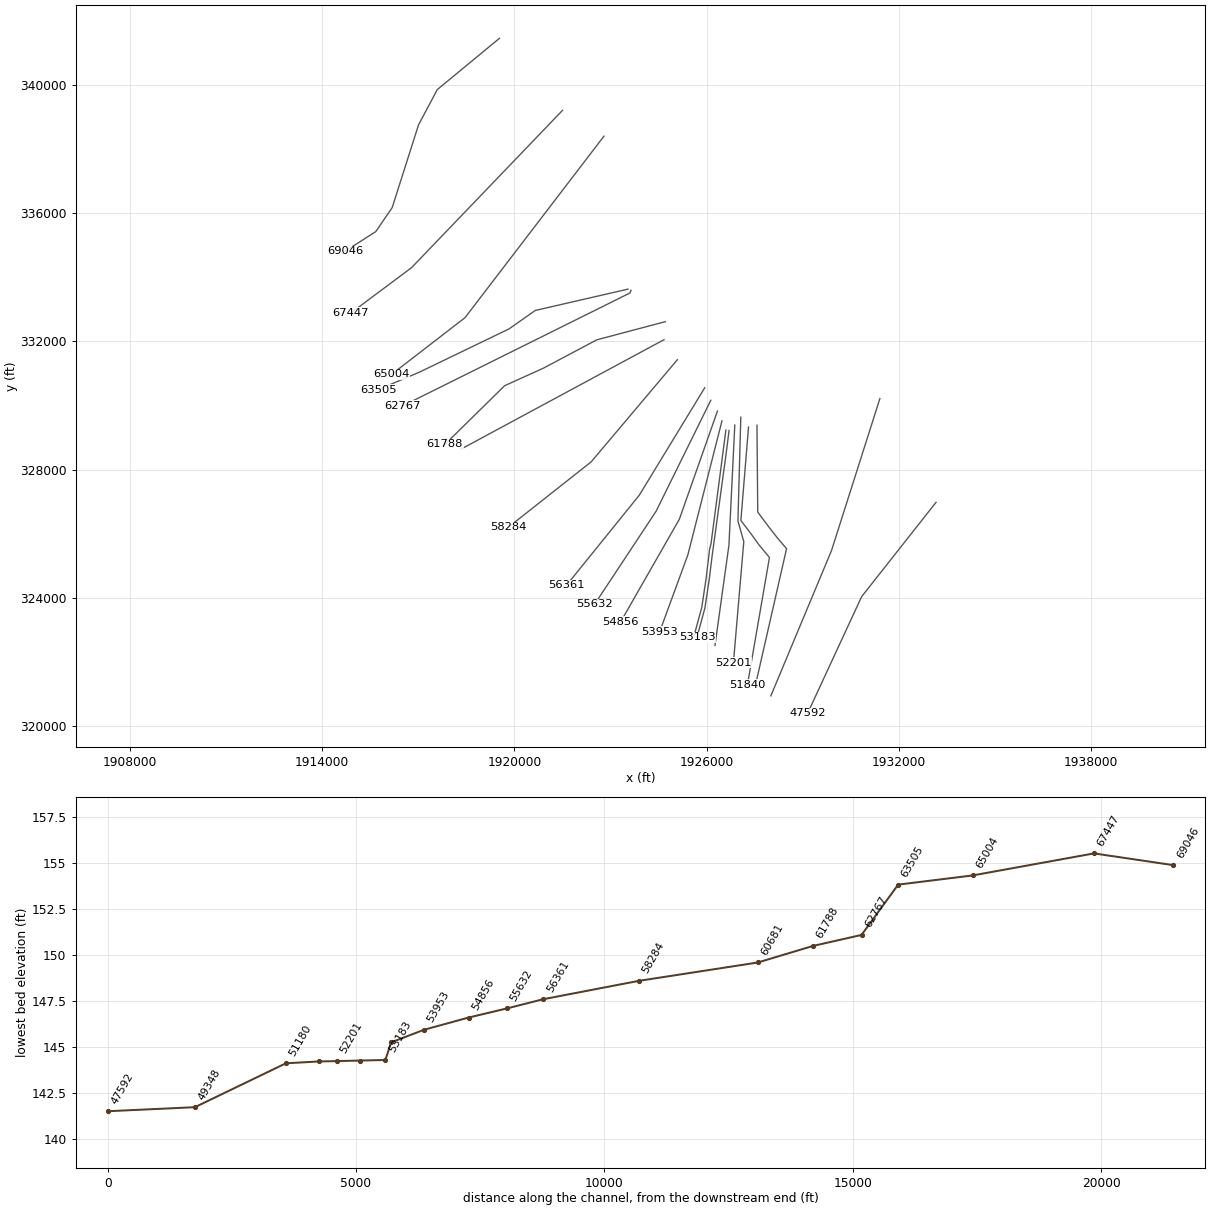
HEC-RAS study BackSwamp.prj: Back Swamp Detailed Study

--- BackSwamp.g01 (geometry) --- (continued)

Type RM Length L Ch R = 2 ,69096   ,,,
BEGIN DESCRIPTION:
Cabinet Shop Rd (SR 1166),  ID: R_BAS_13
END DESCRIPTION:
Bridge Culvert--1,0,-1,-1, 0
Deck Dist Width WeirC Skew NumUp NumDn MinLoCord MaxHiCord MaxSubmerge Is_Ogee
2,48,3,0, 56, 56, 162.98, , 0.95, 0, 0,0,,
 -2457.1 -2387.4 -2332.4 -1792.4 -1607.4 -1427.4 -1342.4 -1192.4 -1127.4 -1077.4
  -992.4  -907.4  -732.4  -632.4  -522.9  -502.9  -362.9  -172.9    -3.1   148.6
   443.2   488.2   733.2   828.2  1083.2  1233.2    1366    1406    1551    1611
    1762    1942    2372  2743.9  3182.2  3369.1  3514.1  3699.1  3944.1  4101.2
  4106.2  4126.2  4196.2  4306.2  4346.2  4490.7  4803.8  5081.6  5265.5  5371.8
  5521.8  5676.8  5716.8  5836.2  6011.2  6078.9
  165.53  165.35  165.32  165.64  165.52  165.17  165.13  165.36  165.65  165.78
  165.73  165.56  164.75  164.12  163.06  162.98  162.92   163.5  164.42  164.82
   164.7  164.78  166.27  166.27  165.07  164.78  164.29  164.25  165.01  165.14
  165.25  165.22  164.87  164.46  164.32  164.38  164.97  165.08  164.51  163.94
  163.66  163.55  163.48   163.7     164  164.29  164.05  165.18   166.3  167.06
   168.7  170.72  170.99  171.25  170.95  170.76
  135.87  135.87  135.87  135.87  135.87  135.87  135.87  135.87  135.87  135.87
  135.87  135.87  135.87  135.87  135.87  135.87  135.87  135.87  135.87  135.87
  135.87  135.87  135.87  135.87  135.87  135.87  135.87  135.87  135.87  135.87
  135.87  135.87  135.87  135.87  135.87  135.87  135.87  135.87  135.87  135.87
  135.87  135.87  135.87  135.87  135.87  135.87  135.87  135.87  135.87  135.87
  135.87  135.87  135.87  135.87  135.87  135.87
 -2457.1 -2387.4 -2332.4 -1792.4 -1607.4 -1427.4 -1342.4 -1192.4 -1127.4 -1077.4
  -992.4  -907.4  -732.4  -632.4  -522.9  -502.9  -362.9  -172.9    -3.1   148.6
   443.2   488.2   733.2   828.2  1083.2  1233.2    1366    1406    1551    1611
    1762    1942    2372  2743.9  3182.2  3369.1  3514.1  3699.1  3944.1  4101.2
  4106.2  4126.2  4196.2  4306.2  4346.2  4490.7  4803.8  5081.6  5265.5  5371.8
  5521.8  5676.8  5716.8  5836.2  6011.2  6078.9
  165.53  165.35  165.32  165.64  165.52  165.17  165.13  165.36  165.65  165.78
  165.73  165.56  164.75  164.12  163.06  162.98  162.92   163.5  164.42  164.82
   164.7  164.78  166.27  166.27  165.07  164.78  164.29  164.25  165.01  165.14
  165.25  165.22  164.87  164.46  164.32  164.38  164.97  165.08  164.51  163.94
  163.66  163.55  163.48   163.7     164  164.29  164.05  165.18   166.3  167.06
   168.7  170.72  170.99  171.25  170.95  170.76
   134.9   134.9   134.9   134.9   134.9   134.9   134.9   134.9   134.9   134.9
   134.9   134.9   134.9   134.9   134.9   134.9   134.9   134.9   134.9   134.9
   134.9   134.9   134.9   134.9   134.9   134.9   134.9   134.9   134.9   134.9
   134.9   134.9   134.9   134.9   134.9   134.9   134.9   134.9   134.9   134.9
   134.9   134.9   134.9   134.9   134.9   134.9   134.9   134.9   134.9   134.9
   134.9   134.9   134.9   134.9   134.9   134.9
Culvert=1,6,,48,0.024,0.9,1,2,3,155.51,4994.5,154.9,4994.5,Culvert #1  , 0 ,2
Culvert Bottom n=0.024
Culvert=1,6,,48,0.024,0.9,1,2,3,156.06,5003.8,155.73,5003.8,Culvert #2  , 0 ,2
Culvert Bottom n=0.024
BC Design=,, 0 ,, 0 ,,,,,,
BC HTab HWMax=171.27
BC Use User HTab Curves=0
BC User HTab FreeFlow(D)= 0

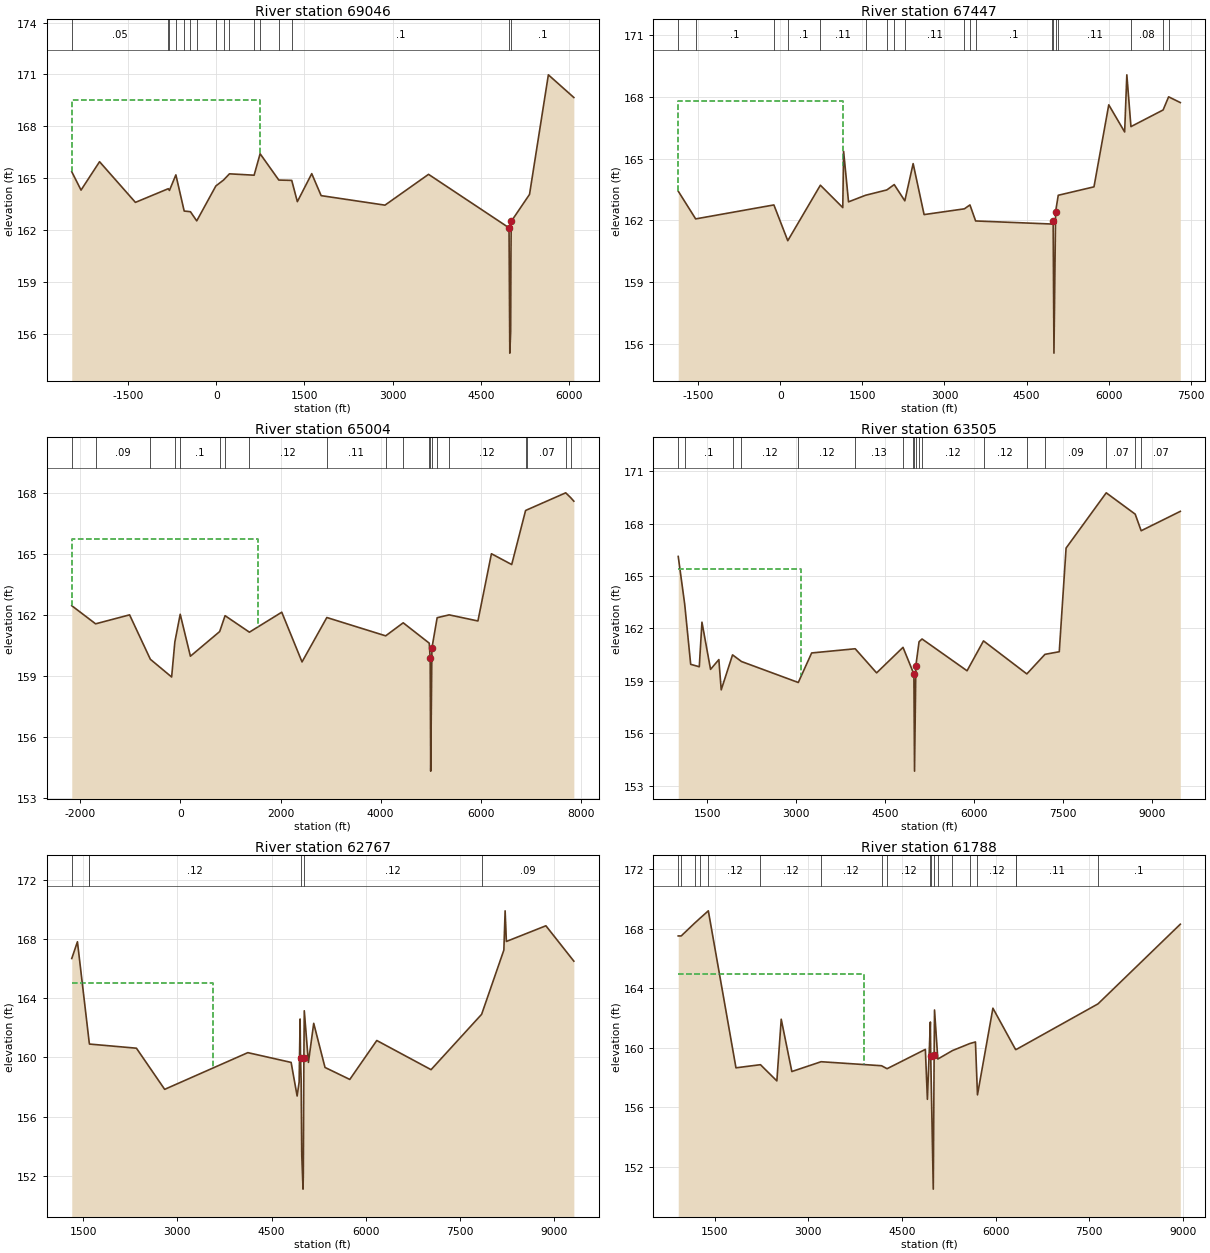
Type RM Length L Ch R = 1 ,69046   ,1645,1599,1594
BEGIN DESCRIPTION:
69046 - LiDAR artifacts removed from left overbank
END DESCRIPTION:
XS GIS Cut Line= 6
      1919536.43       341464.16      1917598.22       339865.43
      1917012.19       338763.91      1916190.78       336181.36
      1915676.53       335428.11      1914718.57       334817.49
#Sta/Elev= 30
 -2456.3  165.38 -2298.7  164.32 -1983.7  165.96 -1373.7  163.61  -814.9   164.4
  -795.1   164.3  -685.8   165.2  -544.4  163.11  -437.9  163.07    -331  162.54
    -5.5  164.56   124.7   164.9   225.3  165.26     645  165.18   746.9  166.42
    1065   164.9  1284.8  164.88  1380.2  163.65  1624.9  165.27  1784.9     164
  2870.6  163.45  3611.4  165.23  4980.4  162.14  4993.5   154.9  5008.3  156.15
  5013.2  160.68  5017.7  162.51  5328.8  164.07  5649.4  170.98  6082.6  169.67
#Mann= 16 ,-1 , 0
 -2456.3     .05       0  -814.9     .09       0  -795.1     .05       0
  -685.8     .07       0  -544.4     .05       0  -437.9     .07       0
    -331     .09       0    -5.5     .08       0   124.7     .05       0
   225.3     .08       0     645     .05       0   746.9     .08       0
    1065     .09       0  1284.8      .1       0  4980.4     .08       0
  5017.7      .1       0
#XS Ineff= 3 ,-1
 -2456.3     750  169.55     750 4903.53161.7026  5094.8 5351.78   161.7
Permanent Ineff=
       F       F       F
Bank Sta=4980.4,5017.7
XS Rating Curve= 0 ,0
Exp/Cntr=0.5,0.3

Type RM Length L Ch R = 1 ,67447   ,2320,2443,2417
BEGIN DESCRIPTION:
67447
END DESCRIPTION:
XS GIS Cut Line= 3
      1921504.02       339215.54      1916795.72       334305.82
      1914899.91       332889.17
#Sta/Elev= 30
 -1861.9  163.42 -1543.6  162.07  -114.9  162.75   138.5  161.01   733.9  163.71
  1143.1  162.62  1158.1  165.36  1248.1   162.9  1558.5  163.22    1948  163.48
  2082.4  163.74    2276  162.95  2428.1  164.76  2628.1  162.28  3363.7  162.56
  3465.4  162.75  3569.2  161.97  4970.4  161.82  4984.9  161.99  4999.6  155.54
    5030  162.43  5078.2  163.22  5730.6  163.63  6000.6  167.62  6290.6   166.3
  6330.6  169.08  6405.6  166.56  6993.1  167.37  7093.8  168.01  7307.2  167.73
#Mann= 19 ,-1 , 0
 -1861.9     .05       0 -1543.6      .1       0  -114.9     .05       0
   138.5      .1       0   733.9     .11       0  1558.5     .05       0
    1948     .09       0  2082.4     .08       0    2276     .11       0
  3363.7     .05       0  3465.4     .07       0  3569.2      .1       0
  4970.4     .05       0  4984.9     .08       0    5030     .05       0
  5078.2     .11       0  6405.6     .08       0  6993.1     .05       0
  7093.8     .07       0
#XS Ineff= 2 ,-1
 -1861.9 1154.29   167.8 6011.43 7302.86  167.55
Permanent Ineff=
       F       F
Bank Sta=4984.9,5030
XS Rating Curve= 0 ,0
Exp/Cntr=0.3,0.1

Type RM Length L Ch R = 1 ,65004   ,1562,1499,1472
BEGIN DESCRIPTION:
65004-LiDAR artifacts removed from left overbank
END DESCRIPTION:
XS GIS Cut Line= 3
       1922796.8       338409.39      1918462.38       332743.32
      1916170.69       330972.46
#Sta/Elev= 30
   -2171  162.46 -1694.9  161.57   -1016  162.01    -601  159.83    -176  158.96
  -111.8  160.68    -4.6  162.04     199  159.98   783.6  161.19   891.7  161.97
  1377.6  161.16    2024  162.14    2429   159.7  2924.5  161.88  4099.7  160.98
    4450  161.62  4970.4  160.62  4989.1  159.89  4999.6  154.34 5023.76  160.38
  5128.4  161.87  5368.1  162.01  5942.8  161.71  6212.8  165.01  6617.8  164.48
  6894.7  167.13  6928.2  167.17  7696.4     168  7797.4  167.76    7859  167.59
#Mann= 20 ,-1 , 0
   -2171     .07       0 -1694.9     .09       0    -601      .1       0
  -111.8     .05       0    -4.6      .1       0   783.6     .05       0
   891.7      .1       0  1377.6     .12       0  2924.5     .11       0
  4099.7     .12       0    4450     .11       0  4970.4     .05       0
  4989.1     .08       0 5023.76     .05       0  5128.4     .11       0
  5368.1     .12       0  6894.7     .09       0  6928.2     .07       0
  7696.4     .05       0  7797.4     .07       0
#XS Ineff= 1 ,-1
   -2171    1549  165.71
Permanent Ineff=
       F
Bank Sta=4989.1,5023.76
XS Rating Curve= 0 ,0
Exp/Cntr=0.3,0.1

Type RM Length L Ch R = 1 ,63505   ,749,738,757
BEGIN DESCRIPTION:
63505
END DESCRIPTION:
XS GIS Cut Line= 5
      1923547.06       333634.49      1920652.49       332967.68
      1919834.12       332391.79      1917034.55       331040.01
      1915757.44       330497.42
#Sta/Elev= 30
  1014.5  166.12  1123.5  163.39  1224.5  159.95  1369.5  159.81  1414.5  162.36
  1559.5  159.66  1699.5  160.22  1739.5  158.49  1930.5  160.49  2081.3  160.11
  3039.1  158.91  3264.5   160.6  3999.2  160.84  4359.9  159.46  4805.4  160.92
  4989.1  159.39  4999.6  153.84  5022.2  159.88  5076.1  161.24  5126.3   161.4
  5885.6  159.58  6162.8  161.29  6893.7   159.4  7199.3  160.52  7440.6  160.67
  7555.6   166.6  8232.7  169.76  8721.2  168.54  8821.9  167.59    9482   168.7
#Mann= 18 ,-1 , 0
  1014.5     .08       0  1123.5      .1       0  1930.5     .12       0
  2081.3     .12       0  3039.1     .12       0  3999.2     .13       0
  4805.4     .12       0  4967.9     .05       0  4989.1     .08       0
  5022.2     .05       0  5076.1     .12       0  5126.3     .12       0
  6162.8     .12       0  6893.7     .12       0  7199.3     .09       0
  8232.7     .07       0  8721.2     .05       0  8821.9     .07       0
#XS Ineff= 2 , 0
          3091.6  165.42
Permanent Ineff=
       F       F
Bank Sta=4989.1,5022.2
XS Rating Curve= 0 ,0
Exp/Cntr=0.3,0.1

Type RM Length L Ch R = 1 ,62767   ,943,979,948
BEGIN DESCRIPTION:
62767
END DESCRIPTION:
XS GIS Cut Line= 3
       1923640.7       333598.47      1923608.22       333514.15
      1916524.86        329993.3
#Sta/Elev= 30
  1316.7  166.68  1407.1  167.81  1593.9  161.03  1598.7   160.9  2347.1  160.62
  2797.1  157.84  4122.1  160.32  4812.1  159.66  4907.7  157.39  4939.7  158.33
  4955.3  162.59 4961.92  159.96  4972.1  158.43  4981.5  153.43  5001.9   151.1
  5006.2     152 5015.41  159.96  5021.7  163.15  5087.6  159.66  5172.1   162.3
  5352.1  159.32  5747.1  158.51  6177.1  161.14  7042.1  159.17  7847.9  162.91
  8202.1  167.25  8222.1   169.9  8242.1  167.83  8872.1  168.89  9317.2   166.5
#Mann= 6 ,-1 , 0
  1316.7     .08       0  1593.9      .1       0  1598.7     .12       0
 4961.92     .08       0 5015.41     .12       0  7847.9     .09       0
#XS Ineff= 2 , 0
         3562.34  165.04
Permanent Ineff=
       F       F
Bank Sta=4961.92,5015.41
XS Rating Curve= 0 ,0
Exp/Cntr=0.3,0.1

Type RM Length L Ch R = 1 ,61788   ,1093,1107,1071
BEGIN DESCRIPTION:
61788 DELETED LIDAR ARTIFACTS IN LEFT OVERBANK
END DESCRIPTION:
XS GIS Cut Line= 5
      1924713.99        332619.1      1922573.72       332051.48
      1920906.77       331166.33      1919697.72       330618.66
      1917833.65       328784.89
#Sta/Elev= 30
   915.8  167.53   963.3  167.53  1180.8   168.4  1267.3  168.73    1398  169.22
  1840.8  158.66  2232.9  158.87  2495.8  157.78  2565.8  161.93  2735.8  158.41
    3205  159.07  4173.5   158.8  4261.8   158.6  4875.1   159.9  4907.7  156.54
  4955.3  161.74    4961  159.45  5001.9   150.5 5015.52  159.49  5021.7  162.55
  5074.5  159.25  5309.5  159.82  5585.7  160.29  5677.4   160.4  5709.9  156.84
  5957.4  162.67  6320.3  159.89  6334.2   159.9  7640.5  162.96  8959.6  168.32
#Mann= 19 ,-1 , 0
   915.8     .07       0   963.3     .05       0  1180.8     .09       0
  1267.3     .11       0    1398     .12       0  2232.9     .12       0
    3205     .12       0  4173.5     .13       0  4261.8     .12       0
  4955.3     .08       0    4961     .05       0 5015.52     .05       0
  5074.5     .12       0  5309.5     .12       0  5585.7     .05       0
  5709.9     .12       0  6320.3     .12       0  6334.2     .11       0
  7640.5      .1       0
#XS Ineff= 2 , 0
         3893.13  164.96
Permanent Ineff=
       F       F
Bank Sta=4961,5015.52
XS Rating Curve= 0 ,0
Exp/Cntr=0.3,0.1

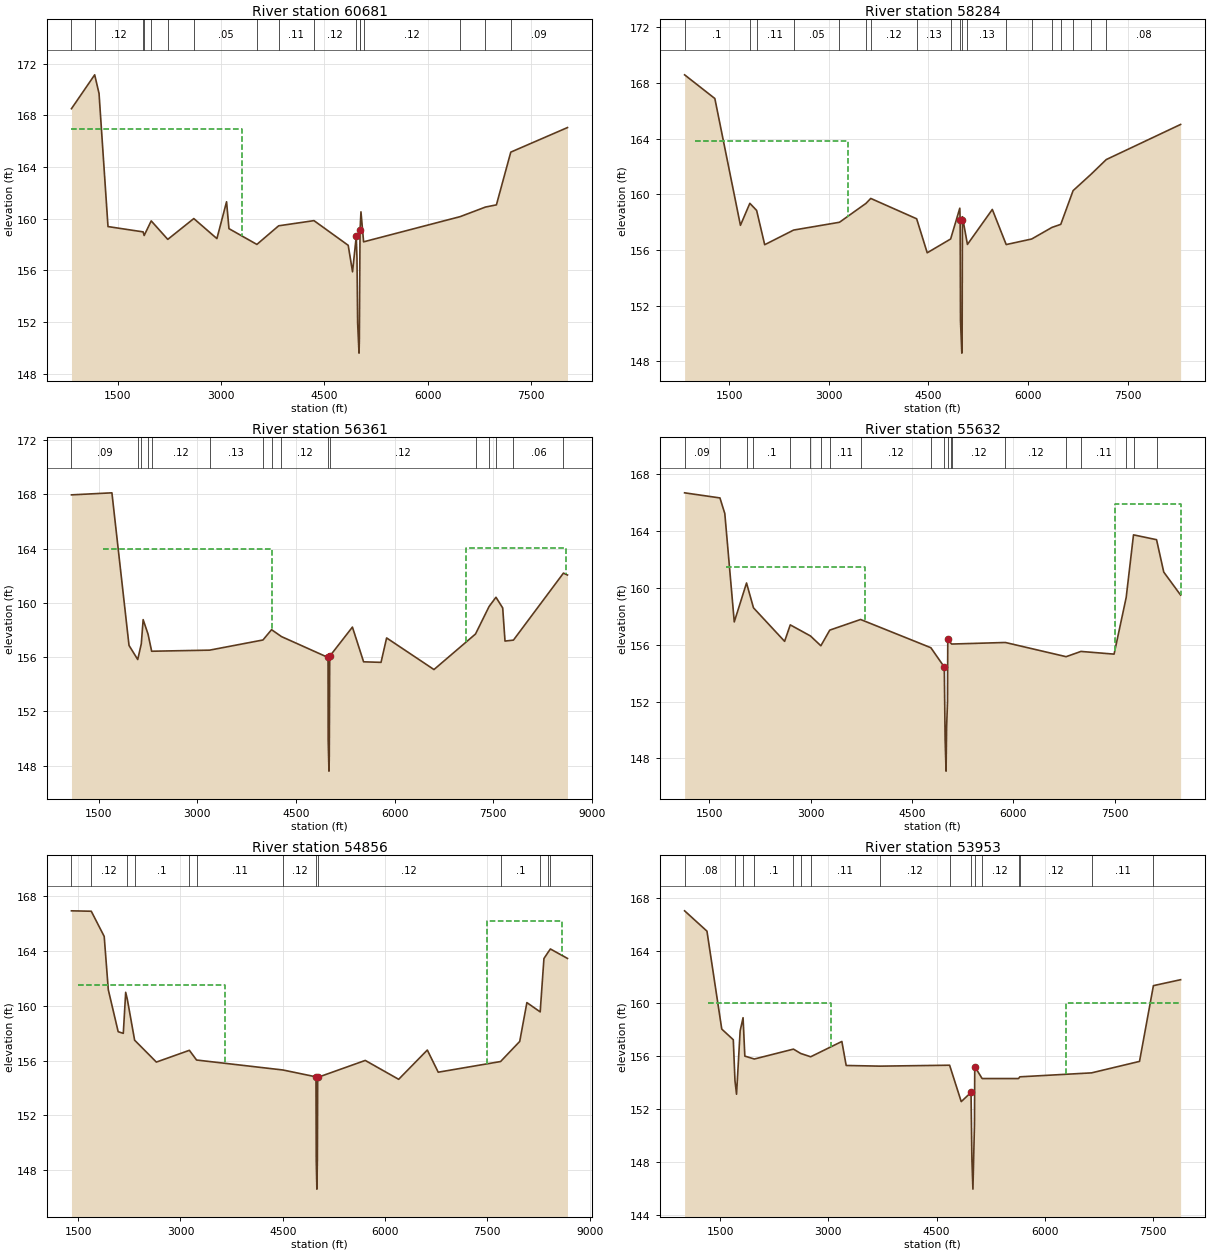
Type RM Length L Ch R = 1 ,60681   ,2242,2397,2343
BEGIN DESCRIPTION:
60681
END DESCRIPTION:
XS GIS Cut Line= 2
      1924670.69        332055.8      1918337.41       328639.16
#Sta/Elev= 30
   829.8  168.51  1166.6  171.13  1229.8  169.69  1359.8  159.39  1869.6  158.98
  1884.6   158.7  1986.7  159.83  2227.1   158.4  2604.8  160.01  2939.8  158.46
  3079.8  161.31  3114.8  159.23  3519.8  158.01  3835.5  159.45  4348.2  159.85
  4844.8  157.94  4907.7  155.89  4961.3  158.63  4972.1  156.93  4981.5  151.93
  5001.9   149.6  5006.2   150.5  5016.4  159.09  5029.8  160.53  5068.1  158.21
  6469.3  160.16    6836   160.9  6994.8  161.07  7203.4  165.15  8025.9  167.05
#Mann= 17 ,-1 , 0
   829.8     .08       0  1166.6     .12       0  1869.6     .11       0
  1884.6     .05       0  1986.7     .12       0  2227.1     .13       0
  2604.8     .05       0  3519.8     .13       0  3835.5     .11       0
  4348.2     .12       0  4961.3     .08       0  5016.4     .05       0
  5016.4     .05       0  5068.1     .12       0  6469.3     .11       0
    6836     .05       0  7203.4     .09       0
#XS Ineff= 2 , 0
         3297.71  166.96
Permanent Ineff=
       F       F
Bank Sta=4961.3,5016.4
XS Rating Curve= 0 ,0
Exp/Cntr=0.3,0.1

Type RM Length L Ch R = 1 ,58284   ,1874,1923,1935
BEGIN DESCRIPTION:
58284
END DESCRIPTION:
XS GIS Cut Line= 3
      1925087.39       331430.83      1922399.88       328243.32
      1919816.55       326201.65
#Sta/Elev= 30
   831.1  168.57  1286.1  166.87  1671.1  157.77  1812.5  159.35  1914.7  158.84
  2036.1  156.38  2471.1  157.43  3161.1  157.99  3558.2  159.34  3631.8   159.7
    4322  158.24  4481.1   155.8  4833.4  156.79  4971.1     159 4976.55  158.13
  4981.5  150.93  5001.9   148.6  5006.2   149.5 5010.61  158.14  5010.8  158.39
  5086.1   156.4  5460.4  158.91  5669.2  156.39  6052.9  156.79  6357.3  157.62
  6490.2  157.84  6675.6  160.26  6944.6  161.43  7174.6  162.49  8293.1  165.01
#Mann= 19 ,-1 , 0
   831.1      .1       0  1812.5     .05       0  1914.7     .11       0
  2471.1     .05       0  3161.1     .12       0  3558.2     .05       0
  3631.8     .12       0    4322     .13       0  4833.4     .11       0
  4971.1     .08       0  5010.8     .11       0  5086.1     .13       0
  5669.2     .12       0  6052.9     .11       0  6357.3     .05       0
  6490.2     .11       0  6675.6     .05       0  6944.6     .09       0
  7174.6     .08       0
#XS Ineff= 1 ,-1
  981.53 3282.71163.8199
Permanent Ineff=
       F
Bank Sta=4976.55,5010.61
XS Rating Curve= 0 ,0
Exp/Cntr=0.3,0.1

Type RM Length L Ch R = 1 ,56361   ,669,729,753
BEGIN DESCRIPTION:
56361
END DESCRIPTION:
XS GIS Cut Line= 3
      1925941.57       330555.85      1923899.88       327201.65
      1921629.07       324389.18
#Sta/Elev= 30
  1086.7  167.97  1701.7  168.12  1961.7  156.87  2094.1  155.83  2148.6  156.99
  2176.7  158.77    2251   157.7  2305.9  156.44  3186.8  156.52  3998.3  157.27
  4129.1  158.03  4279.5  157.52    4988  155.98  4989.9   149.9  5001.9   147.6
  5006.2   148.5  5013.4  156.07  5358.4  158.22  5528.4  155.66  5793.4  155.62
  5878.4  157.42  6598.4  155.09  7229.9  157.71  7436.5  159.74  7541.1  160.42
  7643.4  159.63  7678.4  157.19  7806.6  157.26  8566.7   162.2  8628.2  162.06
#Mann= 16 ,-1 , 0
  1086.7     .09       0  2094.1     .12       0  2148.6     .05       0
    2251      .1       0  2305.9     .12       0  3186.8     .13       0
  3998.3     .05       0  4129.1     .12       0  4279.5     .12       0
    4988     .08       0  5013.4     .12       0  7229.9     .08       0
  7436.5     .05       0  7541.1     .07       0  7806.6     .06       0
  8566.7     .05       0
#XS Ineff= 3 ,-1
 7088.26 8607.83  164.03 1565.06 4131.03  163.96 8607.83 8613.07  160.57
Permanent Ineff=
       F       F       F
Bank Sta=4988,5013.4
XS Rating Curve= 0 ,0
Exp/Cntr=0.3,0.1

Type RM Length L Ch R = 1 ,55632   ,804,776,821
BEGIN DESCRIPTION:
55632
END DESCRIPTION:
XS GIS Cut Line= 3
      1926130.79       330164.53       1924422.2       326697.18
      1922507.14       323797.93
#Sta/Elev= 30
  1134.9   166.7    1658  166.34  1729.9  165.24  1869.9  157.61  2051.3  160.35
  2154.4   158.6  2614.9  156.24  2698.5   157.4  2997.2  156.62  3151.3  155.93
    3283  157.03  3739.1  157.78  4779.6  155.79  4977.9  154.43  4990.1  149.35
  5004.1   147.1  5011.7  150.12  5025.6  152.01  5029.5  156.39  5080.5  156.08
  5087.3  156.05  5881.7  156.16  6780.8  155.16  7000.3  155.53  7490.4  155.34
  7669.6  159.33  7777.8  163.74  8118.9   163.4  8225.4  161.12    8475   159.5
#Mann= 20 ,-1 , 0
  1134.9     .09       0    1658     .12       0  2051.3     .05       0
  2154.4      .1       0  2698.5      .1       0  2997.2     .13       0
  3151.3     .05       0    3283     .11       0  3739.1     .12       0
  4779.6     .12       0  4977.9     .08       0  5029.5     .12       0
  5080.5     .12       0  5087.3     .12       0  5881.7     .12       0
  6780.8     .12       0  7000.3     .11       0  7669.6     .05       0
  7777.8     .08       0  8118.9     .09       0
#XS Ineff= 2 ,-1
    7500    8475   165.9 1744.68    3800 161.492
Permanent Ineff=
       F       F
Bank Sta=4977.9,5029.5
XS Rating Curve= 0 ,0
Exp/Cntr=0.3,0.1

Type RM Length L Ch R = 1 ,54856   ,671,903,802
BEGIN DESCRIPTION:
54856
END DESCRIPTION:
XS GIS Cut Line= 3
      1926337.38       329826.63      1925149.88       326451.65
      1923316.55       323243.32
#Sta/Elev= 30
  1402.1  166.95  1692.4  166.92  1882.1  165.08  1942.1  161.18  2087.1  158.11
  2162.1  157.99  2197.1  160.99  2221.2  160.48  2328.3  157.49  2647.1  155.89
  3131.1  156.75  3236.4  156.04  4504.6  155.31  4987.3  154.81  4991.4  148.67
  5000.7   146.6  5007.9   148.8  5012.5  154.77  5709.9  156.01  6199.9  154.63
  6619.9  156.77  6779.9  155.15  7694.1  155.93  7974.9   157.4  8079.9  160.24
    8275  159.56  8329.9  163.46  8388.3   163.9  8424.5  164.16  8675.1  163.47
#Mann= 13 ,-1 , 0
  1402.1     .08       0  1692.4     .12       0  2221.2     .05       0
  2328.3      .1       0  3131.1     .05       0  3236.4     .11       0
  4504.6     .12       0  4987.3     .08       0  5012.5     .12       0
  7694.1      .1       0    8275     .05       0  8388.3     .08       0
  8424.5     .09       0
#XS Ineff= 3 ,-1
                            1500 3652.01 161.519    7500 8591.68  166.18
Permanent Ineff=
       F       F       F
Bank Sta=4987.3,5012.5
XS Rating Curve= 0 ,0
Exp/Cntr=0.3,0.1

Type RM Length L Ch R = 1 ,53953   ,769,654,697
BEGIN DESCRIPTION:
53953
END DESCRIPTION:
XS GIS Cut Line= 3
       1926479.4       329522.37      1925415.25       325339.15
      1924534.58       322935.67
#Sta/Elev= 30
  1007.1  167.02  1317.1  165.48  1522.1  158.06  1682.1  157.25  1705.5  154.14
  1727.1  153.12  1777.1  157.93  1817.6  158.92  1842.1  156.01    1974  155.79
  2516.1  156.54  2616.8  156.21  2754.8  155.96  3187.1  157.12  3247.1   155.3
  3717.9  155.25    4681  155.32  4842.1  152.56  4977.9  153.26  4990.1  148.18
  5004.1  145.93  5025.6  150.84  5029.5  155.22  5131.7  154.31  5636.3  154.31
  5654.5  154.44  6648.5  154.74  7313.6  155.61  7506.2  161.35  7883.3   161.8
#Mann= 16 ,-1 , 0
  1007.1     .08       0  1705.5     .05       0  1817.6      .1       0
    1974      .1       0  2516.1     .05       0  2616.8     .11       0
  2754.8     .11       0  3717.9     .12       0    4681     .12       0
  4977.9     .08       0  5029.5     .12       0  5131.7     .12       0
  5636.3     .12       0  5654.5     .12       0  6648.5     .11       0
  7506.2     .05       0
#XS Ineff= 2 ,-1
 1331.21 3031.85     160    6300    8000     160
Permanent Ineff=
       F       F
Bank Sta=4977.9,5029.5
XS Rating Curve= 0 ,0
Exp/Cntr=0.5,0.3

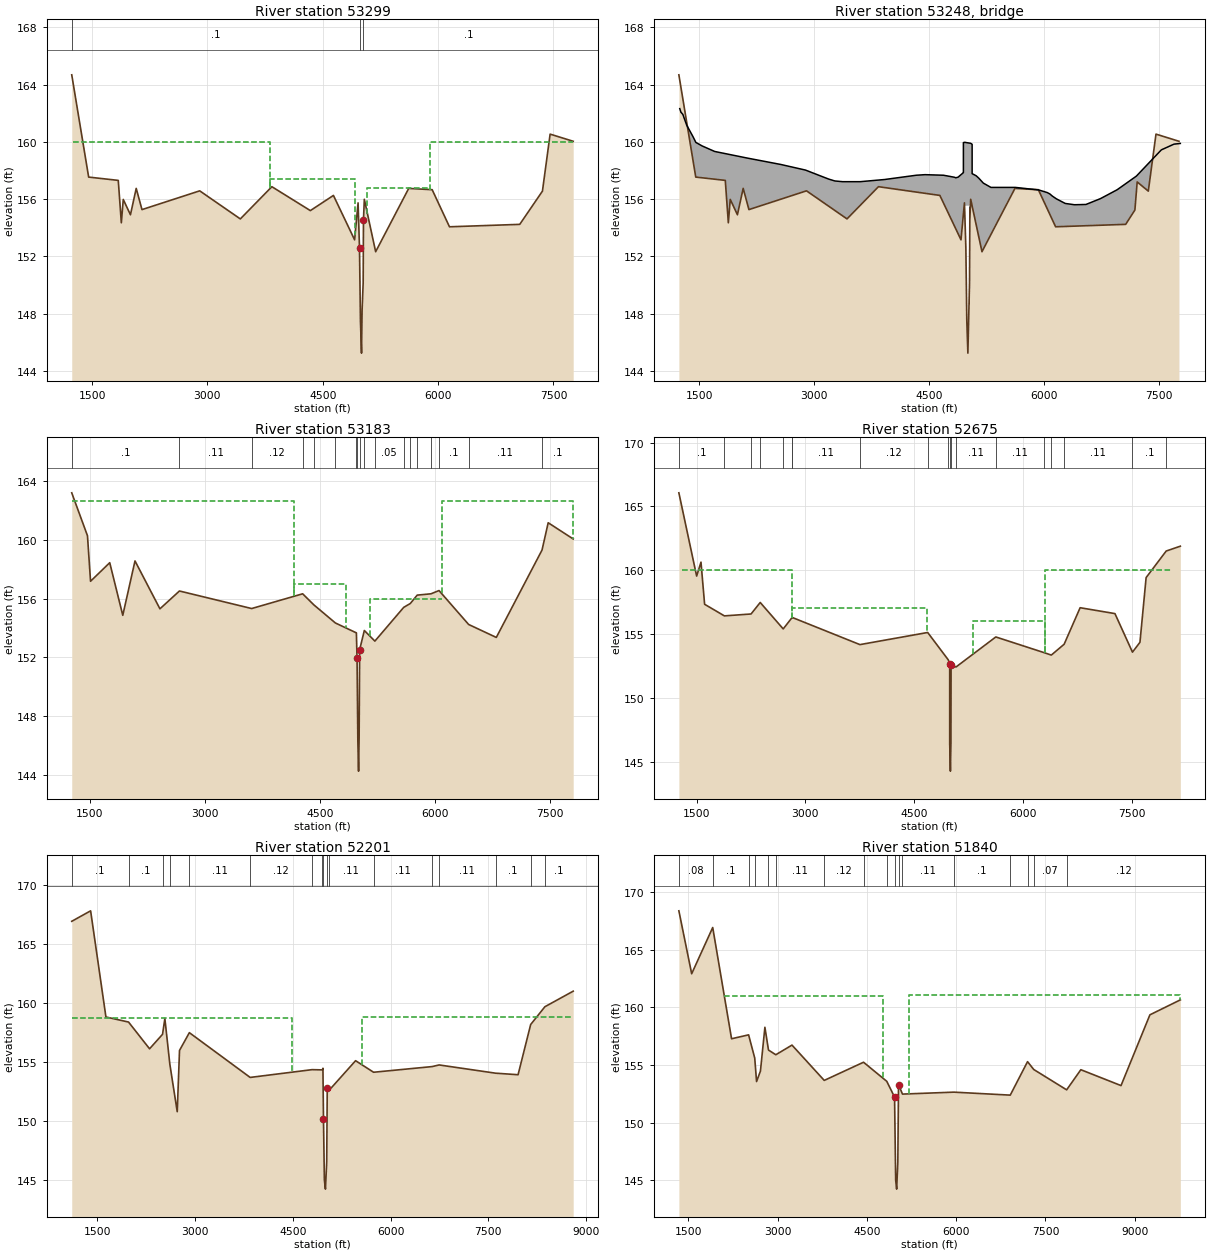
Type RM Length L Ch R = 1 ,53299   ,105,116,142
BEGIN DESCRIPTION:
53299
END DESCRIPTION:
XS GIS Cut Line= 6
      1926600.53        329231.8      1926137.76       325688.61
      1926091.94       325508.06      1925982.45       324587.18
      1925848.51       323698.52      1925603.57       322796.11
#Sta/Elev= 30
    1236  164.68    1456  157.54    1841  157.31    1881  154.35    1906  155.98
  1999.4  154.91  2074.4  156.75  2149.4  155.27    2900  156.58  3428.3  154.62
  3838.3  156.87  4338.9   155.2  4638.9  156.26  4914.4  153.16  4959.4  155.74
  4977.9  152.58  4990.1   147.5  5004.1  145.25  5011.7  148.27  5025.6  150.16
  5029.5  154.54  5040.7  155.99  5187.9  152.33  5617.9  156.75    5923  156.66
    6148  154.07  7061.7  154.24  7356.7  156.56  7456.7  160.54  7756.8  160.04
#Mann= 3 ,-1 , 0
    1236      .1       0  4977.9     .08       0  5029.5      .1       0
#XS Ineff= 4 ,-1
    5900  7756.8     160 1251.42 3818.53     160  5080.7    5900 156.803
 3818.53 4919.92   157.4
Permanent Ineff=
       F       F       F       F
Bank Sta=4977.9,5029.5
XS Rating Curve= 0 ,0
Exp/Cntr=0.5,0.3

Type RM Length L Ch R = 3 ,53248   ,,,
BEGIN DESCRIPTION:
NC HWY 710,  R_BAS_12
END DESCRIPTION:
Bridge Culvert--1,0,-1,-1, 0
Deck Dist Width WeirC Skew NumUp NumDn MinLoCord MaxHiCord MaxSubmerge Is_Ogee
40,45,3,0, 55, 55, 155.63, , 0.95, 0, 1,1,,
  1247.6  1262.6  1287.6  1337.6  1417.6  1457.6  1537.6  1702.6  2126.4  2566.4
    2887    3132    3190    3270    3370    3600  3916.2  4331.2  4446.2  4686.2
  4828.6  4846.7  4877.8  4910.1  4942.4  4945.6  4945.6  4962.1  4963.5  4982.4
  5041.3  5043.1  5059.5  5059.5  5112.9  5147.2  5205.5  5304.7  5624.7  5929.7
  6038.8  6073.8  6103.8  6158.8  6233.8  6273.8  6393.8  6543.8  6733.8  6951.2
  7201.2  7366.2  7526.2  7691.2  7774.2
  162.32  162.07  161.92  161.17  160.39  159.96  159.72  159.33  158.87  158.42
  158.03  157.52   157.4  157.27  157.22  157.22  157.37  157.67  157.71  157.67
  157.53  157.49  157.54  157.69  157.84  157.85  159.95  159.96  159.97  159.95
   159.9  159.89  159.83  157.78  157.63  157.46  157.12  156.82  156.82  156.64
  156.46  156.36  156.22  156.02  155.81   155.7  155.61  155.63  156.04  156.66
  157.61  158.54  159.44  159.84  159.89
  125.25  125.25  125.25  125.25  125.25  125.25  125.25  125.25  125.25  125.25
  125.25  125.25  125.25  125.25  125.25  125.25  125.25  125.25  125.25  125.25
  125.25  125.25  125.25  125.25  125.25  125.25  125.25  125.25  155.54  155.54
  155.54  125.25  125.25  125.25  125.25  125.25  125.25  125.25  125.25  125.25
  125.25  125.25  125.25  125.25  125.25  125.25  125.25  125.25  125.25  125.25
  125.25  125.25  125.25  125.25  125.25
  1247.6  1262.6  1287.6  1337.6  1417.6  1457.6  1537.6  1702.6  2126.4  2566.4
    2887    3132    3190    3270    3370    3600  3916.2  4331.2  4446.2  4686.2
  4828.6  4846.7  4877.8  4910.1  4942.4  4945.6  4945.6  4962.1  4963.5  4982.4
  5041.3  5043.1  5059.5  5059.5  5112.9  5147.2  5205.5  5304.7  5624.7  5929.7
  6038.8  6073.8  6103.8  6158.8  6233.8  6273.8  6393.8  6543.8  6733.8  6951.2
  7201.2  7366.2  7526.2  7691.2  7774.2
  162.32  162.07  161.92  161.17  160.39  159.96  159.72  159.33  158.87  158.42
  158.03  157.52   157.4  157.27  157.22  157.22  157.37  157.67  157.71  157.67
  157.53  157.49  157.54  157.69  157.84  157.85  159.95  159.96  159.97  159.95
   159.9  159.89  159.83  157.78  157.63  157.46  157.12  156.82  156.82  156.64
  156.46  156.36  156.22  156.02  155.81   155.7  155.61  155.63  156.04  156.66
  157.61  158.54  159.44  159.84  159.89
  125.25  125.25  125.25  125.25  125.25  125.25  125.25  125.25  125.25  125.25
  125.25  125.25  125.25  125.25  125.25  125.25  125.25  125.25  125.25  125.25
  125.25  125.25  125.25  125.25  125.25  125.25  125.25  125.25  155.54  155.54
  155.54  125.25  125.25  125.25  125.25  125.25  125.25  125.25  125.25  125.25
  125.25  125.25  125.25  125.25  125.25  125.25  125.25  125.25  125.25  125.25
  125.25  125.25  125.25  125.25  125.25
Pier Skew, UpSta & Num, DnSta & Num=  ,5019, 2 ,5019, 2 , 0 , 0 , 0 ,0,0
     1.2     1.2
  149.49  155.54
     1.2     1.2
  151.11  155.54
Abutment Skew #Up #Dn= , 2 , 2
  4963.5  4982.4
  155.54  150.94
  4963.5  4982.4
  155.54  152.56
Abutment Skew #Up #Dn= , 2 , 2
  5019.4  5041.3
  149.41  155.54
  5019.4  5041.3
  151.03  155.54
BR Coef= 1 , 1 , 0 ,1.25, 0 ,,,0.8,0,2,0,
WSPro=,,,, 1 ,,,, 0 ,,,, 0 ,,,,-1 ,-1 ,-1 , 0 , 0 , 0 , 0 , 0
BR U #Sta/Elev= 30
    1236  164.68    1456  157.54    1841  157.31    1881  154.35    1906  155.98
  1999.4  154.91  2074.4  156.75  2149.4  155.27    2900  156.58  3428.3  154.62
  3838.3  156.87  4638.9  156.26  4914.4  153.16  4959.4  155.74  4977.9  152.58
  4990.1   147.5  5004.1  145.25  5025.6  150.16  5029.5  154.54  5040.7  155.99
  5187.9  152.33  5617.9  156.75    5923  156.66    6148  154.07  7061.7  154.24
  7181.7  155.24  7211.7   157.2  7356.7  156.56  7456.7  160.54  7756.8  160.04
BR U #Mann= 3
    1236     .05  4977.9     .04  5029.5     .05
BR D #Sta/Elev= 30
  1263.7  163.17  1468.7  160.26  1508.7  157.17  1758.7  158.43  1928.7  154.86
  2087.9  158.55  2412.9   155.3  2666.9  156.51  3608.1  155.32  4272.4  156.32
    4418  155.57  4699.1  154.34  4972.3  153.67    4981  151.94  5000.7  144.29
  5007.9  146.49    5015  152.53  5075.9  153.83  5213.3  153.11    5589   155.4
  5674.6  155.66  5764.6  156.23  5944.7  156.32  6049.1  156.54  6434.6  154.24
  6795.4  153.36  7061.4  158.94  7241.4  156.69  7391.3  159.29  7797.3  160.04
BR D #Mann= 18
  1263.7      .1  2666.9     .11  3608.1     .12  4272.4     .05    4418     .12
  4699.1     .08  4972.3     .05    4981     .04    5015     .05  5075.9     .11
  5213.3     .05    5589      .1  5674.6     .05  5764.6      .1  5944.7     .05
  6049.1      .1  6434.6     .11  7391.3      .1
BC Design=,, 0 ,, 0 ,,,,,,
BC HTab HWMax=164.68
BC Use User HTab Curves=0
BC User HTab FreeFlow(D)= 0

Type RM Length L Ch R = 1 ,53183   ,505,508,533
BEGIN DESCRIPTION:
53183
END DESCRIPTION:
XS GIS Cut Line= 6
      1926699.74       329219.22      1926603.99       328461.03
       1926169.5       325289.04      1926081.56       324573.81
      1925946.53        323677.9      1925700.07        322769.9
#Sta/Elev= 30
  1263.7  163.17  1468.7  160.26  1508.7  157.17  1758.7  158.43  1928.7  154.86
  2087.9  158.55  2412.9   155.3  2666.9  156.51  3608.1  155.32  4272.4  156.32
    4418  155.57  4699.1  154.34  4972.3  153.67    4981  151.94  4991.4  146.36
  5000.7  144.29  5007.9  146.49    5015  152.53  5075.9  153.83  5213.3  153.11
    5589   155.4  5674.6  155.66  5764.6  156.23  5944.7  156.32  6049.1  156.54
  6434.6  154.24  6795.4  153.36  7391.3  159.29  7471.4  161.14  7797.3  160.04
#Mann= 18 ,-1 , 0
  1263.7      .1       0  2666.9     .11       0  3608.1     .12       0
  4272.4     .05       0    4418     .12       0  4699.1     .08       0
  4972.3     .05       0    4981     .08       0    5015     .05       0
  5075.9     .11       0  5213.3     .05       0    5589      .1       0
  5674.6     .05       0  5764.6      .1       0  5944.7     .05       0
  6049.1      .1       0  6434.6     .11       0  7391.3      .1       0
#XS Ineff= 4 ,-1
  1263.7 4162.57   162.6 6081.29  7794.9   162.6 5152.38 6081.29     156
 4162.57 4841.35     157
Permanent Ineff=
       F       F       F       F
Bank Sta=4981,5015
XS Rating Curve= 0 ,0
Exp/Cntr=0.5,0.3

Type RM Length L Ch R = 1 ,52675   ,442,474,474
BEGIN DESCRIPTION:
52675
END DESCRIPTION:
XS GIS Cut Line= 3
      1926878.72       329389.36      1926696.14       325639.62
      1926260.77       322507.72
#Sta/Elev= 30
  1255.7  166.06  1500.7  159.54  1560.7  160.63  1610.7  157.33  1883.8  156.42
  2251.5  156.57  2377.6  157.47  2694.6   155.4  2814.4  156.27  2818.3   156.3
  3752.8  154.17  4687.3  155.12  4970.8  152.98  4991.1  152.69  4991.4  146.33
  5000.7  144.26  5007.9  146.46  5009.9  152.54  5078.6  152.42  5626.9  154.77
  6288.2  153.55  6392.5  153.35  6569.3   154.2  6789.9  157.06  7269.9   156.6
  7511.6  153.58  7614.9  154.35  7699.9  159.42  7976.7   161.5  8171.9  161.88
#Mann= 19 ,-1 , 0
  1255.7      .1       0  1883.8      .1       0  2251.5     .05       0
  2377.6      .1       0  2694.6     .05       0  2814.4      .1       0
  2818.3     .11       0  3752.8     .12       0  4687.3     .12       0
  4970.8     .05       0  4991.1     .08       0  5009.9     .05       0
  5078.6     .11       0  5626.9     .11       0  6288.2     .05       0
  6392.5      .1       0  6569.3     .11       0  7511.6      .1       0
  7976.7     .05       0
#XS Ineff= 4 ,-1
 1302.46 2822.31     160 2822.31    4674     157    5319    6300     156
    6300 8062.38     160
Permanent Ineff=
       F       F       F       F
Bank Sta=4991.1,5009.9
XS Rating Curve= 0 ,0
Exp/Cntr=0.3,0.1

Type RM Length L Ch R = 1 ,52201   ,296,361,403
BEGIN DESCRIPTION:
52201
END DESCRIPTION:
XS GIS Cut Line= 4
      1927066.55       329633.99      1926977.03         326398.
       1927159.6       325751.97      1926836.59       321974.11
#Sta/Elev= 30
  1104.9  166.96  1394.9  167.85  1629.9  158.84  1977.3  158.41  2299.9  156.14
  2499.3  157.37  2534.9  158.71  2611.6  154.82  2724.9   150.8  2759.9     156
    2911  157.51  3844.7  153.71  4795.4  154.37    4953  154.35  4962.1  154.49
  4970.5  150.19  4984.2  145.01  5000.5  144.23  5020.1  146.54  5028.5  152.85
  5055.5  152.61  5463.5  155.13  5739.6  154.15  6638.4  154.63  6746.2  154.77
  7613.2  154.07  7958.5  153.94    8152   158.2  8370.4  159.71  8805.1  161.03
#Mann= 17 ,-1 , 0
  1104.9      .1       0  1977.3      .1       0  2499.3     .05       0
  2611.6      .1       0    2911     .11       0  3844.7     .12       0
  4795.4     .12       0    4953     .05       0  4970.5     .08       0
  5028.5     .05       0  5055.5     .11       0  5739.6     .11       0
  6638.4     .05       0  6746.2     .11       0  7613.2      .1       0
    8152     .05       0  8370.4      .1       0
#XS Ineff= 2 , 0
         4491.09  158.75  5559.8          158.85
Permanent Ineff=
       F       F
Bank Sta=4970.5,5028.5
XS Rating Curve= 0 ,0
Exp/Cntr=0.5,0.3

Type RM Length L Ch R = 1 ,51840   ,666,660,707
BEGIN DESCRIPTION:
51840
END DESCRIPTION:
XS GIS Cut Line= 6
      1927307.49       329328.66      1927068.27       326411.44
      1927390.58        325989.6       1927634.4        325648.2
       1927960.7       325257.14      1927273.62       321279.77
#Sta/Elev= 30
  1342.6   168.4  1557.6  162.93  1911.2  166.95  2227.6  157.28  2513.8  157.62
  2616.9   155.6  2647.6  153.56  2712.6  154.47  2787.6  158.28  2847.7   156.3
    2971  155.89  3242.6  156.73  3784.2  153.66  4444.4  155.24  4834.6  153.58
  4965.5  152.21  4984.2  144.99  5000.5  144.21  5020.1  146.52  5031.9   153.3
  5098.5  152.47  5961.4  152.64  6908.6  152.38  7199.2  155.29  7302.9  154.61
  7855.8  152.84  8094.3  154.59  8769.3  153.21  9254.3  159.36  9765.6  160.66
#Mann= 17 ,-1 , 0
  1342.6     .08       0  1911.2      .1       0  2513.8     .05       0
  2616.9     .11       0  2847.7     .11       0    2971     .11       0
  3784.2     .12       0  4444.4     .11       0  4834.6      .1       0
  4965.5     .08       0  5031.9      .1       0  5098.5     .11       0
  5961.4      .1       0  6908.6     .08       0  7199.2     .05       0
  7302.9     .07       0  7855.8     .12       0
#XS Ineff= 2 ,-1
 2097.07 4777.25 161.039 5211.27  9765.6  161.05
Permanent Ineff=
       F       F
Bank Sta=4965.5,5031.9
XS Rating Curve= 0 ,0
Exp/Cntr=0.5,0.3

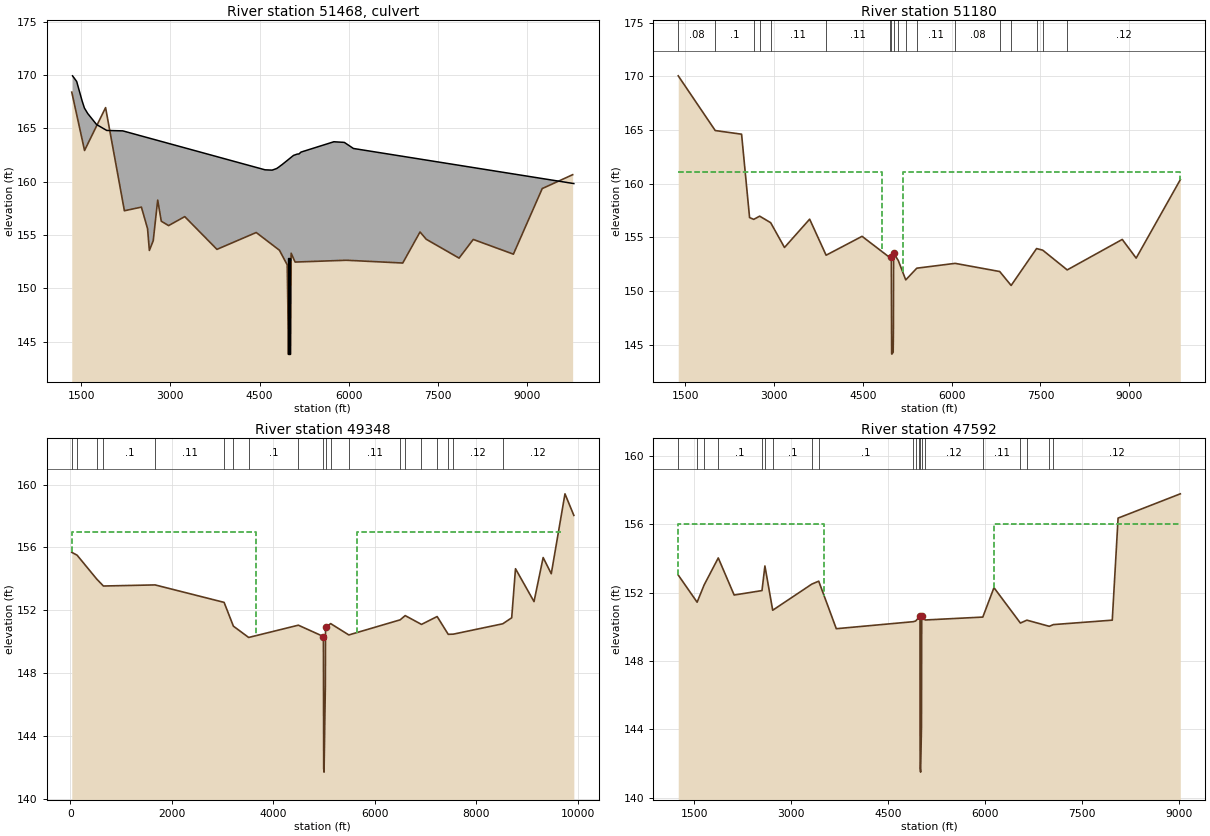
Type RM Length L Ch R = 2 ,51468   ,,,
BEGIN DESCRIPTION:
Ruby Dr (SR 1602),  R_BAS_11
END DESCRIPTION:
Bridge Culvert--1,0,-1,-1, 0
Deck Dist Width WeirC Skew NumUp NumDn MinLoCord MaxHiCord MaxSubmerge Is_Ogee
320,175,3,0, 22, 22, 161.09, , 0.95, 0, 8,8,,
  1355.4  1425.4  1515.4  1555.4  1610.4  1760.4  1930.4  2200.4    4592    4712
  4788.1  4827.1  4871.5  4875.1  5071.3  5132.2  5164.1    5197    5750    5926
    6079  9785.6
  169.93   169.4   167.6  166.91   166.4  165.36  164.81  164.77  161.12  161.09
  161.24  161.39  161.58  161.59  162.47  162.59  162.61  162.78  163.75  163.69
  163.12  159.83
  123.92  123.92  123.92  123.92  123.92  123.92  123.92  123.92  123.92  123.92
  123.92  123.92  123.92  123.92  123.92  123.92  123.92  123.92  123.92  123.92
  123.92  123.92
  1355.4  1425.4  1515.4  1555.4  1610.4  1760.4  1930.4  2200.4    4592    4712
  4788.1  4827.1  4871.5  4875.1  5071.3  5132.2  5164.1    5197    5750    5926
    6079  9785.6
  169.93   169.4   167.6  166.91   166.4  165.36  164.81  164.77  161.12  161.09
  161.24  161.39  161.58  161.59  162.47  162.59  162.61  162.78  163.75  163.69
  163.12  159.83
  124.11  124.11  124.11  124.11  124.11  124.11  124.11  124.11  124.11  124.11
  124.11  124.11  124.11  124.11  124.11  124.11  124.11  124.11  124.11  124.11
  124.11  124.11
Culvert=2,9,10,414,0.012,0.4,1,8,1,143.84,4988.1,143.33,4988.1,Culvert #1  , 0 ,195
Culvert Bottom n=0.012
Culvert=2,9,10,414,0.012,0.4,1,8,1,143.85,4999.3,143.38,4999.3,Culvert #2  , 0 ,195
Culvert Bottom n=0.012
Culvert=2,9,10,414,0.012,0.4,1,8,1,143.86,5010.1,143.42,5010.1,Culvert #3  , 0 ,195
Culvert Bottom n=0.012
BR U #Sta/Elev= 30
  1342.6   168.4  1557.6  162.93  1911.2  166.95  2227.6  157.28  2513.8  157.62
  2616.9   155.6  2647.6  153.56  2712.6  154.47  2787.6  158.28  2847.7   156.3
    2971  155.89  3242.6  156.73  3784.2  153.66  4444.4  155.24  4834.6  153.58
  4965.5  152.21  4982.9  145.96  4983.1  143.84  5015.1  143.86  5031.9   153.3
  5098.5  152.47  5961.4  152.64  6908.6  152.38  7199.2  155.29  7302.9  154.61
  7855.8  152.84  8094.3  154.59  8769.3  153.21  9254.3  159.36  9765.6  160.66
BR U #Mann= 17
  1342.6     .08  1911.2      .1  2513.8     .05  2616.9     .11  2847.7     .11
    2971     .11  3784.2     .12  4444.4     .11  4834.6      .1  4965.5     .08
  5031.9      .1  5098.5     .11  5961.4      .1  6908.6     .08  7199.2     .05
  7302.9     .07  7855.8     .12
BR D #Sta/Elev= 30
  1380.7  170.05  2005.8  164.95  2450.7  164.61  2585.7  156.84  2655.8  156.67
  2715.7  158.61  2756.1  156.97  2942.3  156.36  3175.7  154.05  3600.7  156.69
  3878.8  153.33  4486.1  155.09  4829.5  151.52  4962.1  153.08  4979.9  154.22
  4983.1  143.33  5015.1  143.42  5018.8  153.52  5097.6  152.84    5224  151.03
  5410.6  152.12  6057.3  152.57  6811.3  151.81  7004.5  150.51  7434.2  153.95
  7537.9   153.8  7951.7  151.96  8881.5   154.8  9116.5  153.06  9862.2  160.37
BR D #Mann= 18
  1380.7     .08  2005.8      .1  2655.8     .05  2756.1     .11  2942.3     .11
  3878.8     .11  4962.1      .1  4979.9     .04  5018.8      .1  5097.6     .08
    5224     .11  5410.6     .11  6057.3     .08  6811.3      .1  7004.5     .08
  7434.2     .05  7537.9     .07  7951.7     .12
BR D Banks=4979.9,
BC Design=,, 0 ,, 0 ,,,,,,
BC HTab HWMax=168.4
BC Use User HTab Curves=0
BC User HTab FreeFlow(D)= 0

Type RM Length L Ch R = 1 ,51180   ,1947,1832,1955
BEGIN DESCRIPTION:
51180
END DESCRIPTION:
XS GIS Cut Line= 6
      1927570.79       329384.45      1927594.92       326674.19
      1927939.68        326210.4      1928209.55       325865.63
      1928493.77        325530.1      1927535.23       321322.22
#Sta/Elev= 30
  1380.7  170.05  2005.8  164.95  2450.7  164.61  2585.7  156.84  2655.8  156.67
  2756.1  156.97  2942.3  156.36  3175.7  154.05  3600.7  156.69  3878.8  153.33
  4486.1  155.09  4962.1  153.08 4980.47  153.14    4986  144.18  4989.3  144.11
  5011.7  144.29  5015.5  146.23  5018.8  153.52  5097.6  152.84    5224  151.03
  5410.6  152.12  6057.3  152.57  6811.3  151.81  7004.5  150.51  7434.2  153.95
  7537.9   153.8  7951.7  151.96  8881.5   154.8  9116.5  153.06  9862.2  160.37
#Mann= 18 ,-1 , 0
  1380.7     .08       0  2005.8      .1       0  2655.8     .05       0
  2756.1     .11       0  2942.3     .11       0  3878.8     .11       0
  4962.1      .1       0 4980.47     .08       0  5018.8      .1       0
  5097.6     .05       0    5224     .11       0  5410.6     .11       0
  6057.3     .08       0  6811.3      .1       0  7004.5     .08       0
  7434.2     .05       0  7537.9     .07       0  7951.7     .12       0
#XS Ineff= 2 , 0
       0  4823.1  161.09  5175.1       0  161.09
Permanent Ineff=
       F       F
Bank Sta=4980.47,5018.8
XS Rating Curve= 0 ,0
Exp/Cntr=0.5,0.3

Type RM Length L Ch R = 1 ,49348   ,1752,1756,1600
BEGIN DESCRIPTION:
49348
END DESCRIPTION:
XS GIS Cut Line= 3
      1931405.84        330216.9      1929896.19       325471.93
      1928004.04         320936.
#Sta/Elev= 30
    27.6  155.69   132.8  155.51   520.1  153.99   651.2  153.55  1669.9  153.62
  3029.6  152.51  3212.2     151  3513.4  150.28  4492.8  151.06  4986.7  150.34
  4992.3  141.94  4999.2  141.72  5024.8   147.2  5028.1  150.92  5129.8  151.16
  5487.5  150.44  6498.8   151.4  6598.3  151.67  6919.1  151.11  7227.8  151.61
  7446.2  150.48  7546.3  150.49  8521.5  151.15  8696.9  151.53  8771.9  154.65
  9136.9  152.56  9316.9  155.36  9476.9  154.33  9746.9  159.41  9921.7  158.04
#Mann= 20 ,-1 , 0
    27.6     .05       0   132.8     .07       0   520.1     .05       0
   651.2      .1       0  1669.9     .11       0  3029.6     .05       0
  3212.2     .09       0  3513.4      .1       0  4492.8     .12       0
  4986.7     .08       0  5028.1     .12       0  5129.8     .13       0
  5487.5     .11       0  6498.8     .09       0  6598.3     .05       0
  6919.1     .12       0  7227.8     .11       0  7446.2     .05       0
  7546.3     .12       0  8521.5     .12       0
#XS Ineff= 2 ,-1
    5650 9663.33     157    27.6    3650     157
Permanent Ineff=
       F       F
Bank Sta=4986.7,5028.1
XS Rating Curve= 0 ,0
Exp/Cntr=0.3,0.1

Type RM Length L Ch R = 1 ,47592   ,1838,1857,1867
BEGIN DESCRIPTION:
47592
END DESCRIPTION:
XS GIS Cut Line= 3
      1933158.14       326979.35      1930837.38       324034.98
      1929149.86       320389.11
#Sta/Elev= 30
  1249.8  153.03  1541.9  151.44  1650.4  152.45  1869.2  154.03  2114.8  151.86
  2545.4  152.12  2590.6  153.56  2711.1  150.97  3316.8   152.5    3423  152.67
  3694.8  149.89  4884.9   150.3  4922.3  150.34  4967.4  150.53    4990  150.63
  4990.8  143.74  4992.3  141.72  4999.2   141.5  5012.4  144.14  5016.3  150.64
  5070.1   150.4  5961.1  150.57  6133.8  152.29  6542.7  150.22  6642.7  150.39
  6989.6  150.03    7053  150.13  7963.8  150.39  8053.8  156.36  9016.3  157.78
#Mann= 20 ,-1 , 0
  1249.8     .12       0  1541.9     .05       0  1650.4     .08       0
  1869.2      .1       0  2545.4     .12       0  2590.6     .05       0
  2711.1      .1       0  3316.8     .05       0    3423      .1       0
  4884.9     .11       0  4922.3     .08       0  4967.4     .05       0
    4990     .08       0  5016.3     .05       0  5070.1     .12       0
  5961.1     .11       0  6542.7     .05       0  6642.7      .1       0
  6989.6     .11       0    7053     .12       0
#XS Ineff= 2 ,-1
  1249.8 3506.62     156    6130    9000     156
Permanent Ineff=
       F       F
Bank Sta=4990,5016.3
XS Rating Curve= 0 ,0
Exp/Cntr=0.5,0.3