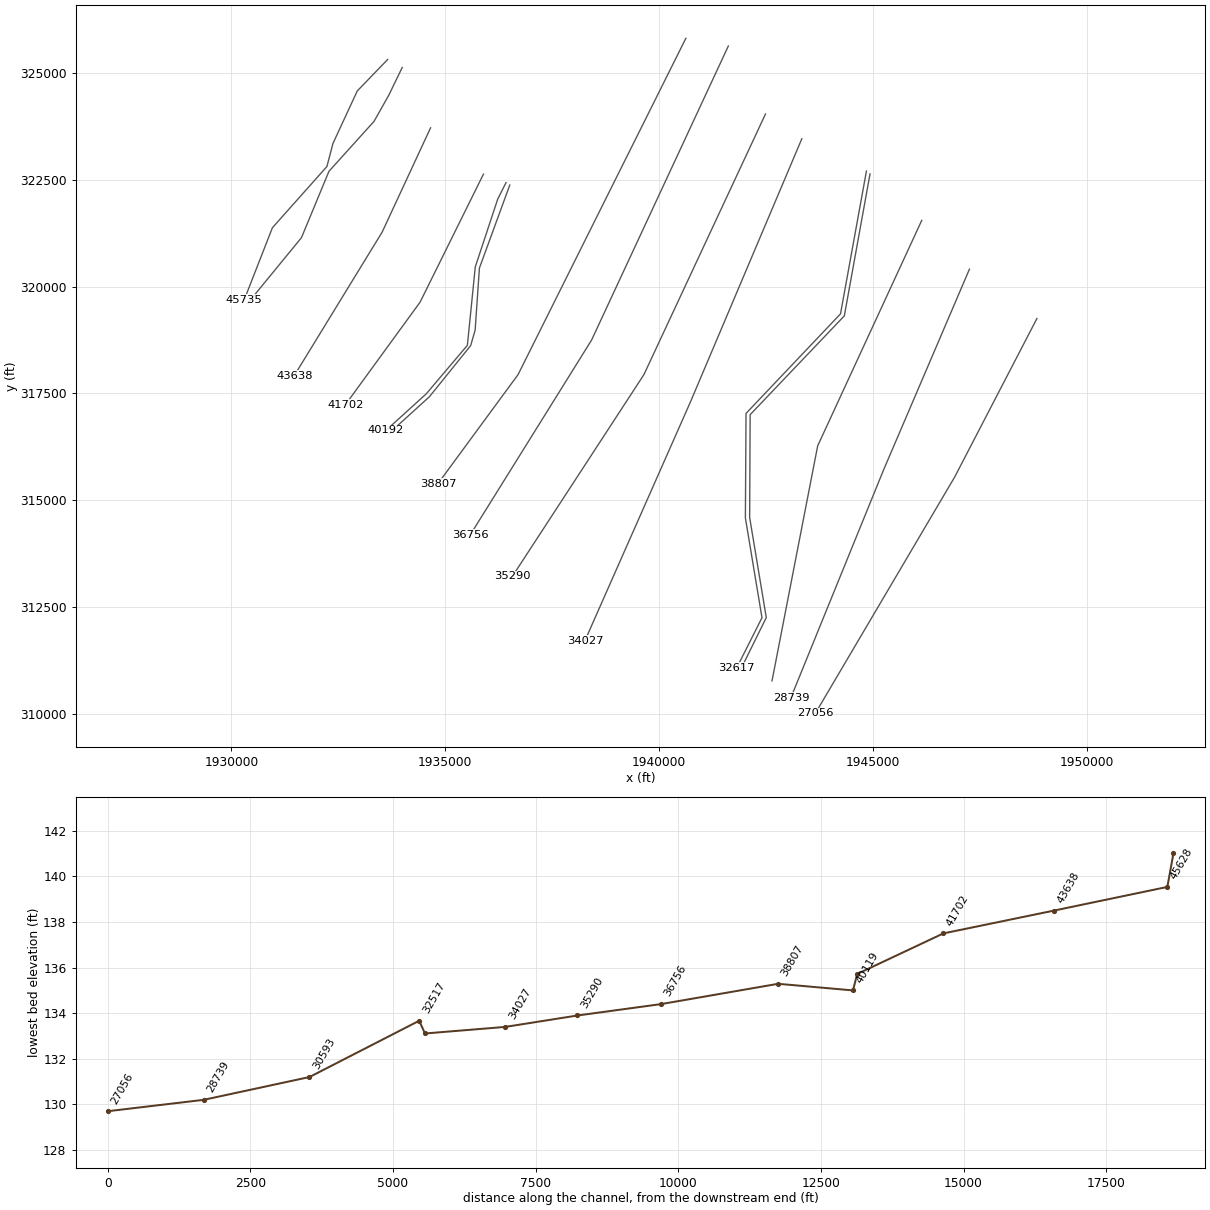
HEC-RAS study BackSwamp.prj: Back Swamp Detailed Study

--- BackSwamp.g01 (geometry) --- (continued)

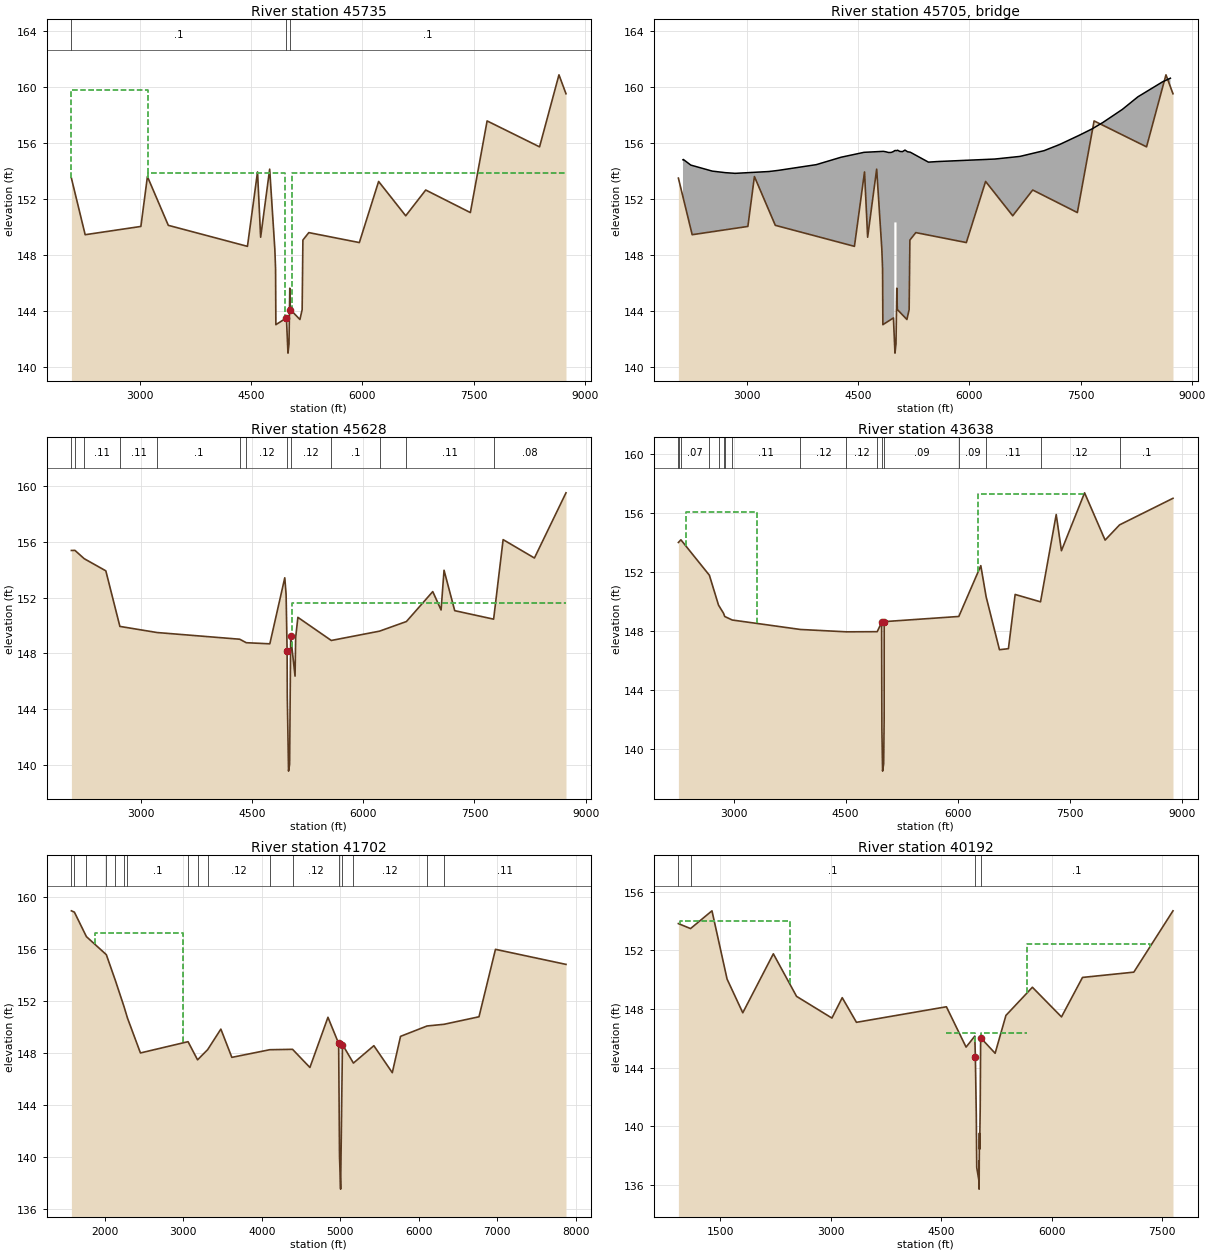
Type RM Length L Ch R = 1 ,45735   ,130,107,116
BEGIN DESCRIPTION:
45735
END DESCRIPTION:
XS GIS Cut Line= 6
      1933652.02       325308.15      1932941.84       324572.79
       1932372.7       323343.84      1932232.21       322806.24
       1930957.4       321374.51      1930297.32       319686.13
#Sta/Elev= 30
  2070.7   153.5  2256.7  149.46  3008.7  150.05    3097  153.61    3379  150.13
  4447.3  148.63  4583.3  153.94  4625.3  149.28  4747.3  154.14  4816.9  148.43
  4826.9  147.03  4830.9  143.04  4973.7  143.52  4994.1  141.01    5008  141.66
  5018.9  145.64  5026.4  144.12  5155.3  143.41  5185.6  144.11  5195.8  149.08
  5275.8  149.61  5957.8   148.9  6217.8  153.26  6583.8  150.81  6853.8  152.65
  7456.4  151.04  7682.4  157.58  8390.4  155.73  8652.4  160.87  8747.2  159.52
#Mann= 3 ,-1 , 0
  2070.7      .1       0  4973.7     .06       0  5026.4      .1       0
#XS Ineff= 3 ,-1
  2070.7 3104.52  159.77    5045  8747.2  153.84 3104.52    4955  153.84
Permanent Ineff=
       F       F       F
Bank Sta=4973.7,5026.4
XS Rating Curve= 0 ,0
Exp/Cntr=0.5,0.3

Type RM Length L Ch R = 3 ,45705   ,,,
BEGIN DESCRIPTION:
Railroad,  R_BAS_09
END DESCRIPTION:
Bridge Culvert--1,0,-1,-1, 0
Deck Dist Width WeirC Skew NumUp NumDn MinLoCord MaxHiCord MaxSubmerge Is_Ogee
18,27,3,0, 43, 43, 154, , 0.95, 0, 1,1,,
  2132.6  2137.6  2237.6  2527.6  2702.6  2837.6  3292.6  3417.6  3931.6  4266.6
  4576.6  4836.5  4870.2  4904.7  4942.2  4979.1  4985.5  4985.5  4997.4  4998.1
  5015.3  5015.3  5029.7  5061.7  5095.4  5129.5  5164.3  5200.2    5446    5561
    6341    6576  6682.8  6832.8  7007.8  7217.8  7482.8  7657.8  7797.8  8062.8
  8273.1  8603.1  8712.2
  154.81  154.83  154.43     154  153.89  153.84  153.97  154.05  154.46  154.99
  155.34  155.41  155.38  155.33  155.33  155.41  155.45  155.45  155.47  155.47
  155.46  155.46  155.49   155.4  155.39   155.5  155.38  155.35  154.64  154.68
  154.86  154.99  155.05  155.24  155.46   155.9  156.56  157.02  157.46   158.4
   159.3  160.36  160.63
  121.01  121.01  121.01  121.01  121.01  121.01  121.01  121.01  121.01  121.01
  121.01  121.01  121.01  121.01  121.01  121.01  121.01  150.34  150.34  150.34
  150.34  121.01  121.01  121.01  121.01  121.01  121.01  121.01  121.01  121.01
  121.01  121.01  121.01  121.01  121.01  121.01  121.01  121.01  121.01  121.01
  121.01  121.01  121.01
  2132.6  2137.6  2237.6  2527.6  2702.6  2837.6  3292.6  3417.6  3931.6  4266.6
  4576.6  4836.5  4870.2  4904.7  4942.2  4979.1  4985.5  4985.5  4997.4  4998.1
  5015.3  5015.3  5029.7  5061.7  5095.4  5129.5  5164.3  5200.2    5446    5561
    6341    6576  6682.8  6832.8  7007.8  7217.8  7482.8  7657.8  7797.8  8062.8
  8273.1  8603.1  8712.2
  154.81  154.83  154.43     154  153.89  153.84  153.97  154.05  154.46  154.99
  155.34  155.41  155.38  155.33  155.33  155.41  155.45  155.45  155.47  155.47
  155.46  155.46  155.49   155.4  155.39   155.5  155.38  155.35  154.64  154.68
  154.86  154.99  155.05  155.24  155.46   155.9  156.56  157.02  157.46   158.4
   159.3  160.36  160.63
  121.01  121.01  121.01  121.01  121.01  121.01  121.01  121.01  121.01  121.01
  121.01  121.01  121.01  121.01  121.01  121.01  121.01  150.34  150.34  150.34
  150.34  121.01  121.01  121.01  121.01  121.01  121.01  121.01  121.01  121.01
  121.01  121.01  121.01  121.01  121.01  121.01  121.01  121.01  121.01  121.01
  121.01  121.01  121.01
BR Coef= 1 , 1 , 0 ,1.25, 0 ,,,0.8,0,1.2,0,
WSPro=,,,, 1 ,,,, 0 ,,,, 0 ,,,,-1 ,-1 ,-1 , 0 , 0 , 0 , 0 , 0
BC Design=,, 0 ,, 0 ,,,,,,
BC HTab HWMax=160.87
BC Use User HTab Curves=0
BC User HTab FreeFlow(D)= 0

Type RM Length L Ch R = 1 ,45628   ,1799,1990,2148
BEGIN DESCRIPTION:
45628
END DESCRIPTION:
XS GIS Cut Line= 6
      1933993.14       325121.58      1933678.35       324472.32
      1933334.05       323862.42       1932279.6       322693.99
      1931637.35       321142.82      1930378.94       319607.38
#Sta/Elev= 30
  2068.7  155.38  2115.9  155.39  2241.9  154.79  2532.7  153.92  2722.1  149.93
  3223.5  149.49  4336.3  149.01  4424.9  148.76  4742.6  148.68    4944  153.42
  4961.9  152.23  4975.4  148.17    4978  144.87  4994.7  139.54  5009.4  140.05
  5023.4  149.23  5082.5  146.36  5090.7  149.14  5120.7  150.58  5570.7  148.92
  6221.3  149.59  6583.1  150.28  6938.1  152.43  7050.1  151.11  7090.1  153.96
  7234.1  151.06  7758.2  150.45  7886.1  156.16  8308.1  154.84  8733.3  159.52
#Mann= 13 ,-1 , 0
  2068.7     .12       0  2115.9     .05       0  2241.9     .11       0
  2722.1     .11       0  3223.5      .1       0  4336.3     .09       0
  4424.9     .12       0  4975.4     .06       0  5023.4     .12       0
  5570.7      .1       0  6221.3     .11       0  6583.1     .11       0
  7758.2     .08       0
#XS Ineff= 2 , 0
       0    4960   151.6    5040       0   151.6
Permanent Ineff=
       F       F
Bank Sta=4975.4,5023.4
XS Rating Curve= 0 ,0
Exp/Cntr=0.5,0.3

Type RM Length L Ch R = 1 ,43638   ,1887,1936,1876
BEGIN DESCRIPTION:
43638
END DESCRIPTION:
XS GIS Cut Line= 3
       1934655.5       323710.81      1933524.88       321274.57
      1931467.58       317915.18
#Sta/Elev= 30
  2259.5  153.98  2262.1  153.99  2292.9  154.16  2674.8  151.76  2796.9  149.74
  2864.9  149.18  2879.9  148.97  2980.5  148.73  3893.9  148.09  4510.2  147.93
  4922.9  147.94  4981.7  148.57  4985.5  141.29  4994.7   138.5  5009.4  139.01
  5015.5  142.03  5016.3  148.62  6015.9  148.97  6310.3  152.41  6381.8   150.3
  6560.3  146.72  6680.3  146.79  6770.3  150.46  7110.4  149.96  7320.3  155.87
  7390.3  153.42  7700.3  157.34  7975.3  154.14    8169  155.17  8884.6  156.97
#Mann= 17 ,-1 , 0
  2259.5     .05       0  2262.1     .07       0  2292.9     .07       0
  2674.8     .05       0  2796.9     .12       0  2864.9     .08       0
  2879.9     .05       0  2980.5     .11       0  3893.9     .12       0
  4510.2     .12       0  4922.9     .13       0  4981.7     .08       0
  5016.3     .09       0  6015.9     .09       0  6381.8     .11       0
  7110.4     .12       0    8169      .1       0
#XS Ineff= 2 ,-1
 6273.89 7700.64  157.29 2356.69  3312.1  156.04
Permanent Ineff=
       F       F
Bank Sta=4981.7,5016.3
XS Rating Curve= 0 ,0
Exp/Cntr=0.3,0.1

Type RM Length L Ch R = 1 ,41702   ,1633,1510,1498
BEGIN DESCRIPTION:
41702
END DESCRIPTION:
XS GIS Cut Line= 3
      1935891.97        322627.4       1934410.3       319633.94
      1932665.52       317238.12
#Sta/Elev= 30
  1572.7  158.96  1610.8  158.86  1764.1  156.97    2018  155.58  2133.7  153.58
  2243.1  151.58  2287.6  150.69  2452.7     148  3059.5  148.87  3180.7  147.47
    3310  148.26  3477.7  149.84  3617.7  147.66  4100.9  148.25  4391.7  148.28
  4612.7  146.88  4842.7  150.75  4979.1  148.73    4990  140.03  5004.1   137.5
  5027.4  148.65  5167.3  147.22  5427.8  148.56  5662.8  146.48  5767.8  149.28
  6105.7  150.08    6322  150.21  6767.8  150.79  6977.8  155.99  7876.6  154.83
#Mann= 17 ,-1 , 0
  1572.7     .09       0  1610.8     .05       0  1764.1     .09       0
    2018     .08       0  2133.7     .05       0  2243.1      .1       0
  2287.6      .1       0  3059.5      .1       0  3180.7     .05       0
    3310     .12       0  4100.9     .11       0  4391.7     .12       0
  4979.1     .08       0  5027.4     .12       0  5167.3     .12       0
  6105.7     .12       0    6322     .11       0
#XS Ineff= 1 ,-1
 1872.61    3000  157.22
Permanent Ineff=
       F
Bank Sta=4979.1,5027.4
XS Rating Curve= 0 ,0
Exp/Cntr=0.5,0.3

Type RM Length L Ch R = 1 ,40192   ,76,73,77
BEGIN DESCRIPTION:
40192
END DESCRIPTION:
XS GIS Cut Line= 6
      1936420.85       322430.81      1936226.48       322046.31
      1935700.95       320457.94      1935516.59       318625.74
        1934555.       317490.99      1933614.06       316636.47
#Sta/Elev= 30
   934.6  153.82  1099.6  153.48  1390.4  154.69  1595.4  150.04  1808.5  147.74
  2223.5  151.76  2538.5  148.86  3018.5  147.38  3158.5  148.77  3351.5  147.09
  4572.7  148.15  4839.6   145.4  4958.1  146.15  4965.7  144.73  4978.3  140.78
  4984.4  137.19  5012.6  136.34  5015.7  137.65  5016.6  135.72  5020.5  139.54
  5023.5  138.44  5031.5  141.23  5037.4  146.04    5234  144.98  5380.6  147.56
  5739.8  149.48  6134.8  147.46    6420  150.15  7116.4  150.51  7648.2  154.69
#Mann= 4 ,-1 , 0
   934.6     .09       0  1099.6      .1       0  4965.7     .08       0
  5037.4      .1       0
#XS Ineff= 5 ,-1
 5670.61  7330.3  152.42  960.87    2450     154    2452    4572  147.77
  5039.4 5670.61  146.36    4572  4961.1  146.36
Permanent Ineff=
       F       F       F       F       F
Bank Sta=4965.7,5037.4
XS Rating Curve= 0 ,0
Exp/Cntr=0.5,0.3

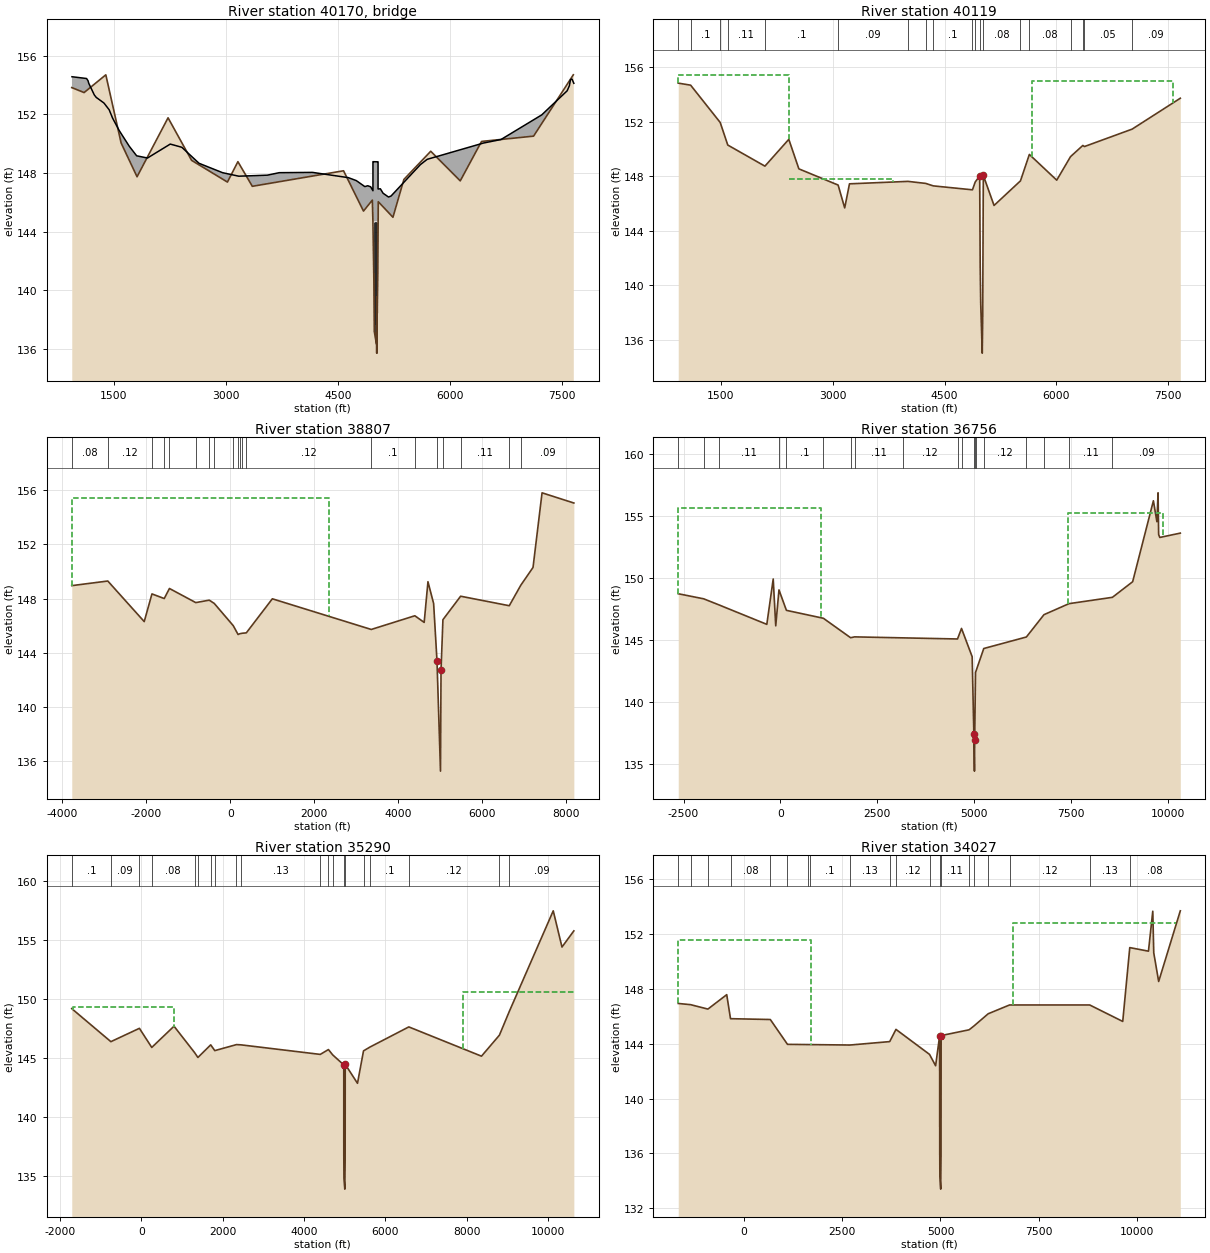
Type RM Length L Ch R = 3 ,40170   ,,,
BEGIN DESCRIPTION:
Henry Berry Rd (SR 1157),  R_BAS_08
END DESCRIPTION:
Bridge Culvert--1,0,-1,-1, 0
Deck Dist Width WeirC Skew NumUp NumDn MinLoCord MaxHiCord MaxSubmerge Is_Ogee
6.5,31,3,0, 48, 48, , , 0.95, 0, 1,1,,
   937.2  1132.2  1152.2  1162.2  1237.2  1262.2    1365    1435    1480    1570
  1703.1  1803.1  1948.1  2253.1  2408.1  2638.1  2953.1  3170.4  3551.5  3711.5
  4156.5  4638.2  4743.2  4857.9    4896  4935.3  4966.2  4966.2  4967.6  4967.6
  5032.9  5032.9  5034.5  5034.5  5065.6  5101.7  5174.2  5208.7  5601.2  5692.3
    6445    6680  7225.7  7565.7  7595.7  7610.7  7630.7  7655.4
  154.56  154.44  154.29  154.11  153.31  153.15  152.77  152.31  151.75  150.89
  149.83  149.17  149.02  149.97  149.75  148.66  148.02  147.78  147.85  148.02
  148.04  147.68  147.48  147.07  147.13  147.06  146.79  148.77  148.77  148.77
  148.76  148.76  148.76  146.91  146.92  146.62  146.36  146.43  148.57  148.93
  150.04  150.28  151.96   153.6  153.95  154.37   154.4  154.11
  115.72  115.72  115.72  115.72  115.72  115.72  115.72  115.72  115.72  115.72
  115.72  115.72  115.72  115.72  115.72  115.72  115.72  115.72  115.72  115.72
  115.72  115.72  115.72  115.72  115.72  115.72  115.72  115.72  115.72  144.69
  144.69  115.72  115.72  115.72  115.72  115.72  115.72  115.72  115.72  115.72
  115.72  115.72  115.72  115.72  115.72  115.72  115.72  115.72
   937.2  1132.2  1152.2  1162.2  1237.2  1262.2    1365    1435    1480    1570
  1703.1  1803.1  1948.1  2253.1  2408.1  2638.1  2953.1  3170.4  3551.5  3711.5
  4156.5  4638.2  4743.2  4857.9    4896  4935.3  4966.2  4966.2  4967.6  4967.6
  5032.9  5032.9  5034.5  5034.5  5065.6  5101.7  5174.2  5208.7  5601.2  5692.3
    6445    6680  7225.7  7565.7  7595.7  7610.7  7630.7  7655.4
  154.56  154.44  154.29  154.11  153.31  153.15  152.77  152.31  151.75  150.89
  149.83  149.17  149.02  149.97  149.75  148.66  148.02  147.78  147.85  148.02
  148.04  147.68  147.48  147.07  147.13  147.06  146.79  148.77  148.77  148.77
  148.76  148.76  148.76  146.91  146.92  146.62  146.36  146.43  148.57  148.93
  150.04  150.28  151.96   153.6  153.95  154.37   154.4  154.11
  115.72  115.72  115.72  115.72  115.72  115.72  115.72  115.72  115.72  115.72
  115.72  115.72  115.72  115.72  115.72  115.72  115.72  115.72  115.72  115.72
  115.72  115.72  115.72  115.72  115.72  115.72  115.72  115.72  115.72  144.69
  144.69  115.72  115.72  115.72  115.72  115.72  115.72  115.72  115.72  115.72
  115.72  115.72  115.72  115.72  115.72  115.72  115.72  115.72
Pier Skew, UpSta & Num, DnSta & Num=  ,4984.5, 2 ,4984.5, 2 , 0 , 0 , 0 ,0,0
       1       1
  137.19  144.69
       1       1
  138.58  144.69
Pier Skew, UpSta & Num, DnSta & Num=  ,5000.2, 2 ,5000.2, 2 , 0 , 0 , 0 ,0,0
       1       1
  136.38  144.69
       1       1
  137.77  144.69
Pier Skew, UpSta & Num, DnSta & Num=  ,5016.6, 2 ,5016.6, 2 , 0 , 0 , 0 ,0,0
       1       1
  135.72  144.69
       1       1
  137.11  144.69
Abutment Skew #Up #Dn= , 2 , 2
  4967.6  4982.8
  144.69  138.88
  4967.6  4982.8
  144.69  140.27
Abutment Skew #Up #Dn= , 2 , 2
  5023.5  5032.9
  138.44  144.69
  5023.5  5032.9
  139.83  144.69
BR Coef= 1 , 1 , 0 ,0.9, 0 ,,,0.8,0,1.2,0,
WSPro=,,,, 1 ,,,, 0 ,,,, 0 ,,,,-1 ,-1 ,-1 , 0 , 0 , 0 , 0 , 0
BC Design=,, 0 ,, 0 ,,,,,,
BC HTab HWMax=154.7
BC Use User HTab Curves=0
BC User HTab FreeFlow(D)= 0

Type RM Length L Ch R = 1 ,40119   ,1309,1312,1305
BEGIN DESCRIPTION:
40119
END DESCRIPTION:
XS GIS Cut Line= 6
      1936508.16       322372.66      1935797.73       320432.03
      1935698.11       318981.82      1935593.63       318619.65
      1934628.25       317422.86      1933676.83       316558.63
#Sta/Elev= 30
   926.4  154.84  1092.7  154.69  1489.3  151.95  1590.9  150.29  2089.2  148.74
  2409.5  150.71  2544.5  148.54    3071  147.35  3159.1  145.67  3223.3  147.44
  4007.9  147.62  4246.5  147.47  4346.7  147.29  4872.9     147  4909.3  147.57
  4969.5  148.02  4976.7  141.34  4983.4  138.66  5004.1     135    5010  137.52
 5018.51  148.06  5162.4  145.85  5516.9  147.66  5636.1   149.6    6003  147.71
  6188.5  149.44  6353.2  150.26  6374.9  150.18  7014.7  151.46  7660.7  153.73
#Mann= 19 ,-1 , 0
   926.4     .09       0  1092.7      .1       0  1489.3     .05       0
  1590.9     .11       0  2089.2      .1       0    3071     .09       0
  4007.9     .08       0  4246.5     .05       0  4346.7      .1       0
  4872.9     .05       0  4909.3     .08       0  4969.5     .08       0
 5018.51     .08       0  5516.9     .05       0  5636.1     .08       0
  6188.5      .1       0  6353.2     .09       0  6374.9     .05       0
  7014.7     .09       0
#XS Ineff= 5 ,-1
   926.4 2409.46  155.45 5670.61 7563.24  155.03 2413.71    3808  147.82
  5172.9    5534  144.69    3808  4827.6  144.69
Permanent Ineff=
       F       F       F       F       F
Bank Sta=4969.5,5018.51
XS Rating Curve= 0 ,0
Exp/Cntr=0.5,0.3

Type RM Length L Ch R = 1 ,38807   ,1963,2051,2022
BEGIN DESCRIPTION:
38807
END DESCRIPTION:
XS GIS Cut Line= 3
      1940624.69       325803.23      1936701.97       317941.23
      1934826.97       315389.15
#Sta/Elev= 30
 -3774.3  148.96 -2916.5   149.3 -2049.3  146.31 -1865.3  148.35   -1573  148.01
 -1448.9  148.75  -822.2  147.71  -500.9  147.89  -382.7  147.65    70.3  146.01
   184.9  145.36   220.9  145.41   280.1  145.45   381.2  145.48  1000.7  147.99
  3355.4  145.73  4393.3  146.74  4615.7  146.25  4705.7  149.25  4840.7  147.64
  4920.7  143.42  5004.1  135.29    5017  142.75    5062  146.45  5483.3  148.18
  6641.5  147.48  6915.7  148.99    7207   150.3    7422   155.8  8178.8  155.05
#Mann= 20 ,-1 , 0
 -3774.3     .08       0 -2916.5     .12       0 -1865.3      .1       0
   -1573     .05       0 -1448.9     .11       0  -822.2      .1       0
  -500.9     .05       0  -382.7     .08       0    70.3     .05       0
   184.9     .09       0   220.9      .1       0   280.1     .05       0
   381.2     .12       0  3355.4      .1       0  4393.3     .12       0
  4920.7     .08       0    5062     .12       0  5483.3     .11       0
  6641.5      .1       0  6915.7     .09       0
#XS Ineff= 1 ,-1
 -3774.3 2343.95  155.42
Permanent Ineff=
       F
Bank Sta=4920.7,5017
XS Rating Curve= 0 ,0
Exp/Cntr=0.3,0.1

Type RM Length L Ch R = 1 ,36756   ,1465,1466,1477
BEGIN DESCRIPTION:
36756-LiDAR artifacts removed from left and right overbank
END DESCRIPTION:
XS GIS Cut Line= 3
      1941617.93       325623.37      1938420.72       318748.53
       1935582.2       314191.27
#Sta/Elev= 30
 -2636.6  148.71 -1980.5   148.3 -1586.5  147.81  -351.6  146.24  -186.6   149.9
  -121.6  146.12   -38.1  149.02   153.8  147.37  1107.7  146.73  1810.2  145.16
  1911.1  145.23  4567.4  145.06  4670.6  145.91  4945.3  143.63  4989.1  137.36
  5004.1   134.4    5010  136.92  5031.9  142.36  5244.3  144.29  6343.9  145.22
  6797.3  147.02  7443.5  147.91  8562.8  148.42  9085.3  149.68  9620.3  156.21
  9710.3  154.52  9740.3  156.85  9755.3  153.49  9785.3  153.25 10314.3   153.6
#Mann= 19 ,-1 , 0
 -2636.6     .08       0 -1980.5      .1       0 -1586.5     .11       0
   -38.1     .05       0   153.8      .1       0  1107.7     .11       0
  1810.2     .05       0  1911.1     .11       0  3166.4     .12       0
  4567.4     .05       0  4670.6     .12       0  4989.1     .08       0
    5010    .045       0  5031.9     .11       0  5244.3     .12       0
  6343.9     .11       0  6797.3     .12       0  7443.5     .11       0
  8562.8     .09       0
#XS Ineff= 2 ,-1
 -2636.6 1051.87  155.62 7428.57 9874.43  155.21
Permanent Ineff=
       F       F
Bank Sta=4989.1,5010
XS Rating Curve= 0 ,0
Exp/Cntr=0.3,0.1

Type RM Length L Ch R = 1 ,35290   ,1260,1263,1275
BEGIN DESCRIPTION:
35290
END DESCRIPTION:
XS GIS Cut Line= 3
      1942486.77       324033.51      1939644.67       317941.23
      1936571.78       313227.73
#Sta/Elev= 30
 -1709.1   149.2  -747.1   146.4   -45.2  147.53   258.4  145.91   805.9  147.71
  1312.8  145.47  1393.5  145.06  1708.3  146.13  1808.5  145.64  2342.1  146.15
  2451.8  146.13  4402.7  145.32  4603.9  145.73  4708.6  145.28  4981.1  144.43
  4981.9  136.89  4985.7  134.81  5006.9   133.9  5014.8   136.3  5017.2  144.48
  5318.5  142.87  5466.9  145.62  5629.4  145.95  6581.1  147.65  8368.5  145.17
  8809.6  146.95  9047.5  148.92 10133.5  157.49 10348.5  154.42 10640.2  155.79
#Mann= 20 ,-1 , 0
 -1709.1      .1       0  -747.1     .09       0   -45.2     .05       0
   258.4     .08       0  1312.8      .1       0  1393.5     .06       0
  1708.3     .05       0  1808.5     .09       0  2342.1     .05       0
  2451.8     .13       0  4402.7     .11       0  4603.9     .05       0
  4708.6     .12       0  4981.1     .08       0  5017.2     .12       0
  5466.9     .11       0  5629.4      .1       0  6581.1     .12       0
  8809.6     .11       0  9047.5     .09       0
#XS Ineff= 2 ,-1
  7919.6 10640.2150.5842-1681.03  814.07149.3451
Permanent Ineff=
       F       F
Bank Sta=4981.1,5017.2
XS Rating Curve= 0 ,0
Exp/Cntr=0.3,0.1

Type RM Length L Ch R = 1 ,34027   ,1383,1410,1517
BEGIN DESCRIPTION:
34027 - LiDAR artifacts removed from left overbank
END DESCRIPTION:
XS GIS Cut Line= 3
      1943336.42       323454.35      1940738.42       317316.23
      1938264.45       311717.25
#Sta/Elev= 30
 -1677.6  146.93 -1359.8  146.84  -921.9  146.52  -442.6  147.57  -346.3  145.82
   667.3  145.76  1104.7  143.95  2694.4   143.9  3707.9  144.15  3867.4  145.04
  4721.5  143.22  4877.4  142.39  4979.4  144.57  4981.9  136.39  4985.7  134.31
  5006.9   133.4  5014.8   135.8  5017.9  144.59  5729.7  145.01  5849.9  145.28
  6216.7  146.18  6760.5  146.82  8801.4  146.82  9642.7  145.62  9821.8     151
 10297.7  150.74 10407.7  153.65 10432.7  150.62 10557.7  148.53 11108.9  153.68
#Mann= 20 ,-1 , 0
 -1677.6     .09       0 -1359.8     .12       0  -921.9      .1       0
  -346.3     .08       0   667.3      .1       0  1104.7     .05       0
  1626.4     .08       0  1680.8      .1       0  2694.4     .13       0
  3707.9      .1       0  3867.4     .12       0  4721.5     .11       0
  4979.4     .08       0  5017.9     .11       0  5729.7     .05       0
  5849.9     .11       0  6216.7      .1       0  6760.5     .12       0
  8801.4     .13       0  9821.8     .08       0
#XS Ineff= 2 ,-1
 6851.4511010.87  152.78 -1677.6 1715.58  151.56
Permanent Ineff=
       F       F
Bank Sta=4979.4,5017.9
XS Rating Curve= 0 ,0
Exp/Cntr=0.5,0.3

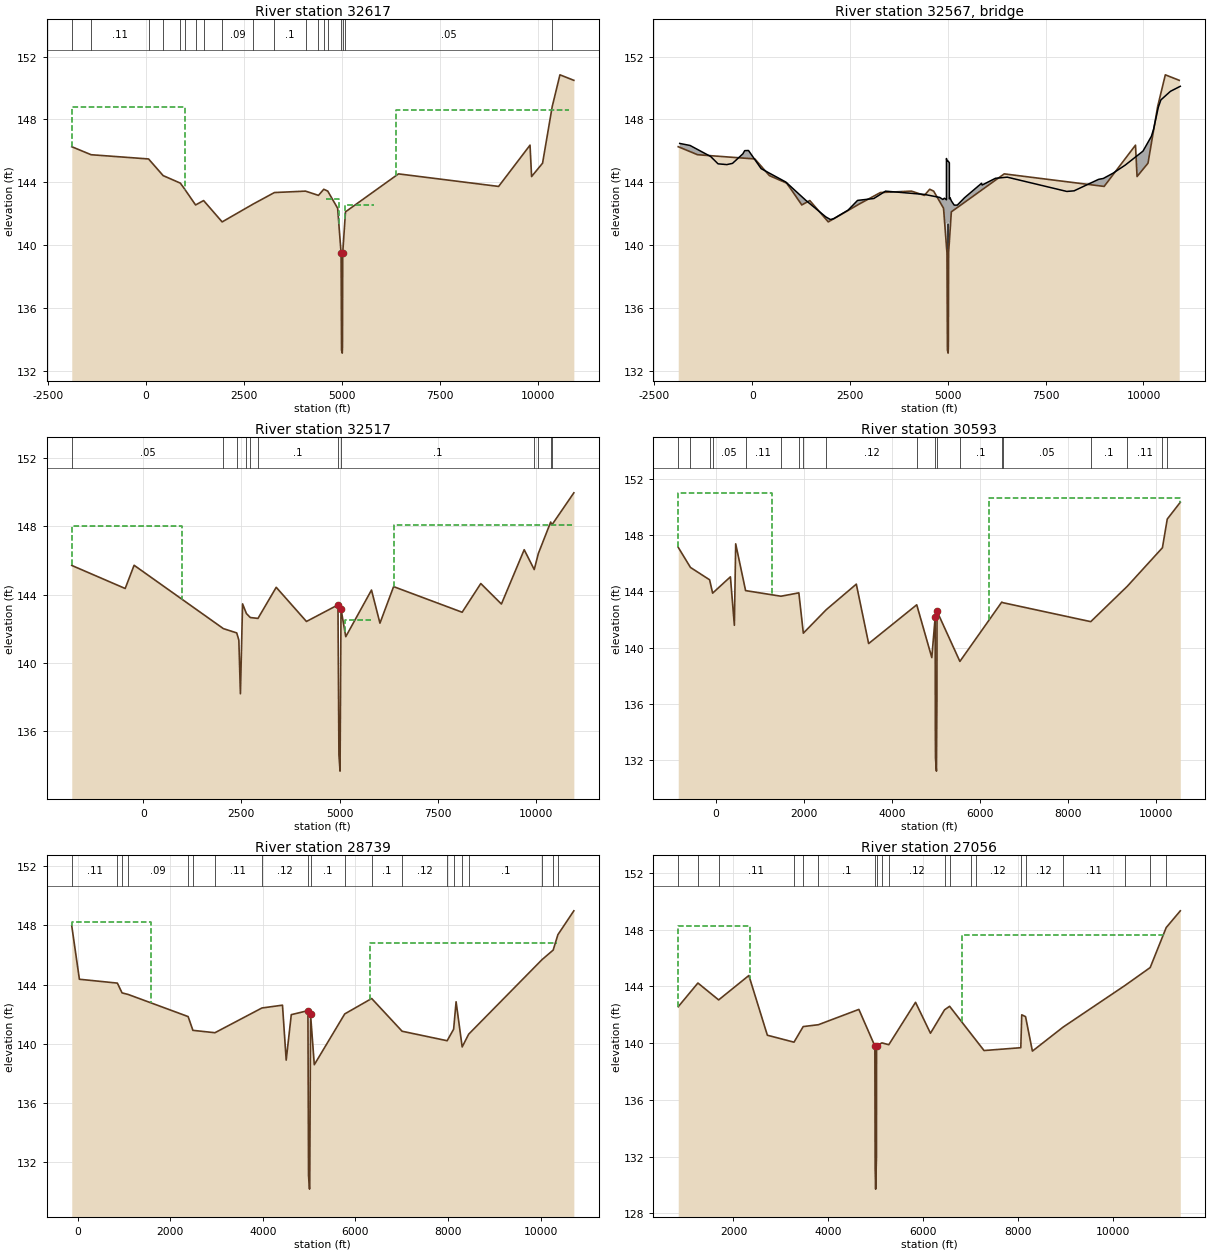
Type RM Length L Ch R = 1 ,32617   ,101,100,100
BEGIN DESCRIPTION:
32617
END DESCRIPTION:
XS GIS Cut Line= 6
      1944847.04       322698.65      1944241.04       319360.86
      1942031.91       317032.96      1942016.79       314588.63
      1942404.76       312255.95      1941813.75       311082.25
#Sta/Elev= 30
 -1892.6  146.26   -1399  145.75    66.4  145.48   437.7  144.42   877.1  143.94
   984.2  143.57  1265.7  142.55  1470.3  142.83  1943.2  141.47  2736.6  142.61
  3276.1  143.34  4071.1  143.43  4400.3  143.16  4535.7  143.55  4637.1  143.43
  4889.6  142.34  4977.2  139.49  4988.7  133.31  5006.9  133.11  5012.4  133.51
  5019.5  139.52  5089.1  142.11  6441.1  144.53  8995.2  143.73  9796.6  146.36
  9836.6  144.36 10116.3  145.21   10362  148.81 10559.4  150.84 10914.3  150.49
#Mann= 19 ,-1 , 0
 -1892.6     .09       0   -1399     .11       0    66.4     .05       0
   437.7      .1       0   877.1     .05       0   984.2     .09       0
  1265.7     .05       0  1470.3     .06       0  1943.2     .09       0
  2736.6     .08       0  3276.1      .1       0  4071.1     .05       0
  4400.3     .08       0  4535.7     .05       0  4637.1     .12       0
  4977.2     .08       0  5019.5     .12       0  5089.1     .05       0
   10362     .08       0
#XS Ineff= 4 ,-1
 -1892.6    1000  148.78  6372.710786.57  148.57  4590.5  4925.1   142.9
  5077.7    5814  142.54
Permanent Ineff=
       F       F       F       F
Bank Sta=4977.2,5019.5
XS Rating Curve= 0 ,0
Exp/Cntr=0.5,0.3

Type RM Length L Ch R = 3 ,32567   ,,,
BEGIN DESCRIPTION:
S Chicken Rd (SR 1003),  R_BAS_07
END DESCRIPTION:
Bridge Culvert--1,0,-1,-1, 0
Deck Dist Width WeirC Skew NumUp NumDn MinLoCord MaxHiCord MaxSubmerge Is_Ogee
34.5,31,3,0, 55, 55, 142.54, , 0.95, 0, 1,1,,
 -1855.3 -1590.3 -1065.7  -875.2  -650.2  -505.2  -239.2  -194.2   -96.9   228.1
   858.1  1371.1  1879.3  1999.3  2084.3  2449.3  2691.4  3106.4  3406.4  4401.4
    4791  4872.5  4910.8  4963.8  4963.8  4965.1  4965.1  4978.6  5004.1  5037.7
  5037.7  5038.7  5038.7  5055.6  5091.7  5162.5  5240.9  5425.9  5860.9  5875.9
  6217.8  6517.6  8041.7  8226.7  8851.7  8975.2  9220.2  9535.2  9987.7   10202
 10260.2 10380.2 10445.2 10690.2 10942.2
  146.47  146.34  145.64  145.17  145.12   145.2  145.81  146.01  146.02  144.86
  144.01  142.84  141.79  141.62  141.68  142.22  142.84  142.96  143.43  143.22
  143.03   142.9  142.98  142.88  145.51  145.49  145.49  145.33  145.35  145.24
  145.24  145.23  142.94  143.01   142.8  142.54  142.54  143.01  143.93  143.82
  144.25  144.32  143.41  143.45  144.18  144.24  144.57  145.09  145.98  146.92
  147.39  148.78  149.24  149.79  150.11
   112.9   112.9   112.9   112.9   112.9   112.9   112.9   112.9   112.9   112.9
   112.9   112.9   112.9   112.9   112.9   112.9   112.9   112.9   112.9   112.9
   112.9   112.9   112.9   112.9   112.9   112.9  141.38  141.39  141.41  141.44
   112.9   112.9   112.9   112.9   112.9   112.9   112.9   112.9   112.9   112.9
   112.9   112.9   112.9   112.9   112.9   112.9   112.9   112.9   112.9   112.9
   112.9   112.9   112.9   112.9   112.9
 -1855.3 -1590.3 -1065.7  -875.2  -650.2  -505.2  -239.2  -194.2   -96.9   228.1
   858.1  1371.1  1879.3  1999.3  2084.3  2449.3  2691.4  3106.4  3406.4  4401.4
    4791  4872.5  4910.8  4963.8  4963.8  4965.1  4965.1  4978.6  5004.1  5037.7
  5037.7  5038.7  5038.7  5055.6  5091.7  5162.5  5240.9  5425.9  5860.9  5875.9
  6217.8  6517.6  8041.7  8226.7  8851.7  8975.2  9220.2  9535.2  9987.7   10202
 10260.2 10380.2 10445.2 10690.2 10942.2
  146.47  146.34  145.64  145.17  145.12   145.2  145.81  146.01  146.02  144.86
  144.01  142.84  141.79  141.62  141.68  142.22  142.84  142.96  143.43  143.22
  143.03   142.9  142.98  142.88  145.51  145.49  145.49  145.33  145.35  145.24
  145.24  145.23  142.94  143.01   142.8  142.54  142.54  143.01  143.93  143.82
  144.25  144.32  143.41  143.45  144.18  144.24  144.57  145.09  145.98  146.92
  147.39  148.78  149.24  149.79  150.11
   112.9   112.9   112.9   112.9   112.9   112.9   112.9   112.9   112.9   112.9
   112.9   112.9   112.9   112.9   112.9   112.9   112.9   112.9   112.9   112.9
   112.9   112.9   112.9   112.9   112.9   112.9  141.38  141.39  141.41  141.44
   112.9   112.9   112.9   112.9   112.9   112.9   112.9   112.9   112.9   112.9
   112.9   112.9   112.9   112.9   112.9   112.9   112.9   112.9   112.9   112.9
   112.9   112.9   112.9   112.9   112.9
Pier Skew, UpSta & Num, DnSta & Num=  ,4989.1, 2 ,4989.1, 2 , 0 , 0 , 0 ,0,0
       1       1
  134.02   141.4
       1       1
  134.79   141.4
Pier Skew, UpSta & Num, DnSta & Num=  ,5013.8, 2 ,5013.8, 2 , 0 , 0 , 0 ,0,0
       1       1
   132.9  141.42
       1       1
  133.67  141.42
Abutment Skew #Up #Dn= , 2 , 2
  4965.1    4982
  141.38  135.54
  4965.1    4982
  141.38  136.31
Abutment Skew #Up #Dn= , 2 , 2
  5019.2  5037.7
  134.61  141.44
  5019.2  5037.7
  135.38  141.44
BR Coef= 1 , 1 , 0 ,0.9, 0 ,,,0.8,0,1.2,0,
WSPro=,,,, 1 ,,,, 0 ,,,, 0 ,,,,-1 ,-1 ,-1 , 0 , 0 , 0 , 0 , 0
BC Design=,, 0 ,, 0 ,,,,,,
BC HTab HWMax=150.84
BC Use User HTab Curves=0
BC User HTab FreeFlow(D)= 0

Type RM Length L Ch R = 1 ,32517   ,1953,1924,1887
BEGIN DESCRIPTION:
32517
END DESCRIPTION:
XS GIS Cut Line= 6
      1944931.15       322633.08      1944330.26        319314.1
      1942128.18       317004.08      1942116.52       314598.53
      1942505.43       312260.13      1941902.01       311035.25
#Sta/Elev= 30
 -1819.4  145.71  -458.6  144.36  -231.8  145.72  2043.3  142.01  2382.4  141.76
  2436.1  141.34  2476.1   138.2  2531.1  143.46  2629.8  142.89  2728.8  142.66
  2923.7  142.61  3388.1  144.43  4158.1  142.43  4960.8   143.4    4985  134.63
  5013.8  133.67  5038.4  143.16  5159.5  141.54  5814.8  144.27  6030.2  142.33
  6377.8  144.47  8123.7  142.97  8598.7  144.65  9123.9  143.45  9704.2  146.63
  9959.8  145.47 10064.9  146.41 10378.9  148.25 10408.8  148.08 10968.7  149.96
#Mann= 12 ,-1 , 0
 -1819.4     .05       0  2043.3     .09       0  2382.4     .05       0
  2629.8     .09       0  2728.8     .08       0  2923.7      .1       0
  4960.8     .08       0  5038.4      .1       0  9959.8     .11       0
 10064.9     .05       0 10378.9     .09       0 10408.8     .08       0
#XS Ineff= 5 ,-1
 6387.8710923.08  148.09-1817.98    1000     148 5805.76 6387.87  143.49
  5137.7 5805.76  142.54    1000  4865.1  142.54
Permanent Ineff=
       F       F       F       F       F
Bank Sta=4960.8,5038.4
XS Rating Curve= 0 ,0
Exp/Cntr=0.5,0.3

Type RM Length L Ch R = 1 ,30593   ,1814,1854,1694
BEGIN DESCRIPTION:
30593
END DESCRIPTION:
XS GIS Cut Line= 3
      1946140.53       321546.83      1943707.17       316274.57
      1942639.46       310779.76
#Sta/Elev= 30
    -858  147.13  -580.6   145.7  -145.6  144.82   -76.6  143.87     327  145.03
     417  141.58     447  147.38   672.1  144.05  1475.4  143.65  1881.6  143.89
  1983.8  141.02  2503.4  142.69    3187  144.51    3467  140.28  4559.4  143.04
    4902  139.28  4978.2  142.17  4981.9  134.19  4985.7  132.11  5006.9   131.2
  5018.2  136.15  5020.1  142.58  5539.5  139.01  6490.3  143.23  6516.5  143.19
  8512.2  141.84  9342.8  144.36   10140   147.1 10249.8  149.14 10546.3  150.34
#Mann= 19 ,-1 , 0
    -858     .08       0  -580.6     .11       0  -145.6     .12       0
   -76.6     .05       0   672.1     .11       0  1475.4     .12       0
  1881.6     .05       0  1983.8     .09       0  2503.4     .12       0
  4559.4     .11       0  4978.2     .08       0  5020.1     .11       0
  5539.5      .1       0  6490.3     .09       0  6516.5     .05       0
  8512.2      .1       0  9342.8     .11       0   10140     .05       0
 10249.8     .09       0
#XS Ineff= 2 ,-1
    -858 1271.74  151.01 6204.7110528.99  150.62
Permanent Ineff=
       F       F
Bank Sta=4978.2,5020.1
XS Rating Curve= 0 ,0
Exp/Cntr=0.3,0.1

Type RM Length L Ch R = 1 ,28739   ,1708,1683,1916
BEGIN DESCRIPTION:
28739
END DESCRIPTION:
XS GIS Cut Line= 3
      1947256.17       320406.82      1945243.63       315701.65
      1943082.17       310389.14
#Sta/Elev= 30
  -132.3  147.97    32.7  144.37   853.9  144.11   954.3  143.45  1090.3  143.34
    2383  141.85  2486.3  140.92  2962.5  140.76  3977.6  142.43  4422.7  142.62
  4502.7  138.91  4612.7  141.98  4972.7  142.25  4985.7  131.11  5006.9   130.2
  5012.4   130.6  5028.8  142.01  5110.2   138.6  5768.3  142.03  6350.7  143.07
  7008.1  140.86  7982.3  140.22  8122.3     141  8175.2  142.85  8306.8   139.8
  8446.9  140.66 10031.2  145.69 10273.6  146.34   10376  147.38 10720.6  148.99
#Mann= 20 ,-1 , 0
  -132.3     .11       0   853.9     .05       0   954.3     .12       0
  1090.3     .09       0    2383     .05       0  2486.3      .1       0
  2962.5     .11       0  3977.6     .12       0  4972.7     .08       0
  5028.8      .1       0  5768.3     .05       0  6350.7      .1       0
  7008.1     .12       0  7982.3     .05       0  8122.3      .1       0
  8306.8     .05       0  8446.9      .1       0 10031.2     .09       0
 10273.6     .05       0   10376      .1       0
#XS Ineff= 2 ,-1
  -132.3 1576.09  148.22 6306.1610364.13  146.83
Permanent Ineff=
       F       F
Bank Sta=4972.7,5028.8
XS Rating Curve= 0 ,0
Exp/Cntr=0.3,0.1

Type RM Length L Ch R = 1 ,27056   ,1711,1665,1646
BEGIN DESCRIPTION:
27056
END DESCRIPTION:
XS GIS Cut Line= 3
      1948833.29       319251.71       1946910.3        315545.4
      1943652.51        310019.4
#Sta/Elev= 30
   834.4  142.56  1249.5  144.23  1687.1  143.04  2324.4  144.76  2714.4  140.55
  3276.1  140.06  3470.2  141.16  3790.2  141.29  4644.4  142.37  4981.8  139.79
  4988.1  131.15  4998.3   129.7  5015.3  131.92  5017.4  139.81  5131.1  140.01
  5275.5  139.88  5839.9  142.87  6154.9  140.69  6451.3  142.34  6558.5  142.59
  7284.9  139.47  8060.1  139.67  8079.9  141.99  8160.2  141.86  8304.9  139.43
  8951.3  141.12 10254.2  144.05 10789.2  145.32 11127.4  148.14 11424.7  149.32
#Mann= 20 ,-1 , 0
   834.4      .1       0  1249.5     .13       0  1687.1     .11       0
  3276.1     .05       0  3470.2     .11       0  3790.2      .1       0
  4981.8     .08       0  5017.4     .11       0  5131.1     .13       0
  5275.5     .12       0  6451.3     .05       0  6558.5     .11       0
  7003.6     .13       0  7113.4     .12       0  8060.1     .05       0
  8160.2     .12       0  8951.3     .11       0 10254.2     .09       0
 10789.2     .07       0 11127.4      .1       0
#XS Ineff= 2 ,-1
   834.4 2347.83  148.23 6815.2211119.57   147.6
Permanent Ineff=
       F       F
Bank Sta=4981.8,5017.4
XS Rating Curve= 0 ,0
Exp/Cntr=0.3,0.1