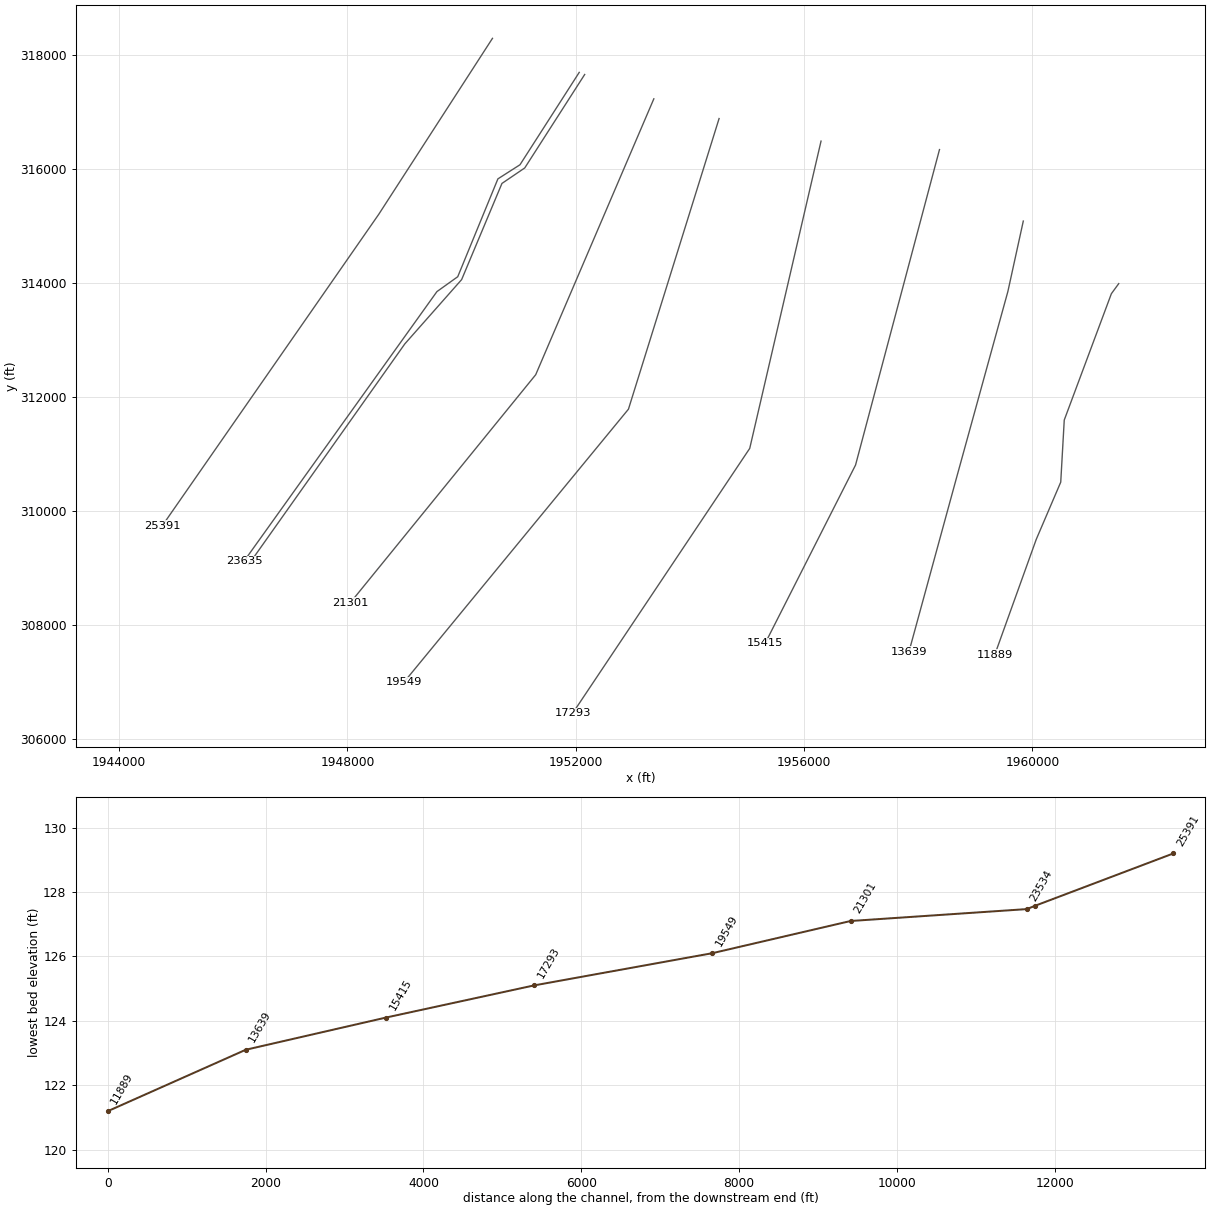
HEC-RAS study BackSwamp.prj: Back Swamp Detailed Study

--- BackSwamp.g01 (geometry) --- (continued)

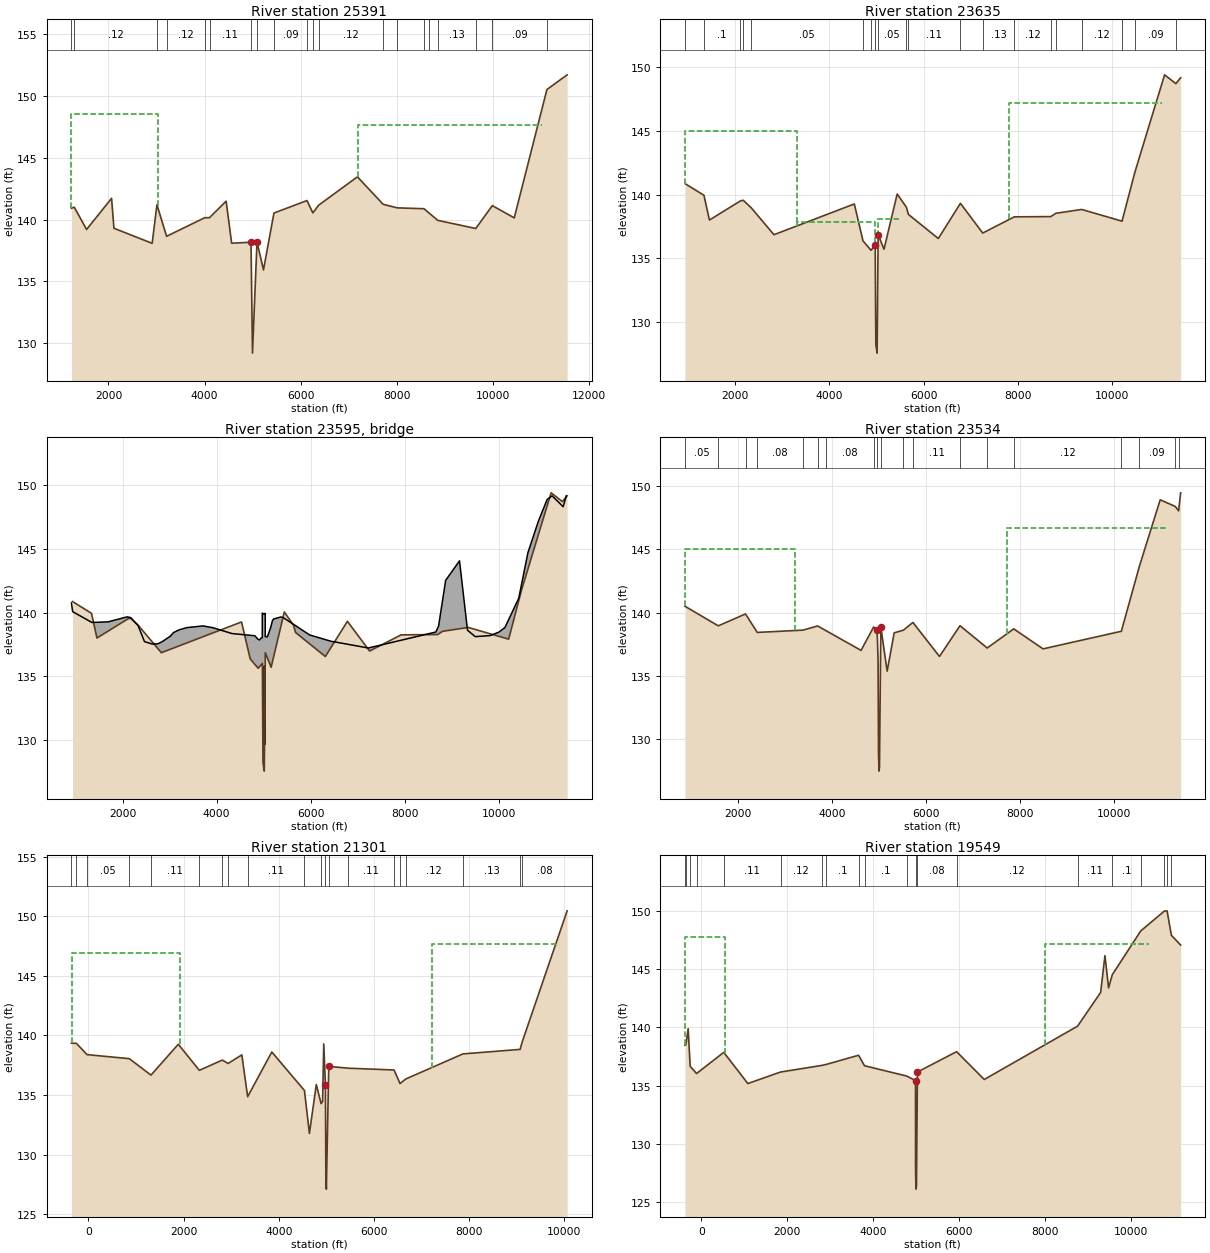
Type RM Length L Ch R = 1 ,25391   ,1694,1756,1777
BEGIN DESCRIPTION:
25391 - LiDAR artifacts removed from right overbank
END DESCRIPTION:
XS GIS Cut Line= 3
      1950540.96       318291.92      1948548.32       315206.86
      1944756.65       309748.52
#Sta/Elev= 30
  1229.6  140.92  1288.7     141  1544.6   139.2  2064.6  141.72  2114.6   139.3
  2909.6  138.08    3009   141.2  3210.4  138.65  4003.2  140.15  4104.1  140.16
  4449.6  141.49  4564.6  138.09  4967.2  138.17  4998.3   129.2  5092.2   138.2
  5227.2  135.93  5444.8  140.53  6132.8  141.54  6254.5  140.54  6373.8  141.16
  7182.2  143.46  7717.7  141.24  8009.9  140.95  8568.8  140.88  8854.2  139.94
  9645.9  139.28  9990.7  141.13 10447.2  140.14 11127.2  150.52 11548.3  151.71
#Mann= 20 ,-1 , 0
  1229.6     .08       0  1288.7     .12       0    3009     .13       0
  3210.4     .12       0  4003.2     .05       0  4104.1     .11       0
  4967.2     .08       0  5092.2     .11       0  5444.8     .09       0
  6132.8     .05       0  6254.5     .08       0  6373.8     .12       0
  7717.7     .13       0  8009.9     .12       0  8568.8     .05       0
  8668.8     .12       0  8854.2     .13       0  9645.9     .11       0
  9990.7     .09       0 11127.2     .07       0
#XS Ineff= 2 ,-1
  1229.6 3021.74  148.58 7184.7811021.74  147.67
Permanent Ineff=
       F       F
Bank Sta=4967.2,5092.2
XS Rating Curve= 0 ,0
Exp/Cntr=0.5,0.3

Type RM Length L Ch R = 1 ,23635   ,144,101,85
BEGIN DESCRIPTION:
23635 - LiDAR artifacts removed from overbanks
END DESCRIPTION:
XS GIS Cut Line= 6
      1952060.93       317694.95      1951022.95       316075.49
      1950635.97         315828.      1949932.35       314112.62
      1949567.53       313851.58       1946186.5       309123.28
#Sta/Elev= 30
   934.3  140.86  1338.2  139.94  1454.3     138    2113   139.5  2171.8  139.55
  2345.9  138.94  2823.7  136.85  4529.6  139.26  4713.6  136.37  4883.3  135.63
  4972.4  136.01  4985.9  128.23  5012.9  127.57  5035.1  136.85  5159.3  135.71
  5439.4  140.04  5635.5     139  5677.9  138.44  6312.4  136.55  6781.7  139.31
  7254.5  136.98  7924.9  138.25    8699  138.27  8809.9  138.53  9354.7  138.83
 10211.5  137.91 10487.2  141.78 11114.7  149.38 11354.7  148.69 11455.5  149.15
#Mann= 20 ,-1 , 0
   934.3     .05       0  1338.2      .1       0    2113     .11       0
  2171.8     .09       0  2345.9     .05       0  4713.6     .08       0
  4883.3     .05       0  4972.4     .08       0  5035.1     .05       0
  5635.5     .12       0  5677.9     .11       0  6781.7     .12       0
  7254.5     .13       0  7924.9     .12       0    8699     .05       0
  8809.9     .11       0  9354.7     .12       0 10211.5     .11       0
 10487.2     .09       0 11354.7     .08       0
#XS Ineff= 4 ,-1
    3320 4971.27  137.84 5042.13 5467.39   138.1 7816.7911053.44  147.19
     500    3320     145
Permanent Ineff=
       F       F       F       F
Bank Sta=4972.4,5035.1
XS Rating Curve= 0 ,0
Exp/Cntr=0.5,0.3

Type RM Length L Ch R = 3 ,23595   ,,,
BEGIN DESCRIPTION:
Addison Tram Rd (SR 1160),  R_BAS_06
END DESCRIPTION:
Bridge Culvert--1,0,-1,-1, 0
Deck Dist Width WeirC Skew NumUp NumDn MinLoCord MaxHiCord MaxSubmerge Is_Ogee
10,30,3,0, 56, 56, 137.85, , 0.95, 0, 1,1,,
   911.7   936.7  1346.7  1691.7  2096.7  2171.7  2326.7  2465.1  2630.1  2750.1
  2835.1  3012.6    3084    3199  3370.4  3711.6  3921.6  4326.6  4812.1  4881.3
  4913.8  4947.5  4971.1  4971.1  4976.5  4976.5  5000.9  5034.1  5034.1  5035.3
  5035.3  5079.9  5148.8  5185.8    5210    5364    5414  5979.4  6429.4  7226.2
  8661.2  8721.2  8871.2  9166.2  9336.2  9501.2  9816.2 10006.2 10131.2 10426.2
 10621.2 10846.2 11031.2 11136.2 11371.2 11436.3
  140.75  140.07  139.22  139.27  139.66   139.6  138.99  137.72  137.53  137.55
   137.7  138.14  138.43  138.64  138.82  138.95  138.81  138.35  138.18   137.9
  137.85  138.01  138.03  139.96  139.94  139.94  139.88  139.93  138.11  138.11
  138.11   138.1  138.81  139.35  139.49  139.65  139.61  138.24  137.75  137.22
  138.47  138.94  142.52  144.05  138.61  138.11  138.19  138.47  138.82  141.12
  144.69  147.18  148.87  149.14  148.29  149.14
  107.57  107.57  107.57  107.57  107.57  107.57  107.57  107.57  107.57  107.57
  107.57  107.57  107.57  107.57  107.57  107.57  107.57  107.57  107.57  107.57
  107.57  107.57  107.57  107.57  107.57  135.88  135.88  135.88  135.88  135.88
  107.57  107.57  107.57  107.57  107.57  107.57  107.57  107.57  107.57  107.57
  107.57  107.57  107.57  107.57  107.57  107.57  107.57  107.57  107.57  107.57
  107.57  107.57  107.57  107.57  107.57  107.57
   911.7   936.7  1346.7  1691.7  2096.7  2171.7  2326.7  2465.1  2630.1  2750.1
  2835.1  3012.6    3084    3199  3370.4  3711.6  3921.6  4326.6  4812.1  4881.3
  4913.8  4947.5  4971.1  4971.1  4976.5  4976.5  5000.9  5034.1  5034.1  5035.3
  5035.3  5079.9  5148.8  5185.8    5210    5364    5414  5979.4  6429.4  7226.2
  8661.2  8721.2  8871.2  9166.2  9336.2  9501.2  9816.2 10006.2 10131.2 10426.2
 10621.2 10846.2 11031.2 11136.2 11371.2 11436.3
  140.75  140.07  139.22  139.27  139.66   139.6  138.99  137.72  137.53  137.55
   137.7  138.14  138.43  138.64  138.82  138.95  138.81  138.35  138.18   137.9
  137.85  138.01  138.03  139.96  139.94  139.94  139.88  139.93  138.11  138.11
  138.11   138.1  138.81  139.35  139.49  139.65  139.61  138.24  137.75  137.22
  138.47  138.94  142.52  144.05  138.61  138.11  138.19  138.47  138.82  141.12
  144.69  147.18  148.87  149.14  148.29  149.14
  107.57  107.57  107.57  107.57  107.57  107.57  107.57  107.57  107.57  107.57
  107.57  107.57  107.57  107.57  107.57  107.57  107.57  107.57  107.57  107.57
  107.57  107.57  107.57  107.57  107.57  135.88  135.88  135.88  135.88  135.88
  107.57  107.57  107.57  107.57  107.57  107.57  107.57  107.57  107.57  107.57
  107.57  107.57  107.57  107.57  107.57  107.57  107.57  107.57  107.57  107.57
  107.57  107.57  107.57  107.57  107.57  107.57
Pier Skew, UpSta & Num, DnSta & Num=  ,4986.8, 2 ,4986.8, 2 , 0 , 0 , 0 ,0,0
       1       1
  128.66  135.88
       1       1
   129.5  135.88
Pier Skew, UpSta & Num, DnSta & Num=  ,5002.8, 2 ,5002.8, 2 , 0 , 0 , 0 ,0,0
       1       1
  129.12  135.88
       1       1
  129.96  135.88
Pier Skew, UpSta & Num, DnSta & Num=  ,5017.9, 2 ,5017.9, 2 , 0 , 0 , 0 ,0,0
       1       1
  131.22  135.88
       1       1
  132.06  135.88
Abutment Skew #Up #Dn= , 2 , 2
  4976.5  4983.2
  135.88   129.1
  4976.5  4983.2
  135.88  129.94
Abutment Skew #Up #Dn= , 2 , 2
  5017.9  5035.3
  131.22  135.88
  5017.9  5035.3
  132.06  135.88
BR Coef= 1 , 1 , 0 ,0.9, 0 ,,,0.8,0,1.2,0,
WSPro=,,,, 1 ,,,, 0 ,,,, 0 ,,,,-1 ,-1 ,-1 , 0 , 0 , 0 , 0 , 0
BC Design=,, 0 ,, 0 ,,,,,,
BC HTab HWMax=149.38
BC Use User HTab Curves=0
BC User HTab FreeFlow(D)= 0

Type RM Length L Ch R = 1 ,23534   ,2496,2233,2216
BEGIN DESCRIPTION:
23534
END DESCRIPTION:
XS GIS Cut Line= 6
      1952156.42       317657.91      1951106.34       316019.65
      1950706.77       315748.01      1950000.66       314062.26
      1949004.96       312934.83      1946268.15       309065.55
#Sta/Elev= 30
   873.7   140.5  1582.5  138.95  2161.1  139.89    2411  138.43  3381.5  138.61
    3694  138.94    3881  138.55  4617.1  137.01  4884.8  138.86  4958.5  138.59
  4978.9  136.22  4988.1  128.92  4998.3  127.47  5009.1  127.79  5037.1  138.87
  5171.7  135.37  5321.7   138.4  5517.9  138.61  5719.3  139.22  6283.9  136.53
  6719.6  138.96  7298.5   137.2  7862.9  138.71  8485.3  137.13 10149.4  138.52
 10531.2  143.63 10975.3  148.91 11292.7  148.39 11366.7  148.04 11409.6  149.46
#Mann= 19 ,-1 , 0
   873.7     .05       0  1582.5      .1       0  2161.1     .09       0
    2411     .08       0  3381.5     .09       0    3694     .05       0
    3881     .08       0  4884.8     .05       0  4958.5     .08       0
  5037.1     .05       0  5517.9     .12       0  5719.3     .11       0
  6719.6     .12       0  7298.5     .13       0  7862.9     .12       0
 10149.4     .11       0 10531.2     .09       0 11292.7     .08       0
 11366.7     .05       0
#XS Ineff= 4 ,-1
    3206  4771.4  135.85 5232.13 5677.71  135.88 7725.1911099.24  146.69
     100    3206     145
Permanent Ineff=
       F       F       F       F
Bank Sta=4958.5,5037.1
XS Rating Curve= 0 ,0
Exp/Cntr=0.5,0.3

Type RM Length L Ch R = 1 ,21301   ,1727,1752,1753
BEGIN DESCRIPTION:
21301
END DESCRIPTION:
XS GIS Cut Line= 3
      1953368.14       317231.69      1951298.32       312394.36
      1948048.34       308394.39
#Sta/Elev= 30
  -357.4  139.35  -254.6  139.34   -30.2  138.39   858.6  138.05  1314.4  136.67
  1887.6  139.26  2329.7  137.07  2810.9  137.93  2934.7  137.65  3222.6  138.37
  3344.9  134.86  3852.6  138.61  4538.2  135.38  4642.6  131.78  4787.6  135.88
  4887.6  134.28  4919.2  134.45  4944.2  139.29  4978.9  135.85  4988.1  128.55
  4998.3   127.1  5049.2   137.4  5462.4  137.25    6422   137.1    6547  135.96
    6665  136.34  7867.6  138.45  9070.3  138.83  9116.4  139.49   10058  150.46
#Mann= 20 ,-1 , 0
  -357.4     .05       0  -254.6     .08       0   -30.2     .05       0
   858.6     .08       0  1314.4     .11       0  2329.7      .1       0
  2810.9     .05       0  2934.7     .12       0  3344.9     .11       0
  4538.2      .1       0  4887.6     .05       0  4978.9     .08       0
  5049.2     .05       0  5462.4     .11       0    6422     .05       0
    6547     .11       0    6665     .12       0  7867.6     .13       0
  9070.3     .09       0  9116.4     .08       0
#XS Ineff= 2 ,-1
 -338.77 1931.16  146.92 7208.65 9826.97  147.69
Permanent Ineff=
       F       F
Bank Sta=4978.9,5049.2
XS Rating Curve= 0 ,0
Exp/Cntr=0.3,0.1

Type RM Length L Ch R = 1 ,19549   ,2202,2256,2264
BEGIN DESCRIPTION:
19549
END DESCRIPTION:
XS GIS Cut Line= 3
      1954511.39       316885.71      1952923.32       311790.19
      1948985.81       306998.52
#Sta/Elev= 30
    -381  138.46  -359.5   138.5    -306  139.88  -259.3  136.66  -111.1  136.03
   522.9  137.85    1084  135.17  1844.2  136.16  2807.2  136.73  2914.3  136.82
  3659.9   137.6  3799.5   136.7  4777.2  135.82  4986.7  135.43  4988.1  127.55
  4998.3   126.1  5009.1  126.42  5031.3  136.16  5943.1  137.91  6586.3  135.52
  8759.2   140.1  9296.3     143  9396.3  146.16  9481.3  143.39  9567.4  144.52
 10229.4  148.28 10775.5  149.98 10842.5  150.01 10943.1  147.91 11158.2  147.07
#Mann= 20 ,-1 , 0
    -381     .09       0  -359.5     .05       0  -259.3     .07       0
  -111.1      .1       0   522.9     .11       0  1844.2     .12       0
  2807.2     .05       0  2914.3      .1       0  3659.9     .12       0
  3799.5      .1       0  4777.2     .08       0  4986.7     .08       0
  5031.3     .08       0  5943.1     .12       0  8759.2     .11       0
  9567.4      .1       0 10229.4     .09       0 10775.5     .08       0
 10842.5     .05       0 10943.1     .09       0
#XS Ineff= 2 ,-1
 -528.99  548.91  147.75 7992.3710432.57  147.12
Permanent Ineff=
       F       F
Bank Sta=4986.7,5031.3
XS Rating Curve= 0 ,0
Exp/Cntr=0.3,0.1

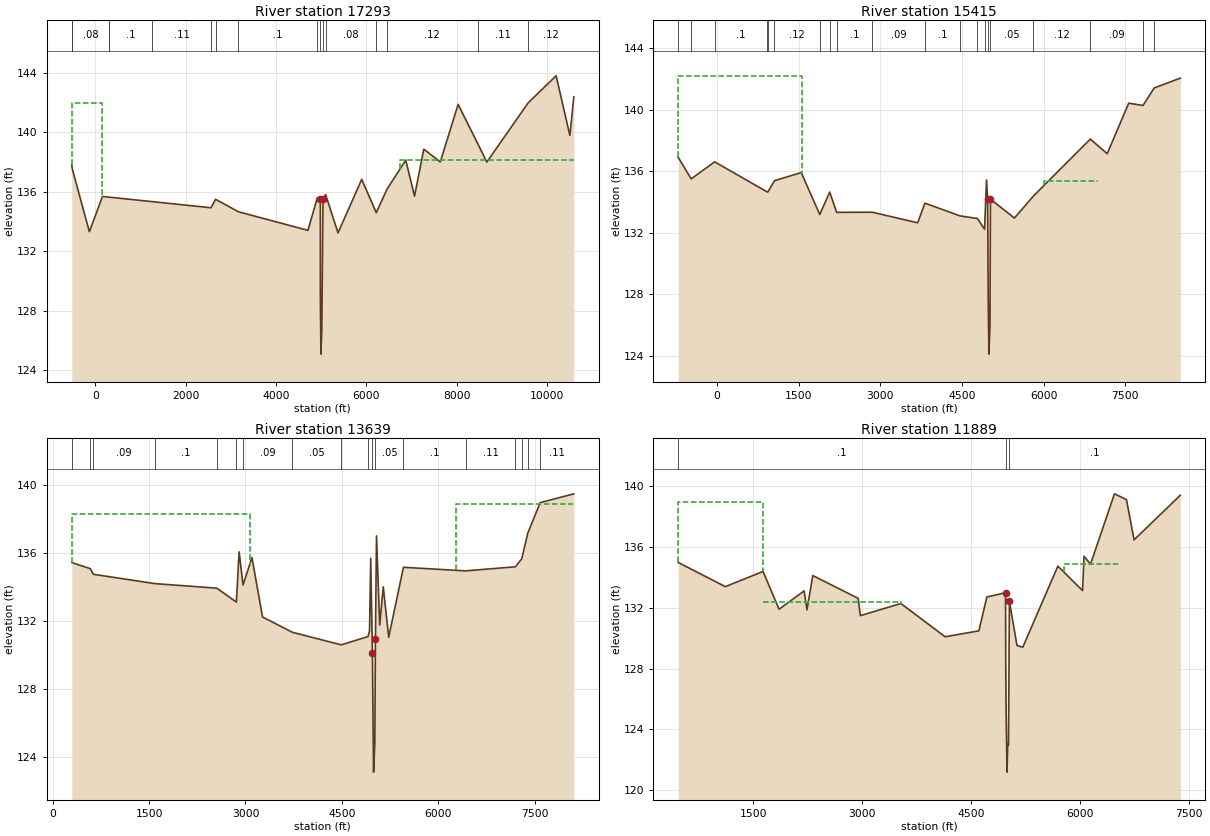
Type RM Length L Ch R = 1 ,17293   ,1960,1878,1898
BEGIN DESCRIPTION:
17293 - LiDAR artifacts removed from left overbank
END DESCRIPTION:
XS GIS Cut Line= 3
      1956297.76       316490.17      1955048.32       311102.69
      1951944.16       306456.87
#Sta/Elev= 30
  -523.8  137.81    -513  137.55  -133.8  133.33   156.2   135.7    2559  134.94
  2659.9  135.51  3167.3  134.67  4706.2  133.42  4913.4  135.61 4980.39   135.5
  4981.3  128.88  4993.5   125.1  5013.5  126.86 5038.75  135.51  5096.8  135.83
  5371.7  133.25  5896.7  136.85  6219.4  134.61  6457.3  136.19  6871.7  138.14
  7066.7  135.72  7271.7  138.88  7636.7  138.02  8031.7  141.89  8464.5  139.26
  8666.7  138.01    9587  142.01 10201.7  143.81 10506.7   139.8 10594.1   142.4
#Mann= 16 ,-1 , 0
  -523.8     .05       0    -513     .08       0   292.8     .11       0
   310.9      .1       0    1251     .11       0    2559     .05       0
  2659.9     .12       0  3167.3      .1       0  4913.4     .05       0
 4980.39    .045       0 5038.75     .05       0  5096.8     .08       0
  6219.4     .11       0  6457.3     .12       0  8464.5     .11       0
    9587     .12       0
#XS Ineff= 2 ,-1
  -523.8  143.12  141.97  6745.8 10594.1  138.16
Permanent Ineff=
       F       F
Bank Sta=4980.39,5038.75
XS Rating Curve= 0 ,0
Exp/Cntr=0.3,0.1

Type RM Length L Ch R = 1 ,15415   ,1844,1776,1810
BEGIN DESCRIPTION:
15415
END DESCRIPTION:
XS GIS Cut Line= 3
      1958373.24       316341.56      1956902.49       310811.03
      1955319.14       307686.01
#Sta/Elev= 30
  -714.4  136.91  -476.3  135.51     -45  136.62   920.8  134.66   933.9  134.66
  1053.7  135.39  1545.6  135.92  1886.6  133.19    2069  134.65  2196.5  133.33
  2852.5  133.34  3685.6  132.65  3818.3  133.93  4463.3   133.1  4784.1  132.93
  4914.6  132.23  4950.6  135.44 4971.44   134.2  4981.3  127.88  4993.5   124.1
  5013.5  125.86 5022.92  134.19  5463.4  132.96  5811.8  134.39  6858.1   138.1
  7168.4  137.15  7563.4  140.44  7826.5  140.29  8031.6  141.43  8511.6  142.07
#Mann= 20 ,-1 , 0
  -714.4     .05       0  -476.3     .08       0     -45      .1       0
   920.8     .08       0   933.9     .05       0  1053.7     .12       0
  1886.6     .11       0    2069     .05       0  2196.5      .1       0
  2852.5     .09       0  3818.3      .1       0  4463.3     .09       0
  4784.1     .11       0  4914.6     .05       0 4971.44     .08       0
 5022.92     .05       0  5811.8     .12       0  6858.1     .09       0
  7826.5     .05       0  8031.6      .1       0
#XS Ineff= 2 ,-1
  -714.4 1554.35  142.22 6006.21 6990.29  135.39
Permanent Ineff=
       F       F
Bank Sta=4971.44,5022.92
XS Rating Curve= 0 ,0
Exp/Cntr=0.3,0.1

Type RM Length L Ch R = 1 ,13639   ,2173,1750,1689
BEGIN DESCRIPTION:
13639
END DESCRIPTION:
XS GIS Cut Line= 4
      1959841.63       315088.23      1959571.24       313852.69
      1958671.24       310586.03      1957837.89       307535.98
#Sta/Elev= 30
     296  135.45   584.7  135.09   630.7  134.76  1586.5  134.21  2554.7  133.94
  2858.2  133.12  2900.8  136.08  2961.9  134.13  3100.8  135.74  3265.8  132.24
  3730.8  131.34    4491   130.6    4908  131.09  4930.8  131.43  4949.2   135.7
  4975.6  130.12  4993.5   123.1  5013.5  124.86  5022.7  130.95  5039.2  137.02
  5089.2  131.77  5144.2  134.02  5229.2  131.05  5458.8  135.17  6426.4  134.96
    7200   135.2    7300  135.67    7394  137.18  7587.2  138.98    8111   139.5
#Mann= 18 ,-1 , 0
     296     .05       0   584.7      .1       0   630.7     .09       0
  1586.5      .1       0  2554.7     .12       0  2858.2     .05       0
  2961.9     .09       0  3730.8     .05       0    4491     .11       0
    4908     .05       0  4975.6     .08       0  5022.7     .05       0
  5458.8      .1       0  6426.4     .11       0    7200     .05       0
    7300     .09       0    7394      .1       0  7587.2     .11       0
#XS Ineff= 2 ,-1
 6281.41  8100.5  138.89     296 3070.65  138.32
Permanent Ineff=
       T       F
Bank Sta=4975.6,5022.7
XS Rating Curve= 0 ,0
Exp/Cntr=0.5,0.3

Type RM Length L Ch R = 1 ,11889   ,116,79,116
BEGIN DESCRIPTION:
11889
END DESCRIPTION:
XS GIS Cut Line= 6
      1961513.76       313991.44      1961384.74       313814.64
      1960559.19       311599.79       1960497.6       310510.94
       1960068.3       309507.21      1959342.44       307486.66
#Sta/Elev= 30
   463.2  134.99  1112.1   133.4  1632.1   134.4  1852.1  131.91  2197.1  133.12
  2237.1  131.87  2317.1  134.13  2942.1  132.63  2972.1  131.49  3530.8  132.29
  4140.3   130.1  4605.3  130.49  4715.3  132.72  4972.7     133  4975.6  128.21
  4981.3  124.97  4993.5  121.19  5002.5  123.05  5013.5  122.95    5026  132.43
  5130.2  129.53  5210.2  129.41  5693.7  134.75  6033.7  133.14  6053.7   135.4
  6143.7  134.88  6473.7  139.51  6638.7  139.13  6743.7  136.48  7380.7  139.42
#Mann= 3 ,-1 , 0
   463.2      .1       0  4972.7     .08       0    5026      .1       0
#XS Ineff= 5 ,-1
   463.2    1632     139 5778.29 6555.43  134.87    1632    3539  132.37
    5041 5778.29   131.6    3539    4958   131.6
Permanent Ineff=
       F       F       F       F       F
Bank Sta=4972.7,5026
XS Rating Curve= 0 ,0
Exp/Cntr=0.5,0.3