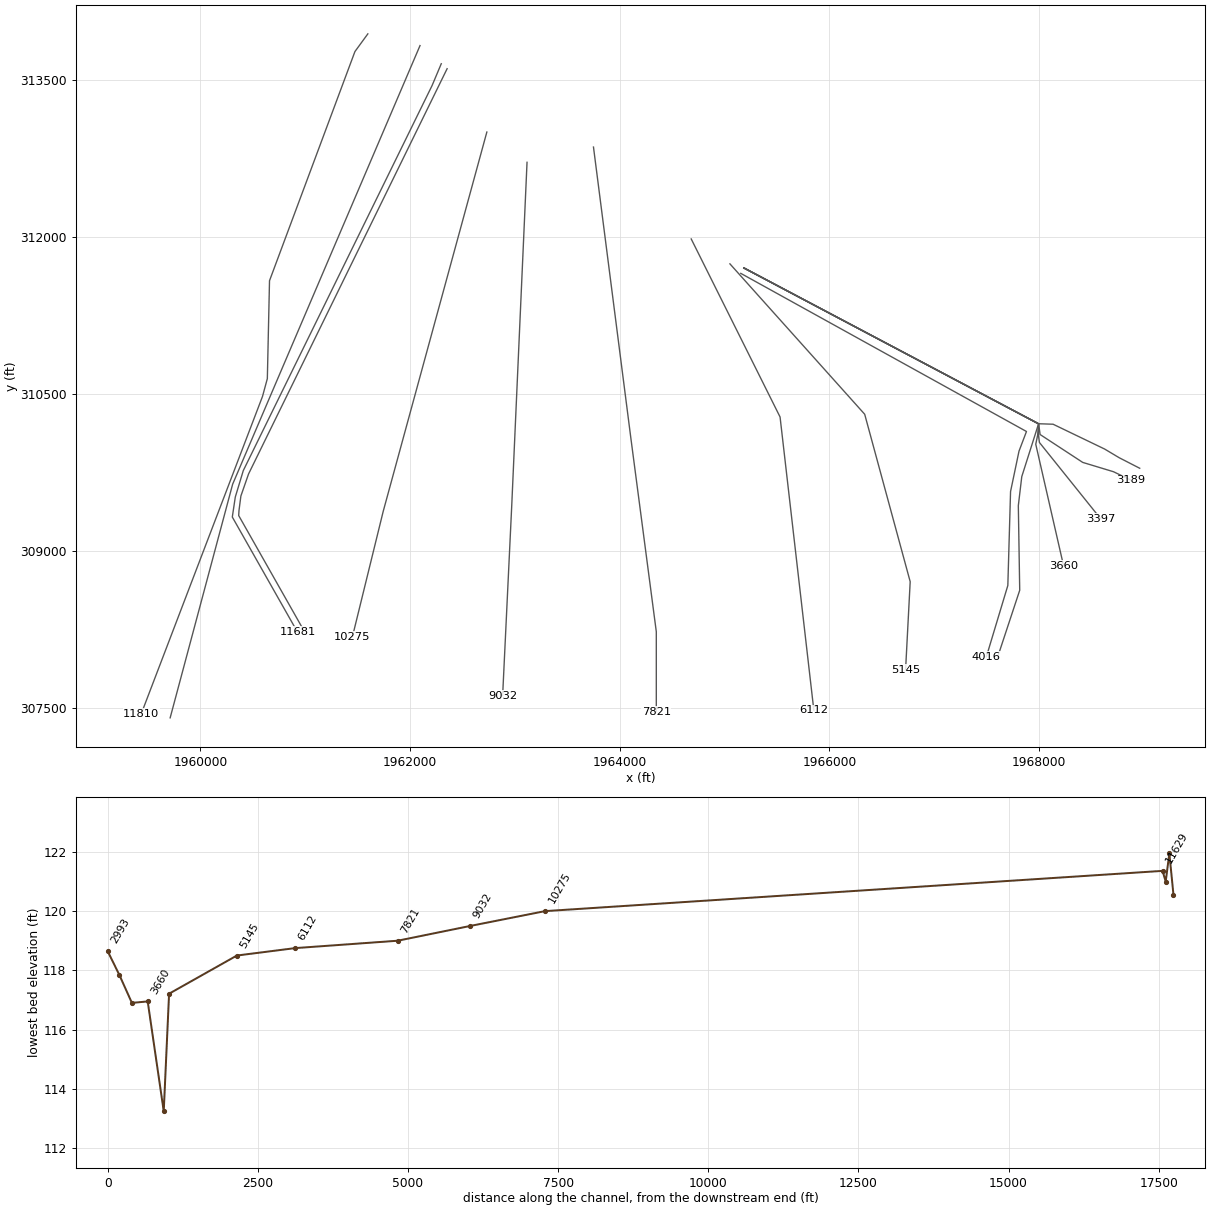
HEC-RAS study BackSwamp.prj: Back Swamp Detailed Study

--- BackSwamp.g01 (geometry) --- (continued)

Type RM Length L Ch R = 3 ,11861   ,,,
BEGIN DESCRIPTION:
Back Swamp Rd (SR 1164),  R_BAS_04
END DESCRIPTION:
Bridge Culvert--1,0,-1,-1, 0
Deck Dist Width WeirC Skew NumUp NumDn MinLoCord MaxHiCord MaxSubmerge Is_Ogee
15,26,3,0, 60, 60, 131.59, , 0.95, 0, 1,1,,
   468.2   528.2   558.2   613.2   668.2     697     867     957    1042    1177
    1457    1567    1697    2067    2332    2637    2792  3145.4  3265.4  3500.4
  4096.8  4287.4  4412.4  4517.4  4592.4  4662.4  4806.4  4820.6  4862.7  4899.7
  4937.3  4965.9  4965.9  4966.6  4966.6  4984.4  4989.4  5006.1  5024.7  5024.7
  5024.8  5024.8  5049.6  5079.6  5113.8  5142.3  5166.8  5192.3    5269    5389
  6479.9  6589.9  6649.9  6754.9  6904.9  7074.9  7199.9  7219.9  7334.9  7371.5
  133.76  133.96   134.2  134.76  134.84  134.83  134.29  134.14  134.07  133.98
  133.76  133.68   133.6  133.32  133.26  133.16  132.99  132.14  131.86  131.59
   131.6  131.67  131.72  131.84  132.03  132.31  133.35  133.43  133.67   133.8
     134  134.26  136.86  136.86  136.86  136.86  136.85  136.83  136.83  134.35
  134.35  134.35  134.46  134.81  135.22  135.64  136.08  136.51  137.07  137.15
  138.06   138.1  138.04  138.14   138.2  138.42  138.71  138.75  139.17  139.36
  102.24  102.24  102.24  102.24  102.24  102.24  102.24  102.24  102.24  102.24
  102.24  102.24  102.24  102.24  102.24  102.24  102.24  102.24  102.24  102.24
  102.24  102.24  102.24  102.24  102.24  102.24  102.24  102.24  102.24  102.24
  102.24  102.24  102.24  102.24   132.6   132.6   132.6   132.6   132.6   132.6
   132.6  102.24  102.24  102.24  102.24  102.24  102.24  102.24  102.24  102.24
  102.24  102.24  102.24  102.24  102.24  102.24  102.24  102.24  102.24  102.24
   468.2   528.2   558.2   613.2   668.2     697     867     957    1042    1177
    1457    1567    1697    2067    2332    2637    2792  3145.4  3265.4  3500.4
  4096.8  4287.4  4412.4  4517.4  4592.4  4662.4  4806.4  4820.6  4862.7  4899.7
  4937.3  4965.9  4965.9  4966.6  4966.6  4984.4  4989.4  5006.1  5024.7  5024.7
  5024.8  5024.8  5049.6  5079.6  5113.8  5142.3  5166.8  5192.3    5269    5389
  6479.9  6589.9  6649.9  6754.9  6904.9  7074.9  7199.9  7219.9  7334.9  7371.5
  133.76  133.96   134.2  134.76  134.84  134.83  134.29  134.14  134.07  133.98
  133.76  133.68   133.6  133.32  133.26  133.16  132.99  132.14  131.86  131.59
   131.6  131.67  131.72  131.84  132.03  132.31  133.35  133.43  133.67   133.8
     134  134.26  136.86  136.86  136.86  136.86  136.85  136.83  136.83  134.35
  134.35  134.35  134.46  134.81  135.22  135.64  136.08  136.51  137.07  137.15
  138.06   138.1  138.04  138.14   138.2  138.42  138.71  138.75  139.17  139.36
  102.24  102.24  102.24  102.24  102.24  102.24  102.24  102.24  102.24  102.24
  102.24  102.24  102.24  102.24  102.24  102.24  102.24  102.24  102.24  102.24
  102.24  102.24  102.24  102.24  102.24  102.24  102.24  102.24  102.24  102.24
  102.24  102.24  102.24  102.24   132.6   132.6   132.6   132.6   132.6   132.6
   132.6  102.24  102.24  102.24  102.24  102.24  102.24  102.24  102.24  102.24
  102.24  102.24  102.24  102.24  102.24  102.24  102.24  102.24  102.24  102.24
Pier Skew, UpSta & Num, DnSta & Num=  ,4985.9, 2 ,4985.9, 2 , 0 , 0 , 0 ,0,0
       1       1
  124.43   132.6
       1       1
  122.75   132.6
Pier Skew, UpSta & Num, DnSta & Num=  ,5005.4, 2 ,5005.4, 2 , 0 , 0 , 0 ,0,0
       1       1
  123.35   132.6
       1       1
  121.67   132.6
Abutment Skew #Up #Dn= , 2 , 2
  4966.6  4970.8
   132.6  128.24
  4966.6  4970.8
   132.6  126.56
Abutment Skew #Up #Dn= , 2 , 2
  5022.8  5024.8
  124.85   132.6
  5022.8  5024.8
  123.17   132.6
BR Coef= 1 , 1 , 0 ,0.9, 0 ,,,0.8,0,1.2,0,
WSPro=,,,, 1 ,,,, 0 ,,,, 0 ,,,,-1 ,-1 ,-1 , 0 , 0 , 0 , 0 , 0
BC Design=,, 0 ,, 0 ,,,,,,
BC HTab HWMax=139.51
BC Use User HTab Curves=0
BC User HTab FreeFlow(D)= 0

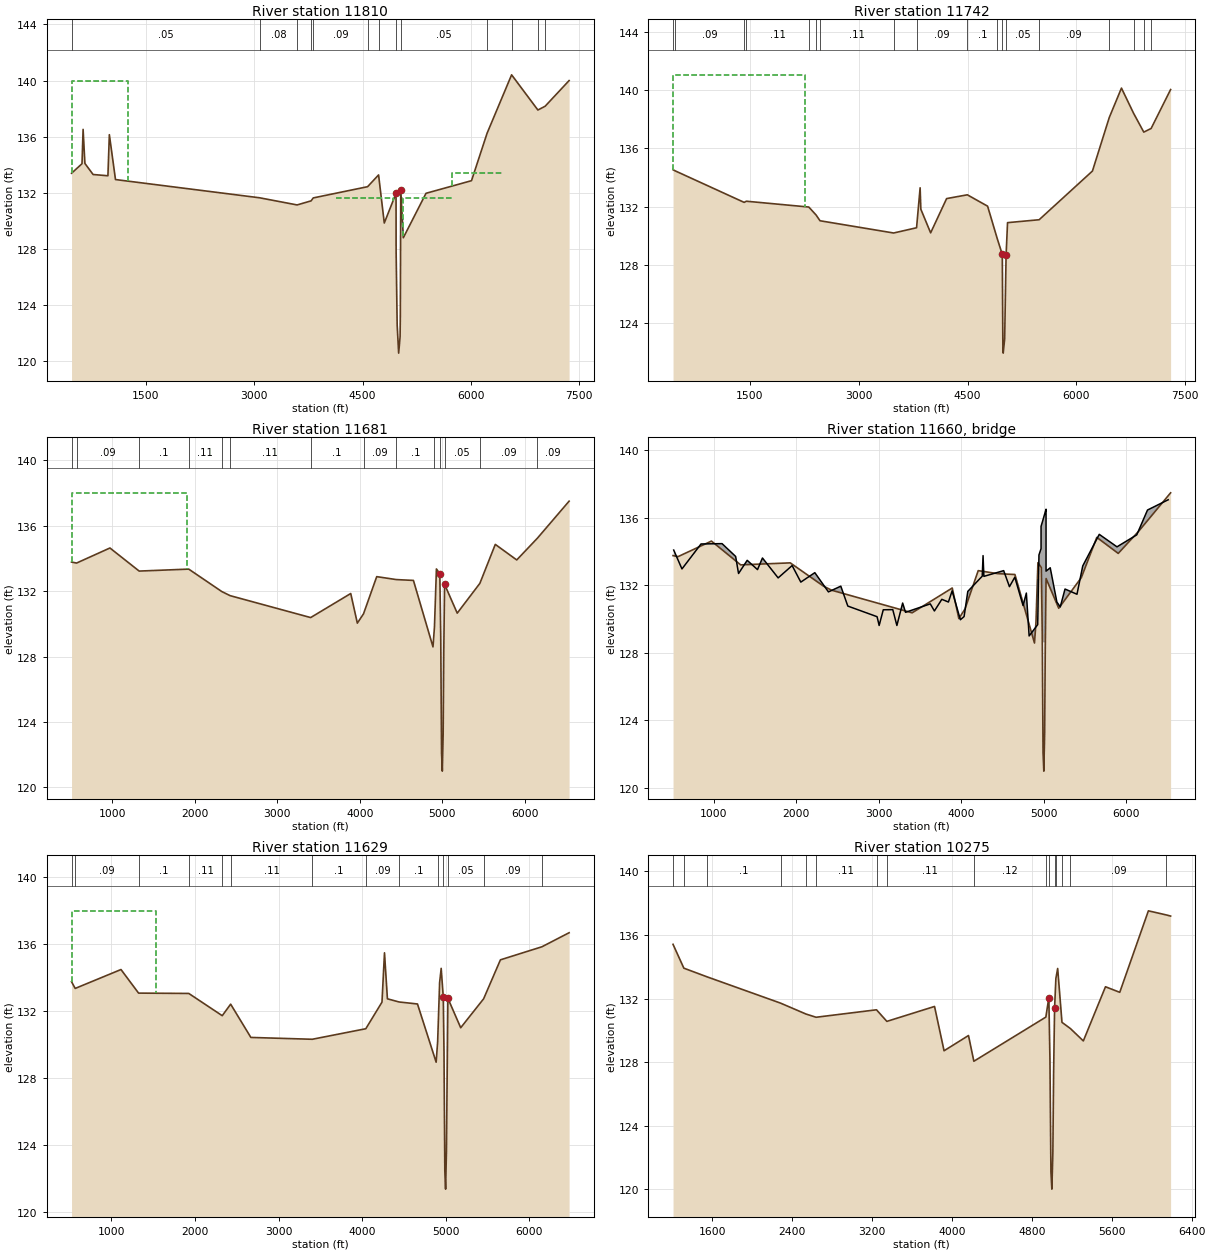
Type RM Length L Ch R = 1 ,11810   ,103,68,87
BEGIN DESCRIPTION:
11810-LiDAR artifacts removed from left overbank
END DESCRIPTION:
XS GIS Cut Line= 6
      1961596.64       313935.38      1961473.64       313766.81
      1960658.79       311580.69      1960638.04       310646.85
      1960592.15       310477.51      1959436.32       307452.22
#Sta/Elev= 30
   469.3  133.39   614.3  134.07   629.3  136.52   654.3  134.09     768   133.3
     973  133.21     993  136.14    1078  132.94  3073.1  131.64    3593  131.13
  3787.2  131.42  3816.8  131.63  4569.3  132.43  4721.6  133.27  4800.6  129.84
  4963.5  131.96  4964.5  127.82    4979  122.57  4999.6  120.56  5019.4  121.72
  5022.8  123.17  5028.6  132.23  5064.3  128.79  5378.6  131.96  6008.6  132.86
  6224.1  136.24    6564  140.41  6928.1   137.9  7028.4  138.17  7360.2     140
#Mann= 13 ,-1 , 0
   469.3     .05       0  3073.1     .08       0    3593     .09       0
  3787.2     .05       0  3816.8     .09       0  4569.3      .1       0
  4721.6     .05       0  4963.5     .08       0  5028.6     .05       0
  6224.1     .08       0    6564     .08       0  6928.1     .05       0
  7028.4     .08       0
#XS Ineff= 4 ,-1
   469.3    1253     140 5732.57 6436.57  133.43  5062.8 5732.57   131.6
 4132.57    4923   131.6
Permanent Ineff=
       F       F       F       F
Bank Sta=4963.5,5028.6
XS Rating Curve= 0 ,0
Exp/Cntr=0.5,0.3

Type RM Length L Ch R = 1 ,11742   ,63,61,72
BEGIN DESCRIPTION:
11742
END DESCRIPTION:
XS GIS Cut Line= 3
      1962094.45       313823.69      1960307.15        309639.8
      1959710.95       307410.92
#Sta/Elev= 30
   442.1  134.53   468.4  134.46  1422.1  132.29  1452.5  132.37  2313.2  131.97
  2414.1  131.42  2467.5  131.03  3482.5  130.19  3798.1  130.55  3847.1  133.29
  3857.1  131.82  3992.1   130.2  4212.1  132.55  4497.5  132.81  4777.1  132.03
  4909.1  129.82  4979.5  128.72  4987.8  122.27  4992.2  121.95  5012.1  122.92
  5031.8  128.66  5051.8   130.9  5487.4   131.1  6221.8  134.44  6453.6  138.11
  6621.8  140.13  6789.1   138.4  6929.4  137.11  7030.5  137.36    7299  140.03
#Mann= 18 ,-1 , 0
   442.1     .05       0   468.4     .09       0  1422.1      .1       0
  1452.5     .11       0  2313.2     .05       0  2414.1     .08       0
  2467.5     .11       0  3482.5     .12       0  3798.1     .09       0
  4497.5      .1       0  4909.1     .05       0  4979.5     .08       0
  5031.8     .05       0  5487.4     .09       0  6453.6     .09       0
  6789.1     .08       0  6929.4     .05       0  7030.5     .08       0
#XS Ineff= 1 ,-1
   442.1 2261.24  141.04
Permanent Ineff=
       F
Bank Sta=4979.5,5031.8
XS Rating Curve= 0 ,0
Exp/Cntr=0.5,0.3

Type RM Length L Ch R = 1 ,11681   ,97,52,50
BEGIN DESCRIPTION:
11681-LiDAR artifacts removed from left overbank
END DESCRIPTION:
XS GIS Cut Line= 6
      1962297.21       313650.63      1962209.68       313442.72
      1960408.64        309769.5      1960332.36       309517.33
      1960303.86        309326.4      1960925.02       308230.16
#Sta/Elev= 30
   504.6  133.77   565.8  133.71   970.2  134.63  1324.7  133.22  1925.7  133.34
  2326.4  131.97    2427  131.72    3404  130.38  3890.2  131.85  3970.2  130.04
  4045.1  130.61  4205.2  132.88  4443.6   132.7  4650.2  132.65  4887.5  128.59
  4905.5  129.82  4929.1  133.35  4970.4  133.06  4981.5   129.2  4991.4   122.1
  5000.6     121  5010.7  123.25  5018.2  128.28  5028.1  132.41  5181.5  130.65
    5456  132.47    5643  134.85    5903   133.9  6153.8  135.23    6538  137.49
#Mann= 14 ,-1 , 0
   504.6     .05       0   565.8     .09       0  1324.7      .1       0
  1925.7     .11       0  2326.4     .05       0    2427     .11       0
    3404      .1       0  4045.1     .09       0  4443.6      .1       0
  4905.5     .05       0  4970.4     .08       0  5028.1     .05       0
    5456     .09       0  6153.8     .09       0
#XS Ineff= 1 ,-1
   504.6    1910     138
Permanent Ineff=
       F
Bank Sta=4970.4,5028.1
XS Rating Curve= 0 ,0
Exp/Cntr=0.5,0.3

Type RM Length L Ch R = 3 ,11660   ,,,
BEGIN DESCRIPTION:
Pedestrian Bridge,  R_BAS_03A
END DESCRIPTION:
Bridge Culvert--1,0,-1,-1, 0
Deck Dist Width WeirC Skew NumUp NumDn MinLoCord MaxHiCord MaxSubmerge Is_Ogee
9,24,3,0, 60, 60, 129.27, , 0.95, 0, 1,1,,
   512.7   612.7   843.8  1098.8  1263.8  1298.8  1403.8  1528.8  1588.8  1778.8
  1948.8  2053.8  2223.8  2388.8  2538.8  2623.8  2978.8  3003.8  3053.8  3168.8
  3218.8  3288.8  3323.8  3623.8  3673.8  3763.8  3843.8  3888.8  3988.8  4033.8
  4078.8  4253.8  4263.8  4273.8  4513.8  4583.8  4648.8  4748.8  4788.8  4822.5
  4926.3  4941.6  4966.9  4966.9  4985.7  5016.9  5016.9  5027.6  5027.6  5078.4
  5158.9  5199.9  5257.7  5402.7  5472.7  5672.7  5887.7  6127.7  6257.7  6508.8
   134.1  132.98  134.46  134.48  133.72  132.71  133.49  132.94  133.63  132.45
  133.18   132.2  132.76  131.62  131.96  130.78  130.15  129.63  130.56  130.57
  129.63  130.96  130.41  130.91  130.49  131.18  131.02  131.68  129.97  130.16
  131.65  132.55  133.77  132.54  132.88  131.93  132.49  130.81  131.55  129.01
  129.68  133.81  134.18   135.5  135.81  136.34  136.34  136.52  132.85  133.05
  131.02  130.73  131.79  131.48  133.16  135.03  134.29     135  136.47  137.08
     101     101     101     101     101     101     101     101     101     101
     101     101     101     101     101     101     101     101     101     101
     101     101     101     101     101     101     101     101     101     101
     101     101     101     101     101     101     101     101     101     101
     101     101     101     101  128.63  128.63     101     101     101     101
     101     101     101     101     101     101     101     101     101     101
   512.7   612.7   843.8  1098.8  1263.8  1298.8  1403.8  1528.8  1588.8  1778.8
  1948.8  2053.8  2223.8  2388.8  2538.8  2623.8  2978.8  3003.8  3053.8  3168.8
  3218.8  3288.8  3323.8  3623.8  3673.8  3763.8  3843.8  3888.8  3988.8  4033.8
  4078.8  4253.8  4263.8  4273.8  4513.8  4583.8  4648.8  4748.8  4788.8  4822.5
  4926.3  4941.6  4966.9  4966.9  4985.7  5016.9  5016.9  5027.6  5027.6  5078.4
  5158.9  5199.9  5257.7  5402.7  5472.7  5672.7  5887.7  6127.7  6257.7  6508.8
   134.1  132.98  134.46  134.48  133.72  132.71  133.49  132.94  133.63  132.45
  133.18   132.2  132.76  131.62  131.96  130.78  130.15  129.63  130.56  130.57
  129.63  130.96  130.41  130.91  130.49  131.18  131.02  131.68  129.97  130.16
  131.65  132.55  133.77  132.54  132.88  131.93  132.49  130.81  131.55  129.01
  129.68  133.81  134.18   135.5  135.81  136.34  136.34  136.52  132.85  133.05
  131.02  130.73  131.79  131.48  133.16  135.03  134.29     135  136.47  137.08
     101     101     101     101     101     101     101     101     101     101
     101     101     101     101     101     101     101     101     101     101
     101     101     101     101     101     101     101     101     101     101
     101     101     101     101     101     101     101     101     101     101
     101     101     101     101  128.63  128.63     101     101     101     101
     101     101     101     101     101     101     101     101     101     101
Abutment Skew #Up #Dn= , 2 , 2
  4984.3  4985.9
  128.63  125.52
  4984.3  4985.9
  128.63  125.88
Abutment Skew #Up #Dn= , 2 , 2
  5014.6  5016.9
  126.26  128.63
  5014.6  5016.9
  126.62  128.63
BR Coef= 1 , 1 , 0 ,1.25, 0 ,,,0.8,0,1.2,0,
WSPro=,,,, 1 ,,,, 0 ,,,, 0 ,,,,-1 ,-1 ,-1 , 0 , 0 , 0 , 0 , 0
BC Design=,, 0 ,, 0 ,,,,,,
BC HTab HWMax=137.57
BC Use User HTab Curves=0
BC User HTab FreeFlow(D)= 0

Type RM Length L Ch R = 1 ,11629   ,11312,10282,10424
BEGIN DESCRIPTION:
11629
END DESCRIPTION:
XS GIS Cut Line= 6
      1962352.91         313603.       1960458.8       309737.23
      1960385.72       309527.07      1960367.64       309388.43
       1960364.8       309340.55      1960977.21       308259.75
#Sta/Elev= 30
     522  133.76   565.8  133.36    1114  134.49  1324.7  133.08  1925.7  133.06
  2326.4  131.73    2427  132.42    2669  130.43    3404  130.32  4045.1  130.95
    4239  132.54    4269  135.49    4304  132.74  4443.6  132.55    4664  132.43
  4887.5  128.95  4905.5  130.18  4929.1  133.71  4947.8  134.56 4973.06  132.82
  4981.5  129.56  4991.4  122.46  5000.6  121.36  5010.7  123.61  5028.1  132.77
  5181.5  131.01    5456  132.74  5657.2  135.07  6153.8  135.85  6479.4  136.69
#Mann= 14 ,-1 , 0
     522     .05       0   565.8     .09       0  1324.7      .1       0
  1925.7     .11       0  2326.4     .05       0    2427     .11       0
    3404      .1       0  4045.1     .09       0  4443.6      .1       0
  4905.5     .05       0 4973.06     .08       0  5028.1     .05       0
    5456     .09       0  6153.8     .09       0
#XS Ineff= 3 ,-1
     522    1539     138 4272.18  4904.3  128.63 5096.63    5650  128.63
Permanent Ineff=
       F       F       F
Bank Sta=4973.06,5028.1
XS Rating Curve= 0 ,0
Exp/Cntr=0.5,0.3

Type RM Length L Ch R = 1 ,10275   ,1202,1243,1280
BEGIN DESCRIPTION:
10275
END DESCRIPTION:
XS GIS Cut Line= 3
      1962731.99       312998.94      1961743.23       309380.26
      1961450.27       308186.72
#Sta/Elev= 30
    1209  135.41  1317.3  133.91  1547.2  133.37  2284.9  131.71  2540.7  131.02
  2640.8  130.82  3245.5  131.29  3349.1  130.56  3826.4   131.5  3921.8  128.71
  4166.3  129.67    4220  128.05  4940.7  130.83  4970.4  132.06  4981.5   128.2
  4991.4   121.1  5000.6     120  5010.7  122.25  5018.2  127.28  5028.1  131.41
    5041  133.26    5059  133.89    5102   130.5  5186.1  130.11  5315.8  129.33
  5537.5  132.74  5680.3  132.39    5967  137.52  6147.2  137.26  6189.3  137.19
#Mann= 16 ,-1 , 0
    1209     .08       0  1317.3     .08       0  1547.2      .1       0
  2284.9     .08       0  2540.7     .05       0  2640.8     .11       0
  3245.5     .05       0  3349.1     .11       0    4220     .12       0
  4940.7     .05       0  4970.4    .045       0  5028.1     .05       0
    5041     .11       0    5102     .11       0  5186.1     .09       0
  6147.2     .09       0
Bank Sta=4970.4,5028.1
XS Rating Curve= 0 ,0
Exp/Cntr=0.3,0.1

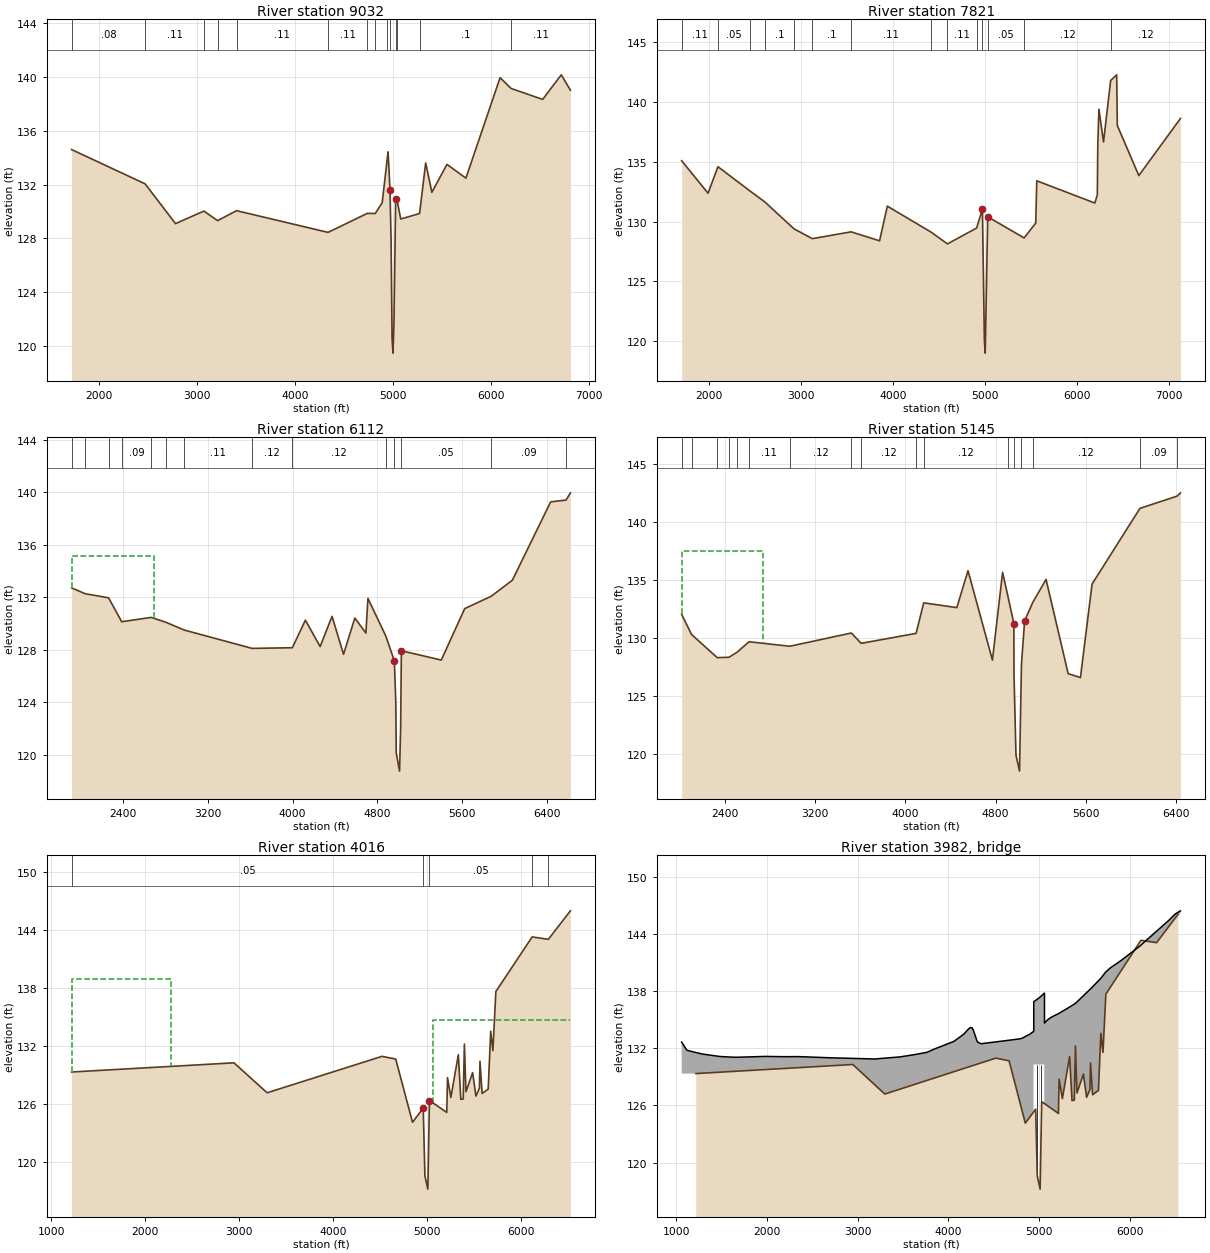
Type RM Length L Ch R = 1 ,9032    ,1147,1211,1251
BEGIN DESCRIPTION:
9032
END DESCRIPTION:
XS GIS Cut Line= 3
      1963115.34       312710.43      1962969.36       309434.52
      1962882.55       307622.45
#Sta/Elev= 30
    1719  134.59    2469  132.05  2780.3   129.1    3070  130.03    3210  129.32
  3403.3  130.06  4337.7  128.45  4738.6  129.86  4819.5  129.85  4890.4  130.65
  4940.7  133.82  4950.6  134.42  4970.4  131.56  4981.5   127.7  4991.4   120.6
  5000.6   119.5  5010.7  121.75  5028.1  130.91    5042  130.84  5079.8  129.44
    5272  129.85  5334.5   133.6  5397.7  131.42  5551.8  133.49  5745.2  132.47
  6094.3  139.92  6206.5  139.12    6529  138.31  6718.9  140.13  6812.3  138.99
#Mann= 14 ,-1 , 0
    1719     .08       0    2469     .11       0    3070     .05       0
    3210     .11       0  3403.3     .11       0  4337.7     .11       0
  4738.6     .05       0  4819.5     .11       0  4940.7     .05       0
  4970.4    .045       0  5028.1     .05       0    5042     .11       0
    5272      .1       0  6206.5     .11       0
Bank Sta=4970.4,5028.1
XS Rating Curve= 0 ,0
Exp/Cntr=0.3,0.1

Type RM Length L Ch R = 1 ,7821    ,1440,1709,1671
BEGIN DESCRIPTION:
7821
END DESCRIPTION:
XS GIS Cut Line= 4
      1963749.15       312855.73      1964105.43       310081.22
      1964348.48       308232.26      1964348.48       307468.32
#Sta/Elev= 30
  1698.6   135.1  1985.6  132.38    2093   134.6  2445.3  132.55  2600.6  131.67
  2920.8   129.4    3120  128.58  3541.6  129.15  3851.4   128.4  3935.8   131.3
    4411  129.13  4590.2  128.14  4907.2  129.47  4970.4  131.06  4991.4   120.1
  5000.6     119  5028.1  130.41    5424  128.64    5550  129.88  5561.6  133.42
  6193.6  131.56  6220.1  132.25  6225.3  136.44  6237.5  139.42  6287.6  136.67
  6365.4  141.82  6430.7  142.29  6437.8  138.05  6671.6  133.86  7124.7  138.64
#Mann= 14 ,-1 , 0
  1698.6     .11       0    2093     .05       0  2445.3     .08       0
  2600.6      .1       0  2920.8     .05       0    3120      .1       0
  3541.6     .11       0    4411     .05       0  4590.2     .11       0
  4907.2     .05       0  4970.4    .045       0  5028.1     .05       0
    5424     .12       0  6365.4     .12       0
Bank Sta=4970.4,5028.1
XS Rating Curve= 0 ,0
Exp/Cntr=0.3,0.1

Type RM Length L Ch R = 1 ,6112    ,874,967,999
BEGIN DESCRIPTION:
6112
END DESCRIPTION:
XS GIS Cut Line= 3
      1964681.49       311979.21      1965529.04       310280.87
      1965851.16       307483.93
#Sta/Elev= 30
  1912.4  132.71  2038.4  132.27    2262  131.95  2385.9  130.13  2664.8  130.46
  2800.1   130.1  2975.8   129.5  3617.8   128.1  3998.2  128.15  4121.8  130.25
  4260.7  128.24  4373.5  130.54  4482.1  127.65  4588.8  130.41  4693.4  129.27
  4712.7  131.91  4881.6  129.04  4962.5  127.14  4975.9  123.99  4980.1  120.13
  5011.5  118.75  5021.6     122  5028.6  127.92  5405.8  127.21  5627.2  131.13
  5877.3  132.07  6077.3  133.29  6439.2  139.26  6584.7   139.4  6625.9  139.95
#Mann= 14 ,-1 , 0
  1912.4     .05       0  2038.4      .1       0    2262     .05       0
  2385.9     .09       0  2664.8     .05       0  2800.1     .09       0
  2975.8     .11       0  3617.8     .12       0  3998.2     .12       0
  4881.6     .05       0  4962.5    .045       0  5028.6     .05       0
  5877.3     .09       0  6584.7     .05       0
#XS Ineff= 2 , 0
          2693.3  135.15
Permanent Ineff=
       F       F
Bank Sta=4962.5,5028.6
XS Rating Curve= 0 ,0
Exp/Cntr=0.3,0.1

Type RM Length L Ch R = 1 ,5145    ,1404,1129,1080
BEGIN DESCRIPTION:
5145
END DESCRIPTION:
XS GIS Cut Line= 4
      1965050.72       311741.48      1966336.33       310306.91
      1966770.36       308709.69      1966726.32       307868.63
#Sta/Elev= 30
  2015.3     132  2103.5  130.27  2330.5  128.28  2434.6  128.31  2506.1  128.74
  2612.6  129.65  2973.7  129.26  3520.3   130.4  3607.4  129.51  4094.3  130.37
  4161.9     133  4455.6  132.59  4554.7  135.77  4771.3  128.07  4861.4  135.63
    4910  133.51 4961.37  131.21  4962.5  126.89  4980.1  119.88  5011.5   118.5
  5028.6  127.67  5056.8  131.44  5129.1  133.04  5246.8  135.02  5442.9   126.9
  5551.8  126.56  5655.1  134.62  6079.5  141.14  6407.3  142.19    6439  142.48
#Mann= 17 ,-1 , 0
  2015.3     .05       0  2103.5     .09       0  2330.5     .05       0
  2434.6     .09       0  2506.1     .05       0  2612.6     .11       0
  2973.7     .12       0  3520.3     .05       0  3607.4     .12       0
  4094.3     .11       0  4161.9     .12       0    4910     .05       0
  4962.5    .045       0  5028.6     .05       0  5129.1     .12       0
  6079.5     .09       0  6407.3     .05       0
#XS Ineff= 2 , 0
         2734.54  137.47
Permanent Ineff=
       F       F
Bank Sta=4961.37,5056.8
XS Rating Curve= 0 ,0
Exp/Cntr=0.5,0.3

Type RM Length L Ch R = 1 ,4016    ,84,89,78
BEGIN DESCRIPTION:
4016
END DESCRIPTION:
XS GIS Cut Line= 6
       1965154.5       311650.74      1967879.58       310142.37
      1967808.33        309954.8      1967727.74       309569.53
      1967701.78       308673.38      1967497.63       307995.55
#Sta/Elev= 30
  1216.3  129.33  2946.4  130.28  3299.1  127.18  4523.2  130.95  4669.2  130.67
  4848.3  124.13  4962.5   125.6  4980.1  118.59  5011.5  117.21  5028.6  126.38
    5213  125.15    5221  128.74  5256.8   126.7  5336.4  131.12  5362.9   126.5
  5388.4  126.54  5400.8  132.22  5417.6  127.29  5488.7  129.27  5523.9  126.84
  5560.8  127.65  5566.8  130.45  5589.7  127.11  5654.5  127.56  5681.2  133.55
  5704.3  131.54  5736.3  137.66  6122.9  143.31  6295.3  143.06  6530.3  146.01
#Mann= 5 ,-1 , 0
  1216.3     .05       0  4962.5    .045       0  5028.6     .05       0
  6122.9      .1       0  6295.3     .05       0
#XS Ineff= 2 , 0
       0 2275.77  138.99  5067.9       0  134.73
Permanent Ineff=
       F       F
Bank Sta=4962.5,5028.6
XS Rating Curve= 0 ,0
Exp/Cntr=0.5,0.3

Type RM Length L Ch R = 3 ,3982    ,,,
BEGIN DESCRIPTION:
3982
Structure ID: R_BAS_03
Detailed Survey Structure
END DESCRIPTION:
Bridge Culvert--1,0,-1,-1, 0
Deck Dist Width WeirC Skew NumUp NumDn MinLoCord MaxHiCord MaxSubmerge Is_Ogee
10.5,47,3,0, 60, 60, , , 0.95, 0, 1,1,,
  1059.8  1117.3  1198.5  1293.7  1482.2  1600.1  1659.9  1982.2  2189.2  2347.1
  2684.2  3187.5  3467.9  3640.8  3764.7  3829.6  4061.4  4169.2  4217.1  4239.7
  4262.7  4275.7  4318.8  4341.4  4359.9  4771.9  4812.3  4851.6  4891.6  4925.7
  4931.7  4938.5  4938.5  4941.2  4941.2  4963.1  4978.5  4985.1  5008.1    5030
  5057.4  5057.4  5059.4  5059.4  5068.1  5093.5    5131  5166.7  5204.7  5314.1
  5400.3  5577.6  5683.2  5733.5  5783.6  5902.5  6108.9  6428.8  6501.1  6558.7
  132.63  131.78  131.58  131.37  131.12  131.06  131.04  131.13   131.1  131.11
  130.99  130.86  131.08  131.34  131.56  131.84  132.71  133.46  133.96  134.15
  134.12  133.87  132.67  132.54  132.46  132.95  133.03  133.24  133.42  133.66
  133.71  133.73  133.73  133.77  136.88  137.01  137.12  137.17  137.33  137.52
  137.75  137.75  137.77  134.63  134.73  134.96  135.22   135.4  135.57  136.18
  136.69  138.31  139.35  139.97   140.4  141.18  142.69  145.39  146.07   146.4
   97.21   97.21   97.21   97.21   97.21   97.21   97.21   97.21   97.21   97.21
   97.21   97.21   97.21   97.21   97.21   97.21   97.21   97.21   97.21   97.21
   97.21   97.21   97.21   97.21   97.21   97.21   97.21   97.21   97.21   97.21
   97.21   97.21  130.28  130.28  130.28  130.28  130.28  130.28  130.28  130.28
  130.28   97.21   97.21   97.21   97.21   97.21   97.21   97.21   97.21   97.21
   97.21   97.21   97.21   97.21   97.21   97.21   97.21   97.21   97.21   97.21
  1059.8  1117.3  1198.5  1293.7  1482.2  1600.1  1659.9  1982.2  2189.2  2347.1
  2684.2  3187.5  3467.9  3640.8  3764.7  3829.6  4061.4  4169.2  4217.1  4239.7
  4262.7  4275.7  4318.8  4341.4  4359.9  4771.9  4812.3  4851.6  4891.6  4925.7
  4931.7  4938.5  4938.5  4941.2  4941.2  4963.1  4978.5  4985.1  5008.1    5030
  5057.4  5057.4  5059.4  5059.4  5068.1  5093.5    5131  5166.7  5204.7  5314.1
  5400.3  5577.6  5683.2  5733.5  5783.6  5902.5  6108.9  6428.8  6501.1  6558.7
  132.63  131.78  131.58  131.37  131.12  131.06  131.04  131.13   131.1  131.11
  130.99  130.86  131.08  131.34  131.56  131.84  132.71  133.46  133.96  134.15
  134.12  133.87  132.67  132.54  132.46  132.95  133.03  133.24  133.42  133.66
  133.71  133.73  133.73  133.77  136.88  137.01  137.12  137.17  137.33  137.52
  137.75  137.75  137.77  134.63  134.73  134.96  135.22   135.4  135.57  136.18
  136.69  138.31  139.35  139.97   140.4  141.18  142.69  145.39  146.07   146.4
   97.21   97.21   97.21   97.21   97.21   97.21   97.21   97.21   97.21   97.21
   97.21   97.21   97.21   97.21   97.21   97.21   97.21   97.21   97.21   97.21
   97.21   97.21   97.21   97.21   97.21   97.21   97.21   97.21   97.21   97.21
   97.21   97.21  130.28  130.28  130.28  130.28  130.28  130.28  130.28  130.28
  130.28   97.21   97.21   97.21   97.21   97.21   97.21   97.21   97.21   97.21
   97.21   97.21   97.21   97.21   97.21   97.21   97.21   97.21   97.21   97.21
Pier Skew, UpSta & Num, DnSta & Num=  ,4980.1, 2 ,4980.1, 2 , 0 , 0 , 0 ,0,0
     2.5     2.5
  118.59  130.28
     2.5     2.5
  118.87  130.28
Pier Skew, UpSta & Num, DnSta & Num=  ,5021.6, 2 ,5021.6, 2 , 0 , 0 , 0 ,0,0
     2.5     2.5
  120.46  130.28
     2.5     2.5
  120.74  130.28
Abutment Skew #Up #Dn= , 2 , 2
  4938.5  4956.2
  130.28  125.89
  4938.5  4956.2
  130.28  126.17
Abutment Skew #Up #Dn= , 2 , 2
  5045.9  5057.4
     127  130.28
  5045.9  5057.4
  127.28  130.28
BR Coef= 1 , 1 , 0 ,1.25, 0 ,,,0.8,0,2,0,
WSPro=,,,, 1 ,,,, 0 ,,,, 0 ,,,,-1 ,-1 ,-1 , 0 , 0 , 0 , 0 , 0
BC Design=,, 0 ,, 0 ,,,,,,
BC HTab HWMax=146.01
BC Use User HTab Curves=0
BC User HTab FreeFlow(D)= 0

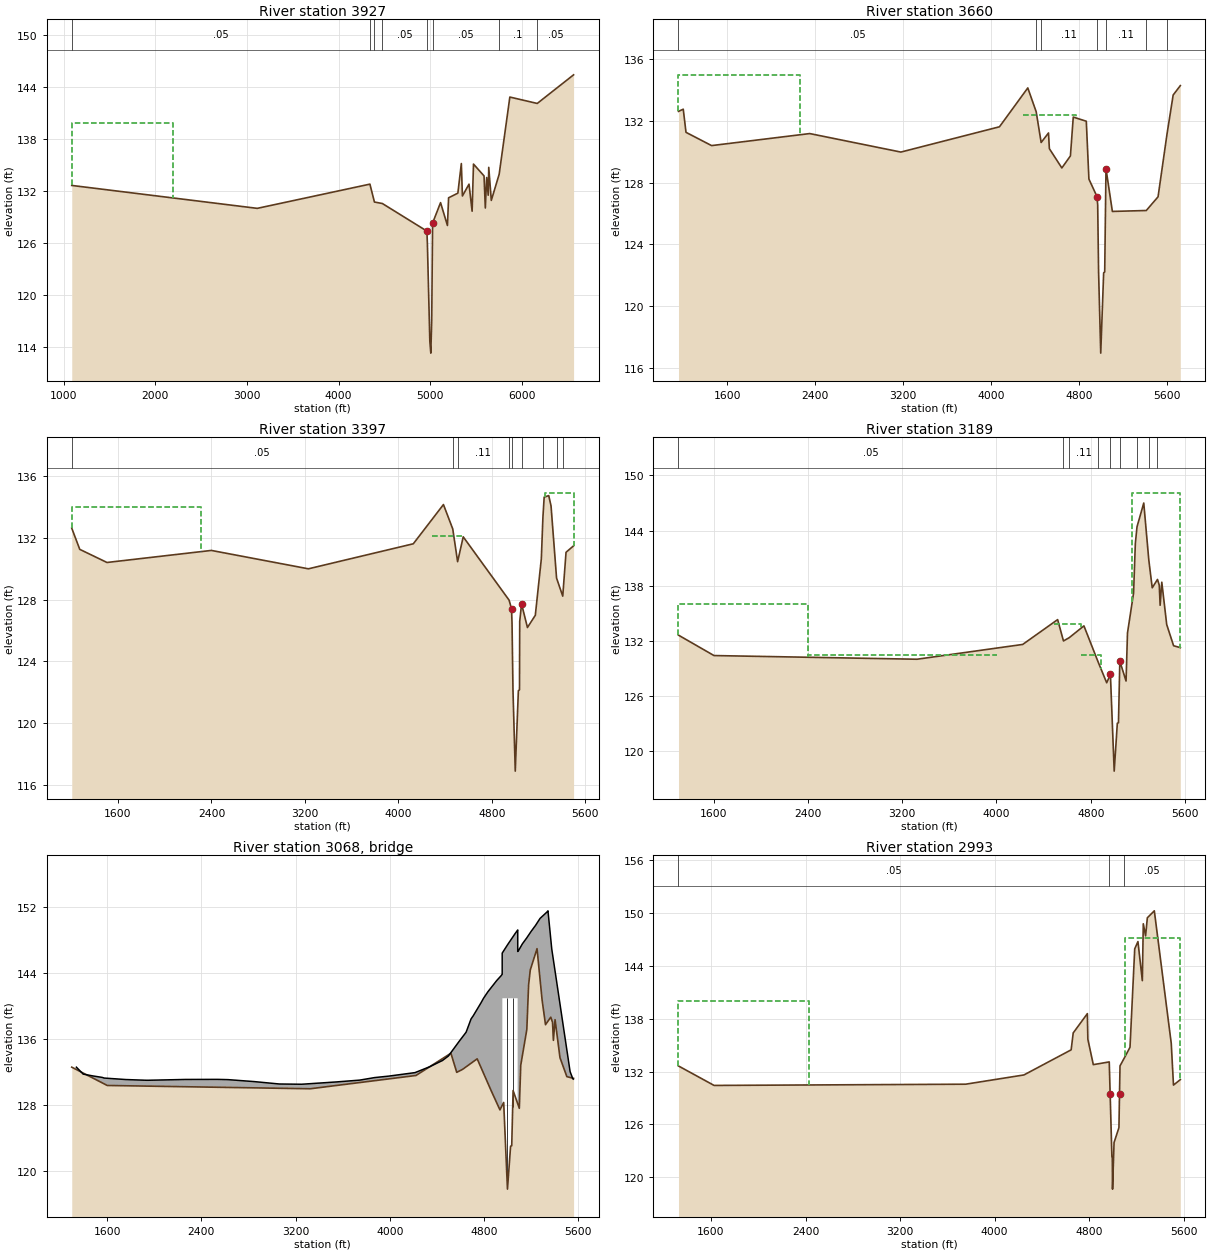
Type RM Length L Ch R = 1 ,3927    ,204,267,325
BEGIN DESCRIPTION:
3927
END DESCRIPTION:
XS GIS Cut Line= 6
      1965183.62       311701.86      1967994.86       310215.23
      1967834.78       309711.98      1967801.89       309434.88
      1967815.19       308628.02       1967601.7       307982.23
#Sta/Elev= 30
  1088.3  132.63    3113  129.98  4342.5  132.78  4391.8  130.71  4478.3  130.54
  4964.6  127.35  4970.1  125.79  4996.4  114.65  5007.2  113.24    5017  117.03
  5026.7  128.28  5113.5  130.64  5188.7     128  5201.2   131.2  5302.4  131.74
  5340.3  135.16  5352.1  131.41  5424.2  132.78    5458  129.65    5473   135.1
  5588.1  133.73  5602.2  130.02  5616.8  133.55  5633.7   131.5  5639.6  134.72
  5667.4   130.9  5753.2  133.92  5869.8  142.85  6168.7  142.11  6565.5  145.42
#Mann= 8 ,-1 , 0
  1088.3     .05       0  4342.5     .06       0  4391.8     .11       0
  4478.3     .05       0  4970.1    .045       0  5031.2     .05       0
  5753.2      .1       0  6168.7     .05       0
#XS Ineff= 2 , 0
         2190.72  139.83
Permanent Ineff=
       F       F
Bank Sta=4964.6,5026.7
XS Rating Curve= 0 ,0
Exp/Cntr=0.5,0.3

Type RM Length L Ch R = 1 ,3660    ,181,263,313
BEGIN DESCRIPTION:
3660
END DESCRIPTION:
XS GIS Cut Line= 6
      1965183.79       311702.16      1966187.29       311171.46
      1967995.13       310215.39      1967986.21       310107.63
      1967968.27       310020.45      1968234.11       308858.89
#Sta/Elev= 30
  1155.2  132.63  1198.6  132.77  1223.6  131.27  1456.7  130.41    2350  131.19
    3180  129.99  4077.6  131.63  4335.5  134.15  4412.1   132.6  4457.1  130.61
    4524  131.23  4531.9  130.21  4645.5  128.96  4723.5  129.74  4749.5  132.26
  4868.1  131.99  4891.9  128.24  4965.7   127.1  4971.9  126.56  4980.1  122.19
  4999.6  116.95  5026.2  122.16  5035.8  122.21  5047.4  128.91  5105.6  126.14
  5414.3   126.2  5521.5  127.09  5603.3  131.17    5659  133.69  5724.2   134.3
#Mann= 7 ,-1 , 0
  1155.2     .05       0  4412.1     .06       0  4457.1     .11       0
  4965.7    .045       0  5047.4     .11       0  5414.3      .1       0
  5603.3     .05       0
#XS Ineff= 2 ,-1
  1155.2    2258     135 4295.17 4772.26  132.39
Permanent Ineff=
       F       F
Bank Sta=4965.7,5047.4
XS Rating Curve= 0 ,0
Exp/Cntr=0.3,0.1

Type RM Length L Ch R = 1 ,3397    ,161,208,250
BEGIN DESCRIPTION:
3397
END DESCRIPTION:
XS GIS Cut Line= 6
        1965184.       311702.39      1967995.41       310215.56
      1967994.35       310104.63        1968003.       310037.82
      1968567.23       309334.69      1968589.36       309309.12
#Sta/Elev= 30
  1204.7  132.63  1273.2  131.26  1506.1  130.41  2399.3  131.19  3229.6     130
  4127.1  131.62  4385.1  134.16  4464.8  132.58  4506.3  130.46  4554.4  132.07
    4947  127.97  4967.5  127.41  4971.9  126.51  4980.1  122.14  4999.6   116.9
  5026.2  122.11  5035.8  122.16  5037.8   126.6  5053.5  127.73  5103.9   126.2
  5171.2  126.99  5222.7  130.65  5236.2  133.33    5247  134.64    5286  134.74
  5305.8  134.07    5353   129.4  5405.9  128.23  5434.1  131.07  5498.7  131.49
#Mann= 9 ,-1 , 0
  1204.7     .05       0  4464.8     .06       0  4506.3     .11       0
    4947     .11       0  4967.5    .045       0  5053.5     .11       0
  5236.2     .05       0    5353     .08       0  5405.9     .05       0
#XS Ineff= 3 ,-1
  1204.7 2307.99  134.03  4288.8 4555.98  132.12 5252.58  5498.7  134.92
Permanent Ineff=
       F       F       F
Bank Sta=4967.5,5053.5
XS Rating Curve= 0 ,0
Exp/Cntr=0.5,0.3

Type RM Length L Ch R = 1 ,3189    ,181,196,199
BEGIN DESCRIPTION:
3189
END DESCRIPTION:
XS GIS Cut Line= 6
      1965184.16        311702.7      1967995.68       310215.72
      1968009.81       310113.39      1968416.22        309847.5
      1968710.16       309758.49      1968875.17       309678.88
#Sta/Elev= 30
  1300.4  132.63  1601.8  130.41  3325.4  130.01  4222.8  131.62  4519.4  134.32
  4568.9     132  4618.3  132.36  4742.6  133.64  4861.1  129.78  4935.8  127.45
  4967.5  128.35  4999.6  117.84  5026.2  123.05  5035.8   123.1  5047.4   129.8
  5100.3  127.64  5112.4  132.86    5164   137.2  5179.1  142.59  5193.2  144.41
  5250.6     147  5293.5  140.79  5322.5  137.78  5367.2  138.69  5382.3  138.06
  5389.6  135.88  5403.7  138.39  5445.5  133.78  5503.8  131.48    5561  131.27
#Mann= 9 ,-1 , 0
  1300.4     .05       0  4568.9     .06       0  4618.3     .11       0
  4861.1     .11       0  4967.5    .045       0  5047.4     .11       0
  5193.2     .05       0  5293.5     .08       0  5367.2     .05       0
#XS Ineff= 5 ,-1
 1241.73    2404     136 4492.37    4715   133.8    4715 4886.77   130.5
  5152.9    5561  148.11    2404    4008   130.5
Permanent Ineff=
       F       F       F       F       F
Bank Sta=4967.5,5047.4
XS Rating Curve= 0 ,0
Exp/Cntr=0.5,0.3

Type RM Length L Ch R = 3 ,3068    ,,,
BEGIN DESCRIPTION:
3117
Structure ID: R_BAS_02
Detailed Survey Structure
END DESCRIPTION:
Bridge Culvert--1,0,-1,-1, 0
Deck Dist Width WeirC Skew NumUp NumDn MinLoCord MaxHiCord MaxSubmerge Is_Ogee
67,108,3,0, 58, 58, , , 0.95, 0, 1,1,,
  1339.7  1397.5  1478.8  1558.9  1575.6  1759.9    1939  2263.1  2537.4  2626.1
  2850.3  3062.7  3252.3    3422  3547.1  3744.6  3872.8  3988.3  4214.9  4340.7
  4447.8  4497.9  4590.8  4648.5  4690.5  4709.7  4775.1  4795.2  4832.6  4871.7
  4908.5  4946.7  4954.8  4954.8  4956.1  4956.1  4977.6  4997.8  5000.5  5040.3
  5063.5  5085.9  5085.9  5086.8  5086.8  5094.9  5126.3  5162.8  5200.6  5237.7
  5276.3  5336.7  5343.5  5362.6  5375.6  5531.4  5554.7  5557.6
  132.63  131.79  131.57  131.39  131.31  131.13  131.04  131.14  131.15  131.12
  130.88  130.59  130.56  130.72  130.84  131.06  131.37  131.54  131.97  132.69
  133.44  133.98  135.79  136.87  138.48  138.88  140.44  140.96  141.76  142.47
  143.14  143.74   143.9  146.46  146.49  146.49  146.97  147.42  147.48  148.32
  148.81  149.25  149.25  149.27  146.66  146.81  147.59   148.3   149.1  149.82
  150.67  151.47  151.59  148.85  146.97  132.09  131.22  131.18
   94.99   94.99   94.99   94.99   94.99   94.99   94.99   94.99   94.99   94.99
   94.99   94.99   94.99   94.99   94.99   94.99   94.99   94.99   94.99   94.99
   94.99   94.99   94.99   94.99   94.99   94.99   94.99   94.99   94.99   94.99
   94.99   94.99   94.99   94.99   94.99  140.99  140.99  140.99  140.99  140.99
  140.99  140.99   94.99   94.99   94.99   94.99   94.99   94.99   94.99   94.99
   94.99   94.99   94.99   94.99   94.99   94.99   94.99   94.99
  1339.7  1397.5  1478.8  1558.9  1575.6  1759.9    1939  2263.1  2537.4  2626.1
  2850.3  3062.7  3252.3    3422  3547.1  3744.6  3872.8  3988.3  4214.9  4340.7
  4447.8  4497.9  4590.8  4648.5  4690.5  4709.7  4775.1  4795.2  4832.6  4871.7
  4908.5  4946.7  4954.8  4954.8  4956.1  4956.1  4977.6  4997.8  5000.5  5040.3
  5063.5  5085.9  5085.9  5086.8  5086.8  5094.9  5126.3  5162.8  5200.6  5237.7
  5276.3  5336.7  5343.5  5362.6  5375.6  5531.4  5554.7  5557.6
  132.63  131.79  131.57  131.39  131.31  131.13  131.04  131.14  131.15  131.12
  130.88  130.59  130.56  130.72  130.84  131.06  131.37  131.54  131.97  132.69
  133.44  133.98  135.79  136.87  138.48  138.88  140.44  140.96  141.76  142.47
  143.14  143.74   143.9  146.46  146.49  146.49  146.97  147.42  147.48  148.32
  148.81  149.25  149.25  149.27  146.66  146.81  147.59   148.3   149.1  149.82
  150.67  151.47  151.59  148.85  146.97  132.09  131.22  131.18
   94.99   94.99   94.99   94.99   94.99   94.99   94.99   94.99   94.99   94.99
   94.99   94.99   94.99   94.99   94.99   94.99   94.99   94.99   94.99   94.99
   94.99   94.99   94.99   94.99   94.99   94.99   94.99   94.99   94.99   94.99
   94.99   94.99   94.99   94.99   94.99  140.99  140.99  140.99  140.99  140.99
  140.99  140.99   94.99   94.99   94.99   94.99   94.99   94.99   94.99   94.99
   94.99   94.99   94.99   94.99   94.99   94.99   94.99   94.99
Pier Skew, UpSta & Num, DnSta & Num=  ,4997.5, 2 ,4997.5, 2 , 0 , 0 , 0 ,0,0
     1.3     1.3
     115  140.99
     1.3     1.3
  118.66  140.99
Pier Skew, UpSta & Num, DnSta & Num=  ,5044, 2 ,5044, 2 , 0 , 0 , 0 ,0,0
     1.3     1.3
  121.46  140.99
     1.3     1.3
  125.12  140.99
Abutment Skew #Up #Dn= , 2 , 2
  4956.1  4970.9
  140.99   136.4
  4956.1  4970.9
  140.99  140.06
Abutment Skew #Up #Dn= , 2 , 2
  5052.3  5085.9
  122.35  140.99
  5052.3  5085.9
  126.01  140.99
BR Coef= 1 , 1 , 0 ,1.25, 0 ,,,0.8,0,2,0,
WSPro=,,,, 1 ,,,, 0 ,,,, 0 ,,,,-1 ,-1 ,-1 , 0 , 0 , 0 , 0 , 0
BC Design=,, 0 ,, 0 ,,,,,,
BC HTab HWMax=147.12
BC Use User HTab Curves=0
BC User HTab FreeFlow(D)= 0

Type RM Length L Ch R = 1 ,2993    ,85,121,167
BEGIN DESCRIPTION:
2993
END DESCRIPTION:
XS GIS Cut Line= 6
      1965184.39       311703.16      1967995.57       310216.38
       1968133.5       310211.74      1968624.43       309975.39
      1968764.11       309892.14      1968959.88       309791.65
#Sta/Elev= 30
  1325.3  132.63  1626.7  130.42  3754.2  130.56  4247.9  131.61  4647.4  134.46
  4664.8  136.38  4784.5  138.57  4788.7  135.67  4834.8  132.78  4969.6  133.09
 4977.38  129.41  4992.2  122.31  4995.5  122.23  4997.5  118.65  5010.4  123.94
  5051.7  125.63 5056.46  129.42  5060.8  132.64  5095.3  133.49  5145.3  134.75
  5185.3  145.93  5212.5  146.75  5249.6  142.31  5257.7  148.77  5277.1   147.4
    5292  149.45    5351  150.24  5494.2   135.2  5513.2  130.46    5571  131.08
#Mann= 3 ,-1 , 0
  1325.3     .05       0  4969.6    .045       0  5095.3     .05       0
#XS Ineff= 2 , 0
       0    2430     140  5106.9       0  147.11
Permanent Ineff=
       F       F
Bank Sta=4977.38,5056.46
XS Rating Curve= 0 ,0
Exp/Cntr=0.5,0.3