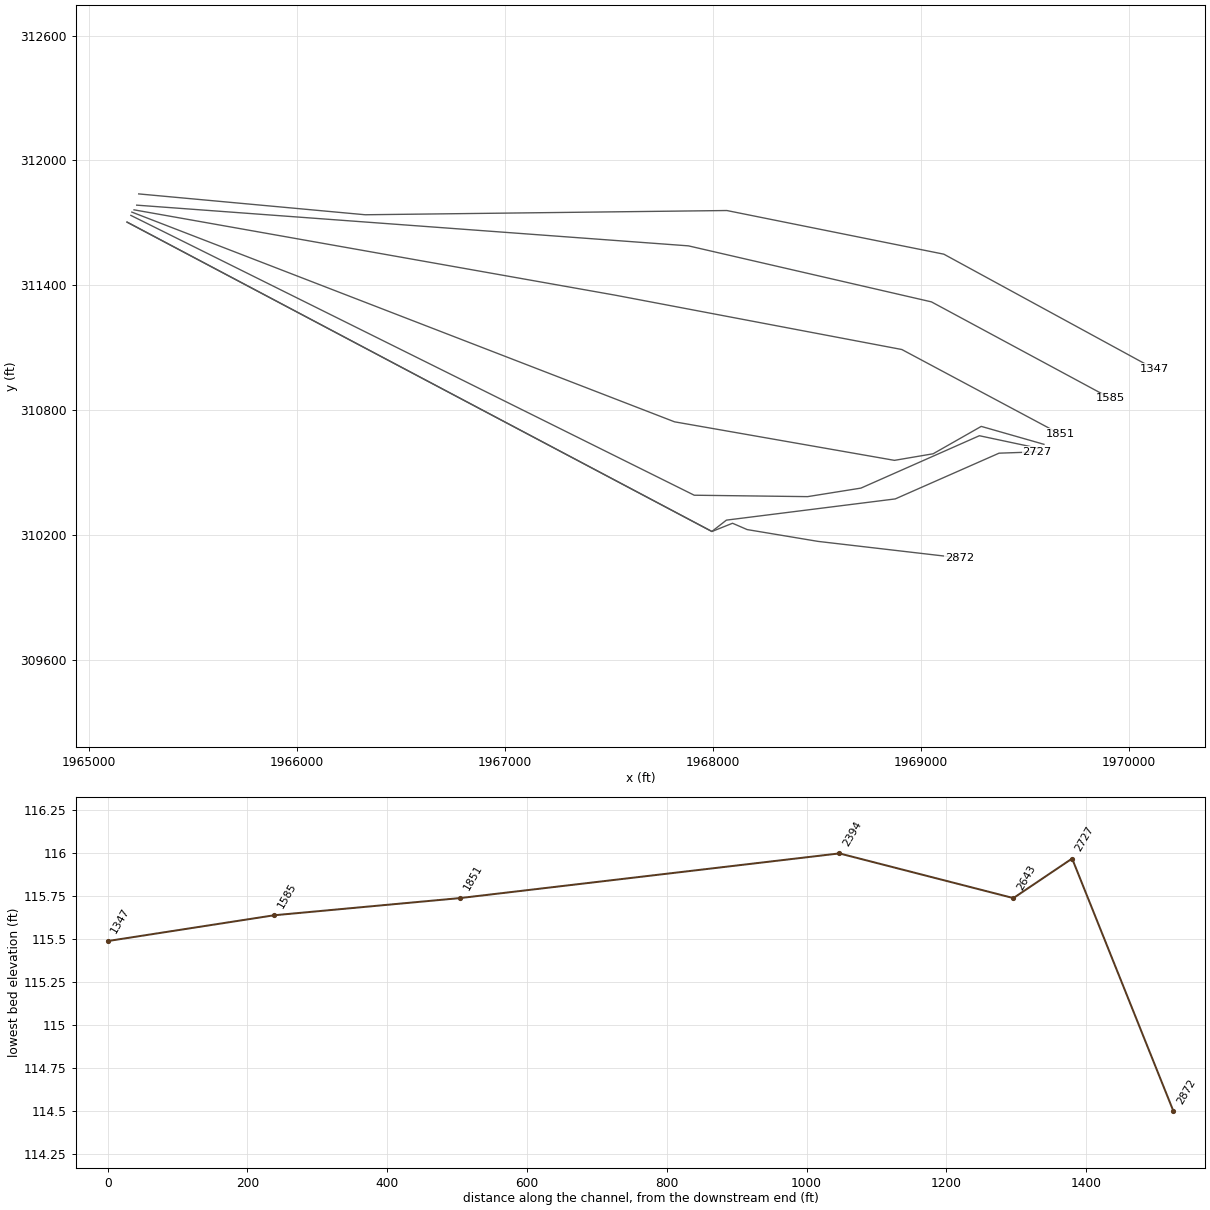
HEC-RAS study BackSwamp.prj: Back Swamp Detailed Study

--- BackSwamp.g01 (geometry) --- (continued)

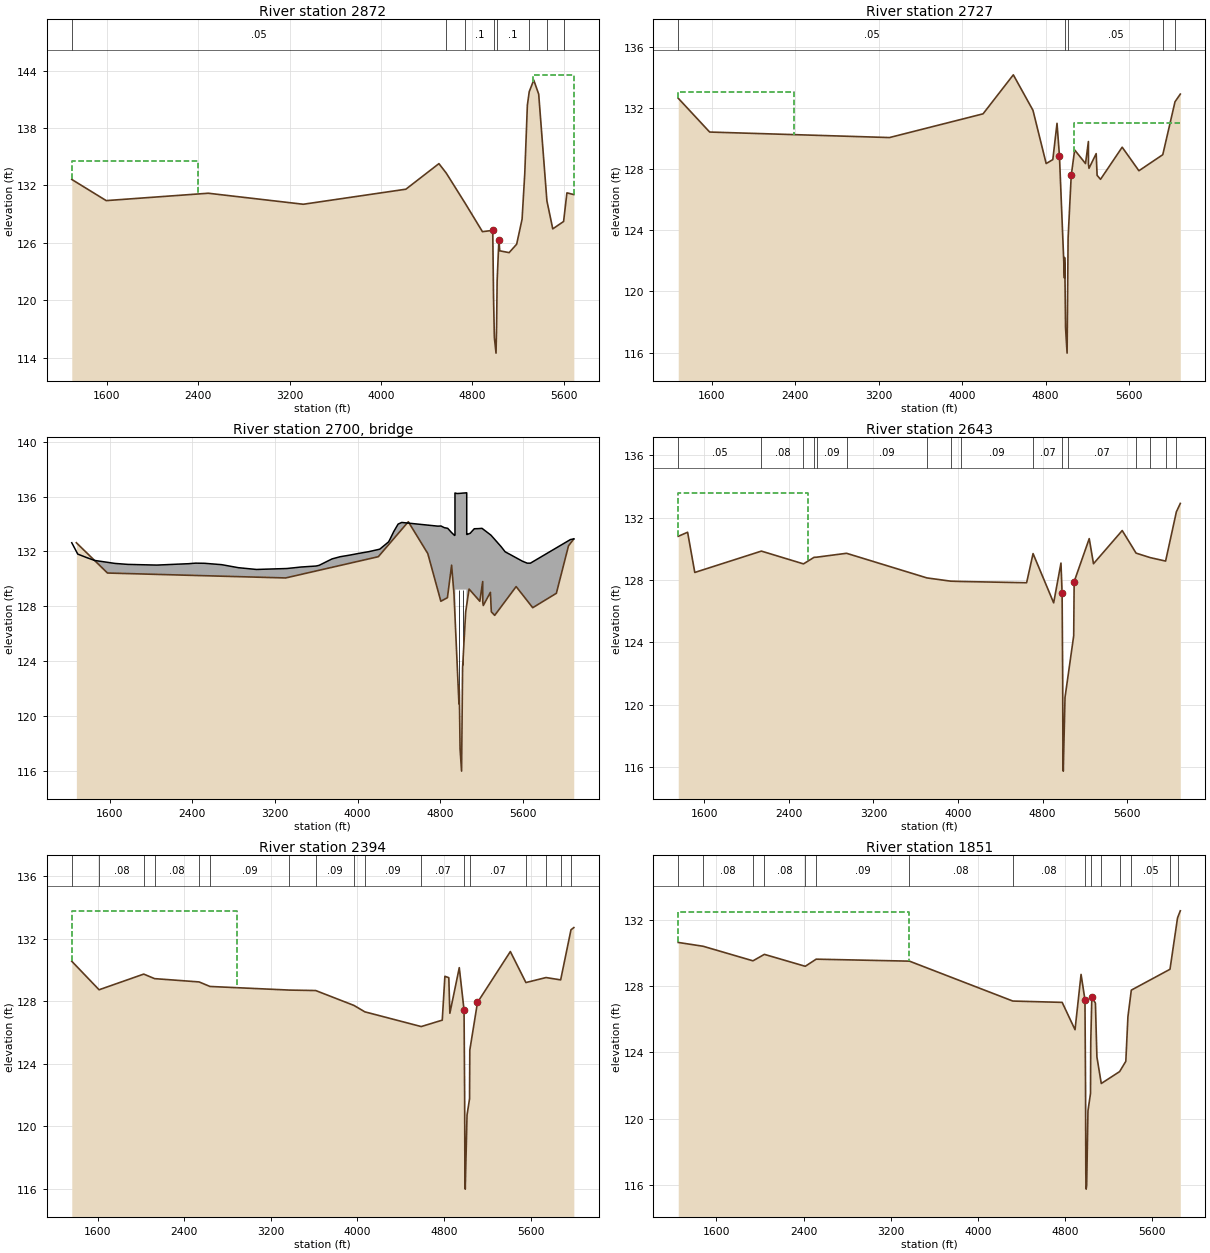
Type RM Length L Ch R = 1 ,2872    ,115,145,228
BEGIN DESCRIPTION:
2872
END DESCRIPTION:
XS GIS Cut Line= 6
      1965184.58       311703.42      1967995.68        310216.6
      1968094.83       310256.31      1968165.07       310225.93
      1968505.94       310169.12      1969184.29       310090.27
#Sta/Elev= 30
  1294.7  132.63    1596  130.42  2488.7  131.19    3320  130.04  4217.3  131.61
  4506.4  134.28  4570.7  133.29  4737.2  130.12    4887  127.18  4977.2  127.31
  4984.2  120.29  4991.4  116.13  5005.9   114.5    5011  117.45  5015.6  122.03
  5031.1  126.35  5038.4  125.18  5120.4  124.99  5186.4  125.87  5233.8  128.48
  5257.3  133.25  5280.1  140.38  5296.4  141.79  5335.9     143  5379.2  141.53
    5451   130.4  5502.2  127.47  5596.9  128.24  5626.1  131.23  5686.6  131.05
#Mann= 8 ,-1 , 0
  1294.7     .05       0  4570.7     .08       0  4737.2      .1       0
  4984.2    .045       0  5015.6      .1       0  5296.4     .05       0
    5451     .09       0  5596.9     .05       0
#XS Ineff= 2 , 0
       0    2400   134.6  5329.9       0  143.55
Permanent Ineff=
       F       F
Bank Sta=4977.2,5031.1
XS Rating Curve= 0 ,0
Exp/Cntr=0.5,0.3

Type RM Length L Ch R = 1 ,2727    ,87,84,123
BEGIN DESCRIPTION:
2727
END DESCRIPTION:
XS GIS Cut Line= 6
      1965184.82       311703.94      1967995.63       310216.89
      1968065.39       310271.33       1968876.9       310373.27
      1969375.87       310593.15      1969556.98       310599.43
#Sta/Elev= 30
  1277.4  132.63  1578.7  130.42  3302.9  130.06  4200.1  131.61  4490.4  134.16
  4678.8  131.84  4805.3  128.36  4869.1  128.62  4909.3  130.99  4932.5  128.88
  4980.6  120.88  4981.5  122.22  4984.2  121.76  4991.4   117.6  5005.9  115.97
  5015.6   123.5  5045.6  127.58  5078.5  129.25  5182.6  128.36  5210.4   129.8
  5210.8   128.3    5216  128.05  5284.8  129.01  5293.8  127.59  5326.5  127.33
  5534.1  129.43  5694.6  127.89  5923.4  128.94  6040.7   132.4  6091.5   132.9
#Mann= 5 ,-1 , 0
  1277.4     .05       0  4984.2    .045       0  5015.6     .05       0
  5923.4     .08       0  6040.7     .05       0
#XS Ineff= 3 ,-1
 1213.74    2383  133.07    2383    4923     129    5076  6091.5     131
Permanent Ineff=
       F       F       F
Bank Sta=4932.5,5045.6
XS Rating Curve= 0 ,0
Exp/Cntr=0.5,0.3

Type RM Length L Ch R = 3 ,2700    ,,,
BEGIN DESCRIPTION:
2700
Structure ID: R_BAS_01
Detailed Survey Structure
END DESCRIPTION:
Bridge Culvert--1,0,-1,-1, 0
Deck Dist Width WeirC Skew NumUp NumDn MinLoCord MaxHiCord MaxSubmerge Is_Ogee
10.5,33,3,0, 59, 59, , , 0.95, 0, 1,1,,
  1233.1  1291.1  1372.5  1453.1  1652.1  1775.9  2056.6  2361.9  2430.8  2518.7
  2684.2  2845.6  3020.2  3315.8  3454.2  3596.8  3626.8  3752.1  3830.7  3918.7
  4009.1  4108.5  4190.5  4213.9    4299  4311.5    4349  4391.6  4426.6  4775.8
  4806.8  4838.8  4871.8  4906.6  4938.1    4942    4942  4945.7  4945.7  4961.4
  4988.9  5016.7  5053.2  5053.2  5055.8  5055.8  5058.9    5089  5128.6  5168.9
  5203.6  5290.6  5387.8  5427.5  5595.4  5641.2  5672.1  6058.9  6092.5
  132.63   131.8  131.56  131.34  131.12  131.05     131   131.1  131.14  131.13
  131.03  130.81  130.68  130.75  130.86  130.93  130.98  131.45  131.61  131.72
  131.85  131.98  132.12  132.16  132.69  132.86  133.44  133.99  134.11  133.84
  133.85  133.73  133.68  133.39  133.16  133.19  136.26  136.25  136.25  136.22
  136.23  136.25  136.27  136.27  136.27  133.24  133.23  133.32  133.65  133.66
  133.68  133.18  132.35  131.97  131.28  131.14  131.14  132.86  132.91
   95.97   95.97   95.97   95.97   95.97   95.97   95.97   95.97   95.97   95.97
   95.97   95.97   95.97   95.97   95.97   95.97   95.97   95.97   95.97   95.97
   95.97   95.97   95.97   95.97   95.97   95.97   95.97   95.97   95.97   95.97
   95.97   95.97   95.97   95.97   95.97   95.97   95.97   95.97  129.21  129.21
  129.21  129.21  129.21   95.97   95.97   95.97   95.97   95.97   95.97   95.97
   95.97   95.97   95.97   95.97   95.97   95.97   95.97   95.97   95.97
  1233.1  1291.1  1372.5  1453.1  1652.1  1775.9  2056.6  2361.9  2430.8  2518.7
  2684.2  2845.6  3020.2  3315.8  3454.2  3596.8  3626.8  3752.1  3830.7  3918.7
  4009.1  4108.5  4190.5  4213.9    4299  4311.5    4349  4391.6  4426.6  4775.8
  4806.8  4838.8  4871.8  4906.6  4938.1    4942    4942  4945.7  4945.7  4961.4
  4988.9  5016.7  5053.2  5053.2  5055.8  5055.8  5058.9    5089  5128.6  5168.9
  5203.6  5290.6  5387.8  5427.5  5595.4  5641.2  5672.1  6058.9  6092.5
  132.63   131.8  131.56  131.34  131.12  131.05     131   131.1  131.14  131.13
  131.03  130.81  130.68  130.75  130.86  130.93  130.98  131.45  131.61  131.72
  131.85  131.98  132.12  132.16  132.69  132.86  133.44  133.99  134.11  133.84
  133.85  133.73  133.68  133.39  133.16  133.19  136.26  136.25  136.25  136.22
  136.23  136.25  136.27  136.27  136.27  133.24  133.23  133.32  133.65  133.66
  133.68  133.18  132.35  131.97  131.28  131.14  131.14  132.86  132.91
   95.97   95.97   95.97   95.97   95.97   95.97   95.97   95.97   95.97   95.97
   95.97   95.97   95.97   95.97   95.97   95.97   95.97   95.97   95.97   95.97
   95.97   95.97   95.97   95.97   95.97   95.97   95.97   95.97   95.97   95.97
   95.97   95.97   95.97   95.97   95.97   95.97   95.97   95.97  129.21  129.21
  129.21  129.21  129.21   95.97   95.97   95.97   95.97   95.97   95.97   95.97
   95.97   95.97   95.97   95.97   95.97   95.97   95.97   95.97   95.97
Pier Skew, UpSta & Num, DnSta & Num=  ,4980.6, 2 ,4980.6, 2 , 0 , 0 , 0 ,0,0
     1.3     1.3
  120.88  129.21
     1.3     1.3
  123.97  129.21
Pier Skew, UpSta & Num, DnSta & Num=  ,5017.3, 2 ,5017.3, 2 , 0 , 0 , 0 ,0,0
     1.3     1.3
  123.49  129.21
     1.3     1.3
  126.58  129.21
Abutment Skew #Up #Dn= , 2 , 2
  4945.7  4964.7
  129.21  124.17
  4945.7  4964.7
  129.21  127.26
Abutment Skew #Up #Dn= , 2 , 2
  5031.4  5053.2
   125.6  129.21
  5031.4  5053.2
  128.69  129.21
BR Coef= 1 , 1 , 0 ,1.25, 0 ,,,0.8,0,2,0,
WSPro=,,,, 1 ,,,, 0 ,,,, 0 ,,,,-1 ,-1 ,-1 , 0 , 0 , 0 , 0 , 0
BC Design=,, 0 ,, 0 ,,,,,,
BC HTab HWMax=134.16
BC Use User HTab Curves=0
BC User HTab FreeFlow(D)= 0

Type RM Length L Ch R = 1 ,2643    ,263,249,117
BEGIN DESCRIPTION:
2643
END DESCRIPTION:
XS GIS Cut Line= 6
      1965203.03       311735.95      1967910.75       310391.05
      1968455.65       310384.26      1968712.19        310425.3
      1969281.27         310677.      1969570.46       310615.57
#Sta/Elev= 30
    1354  130.81  1442.7  131.07  1510.6  128.49  2140.7  129.86  2538.7  129.04
  2638.7  129.46  2664.1  129.47    2946  129.72  3706.3  128.14    3932  127.93
  4032.6  127.91  4649.5  127.83  4710.5   129.7  4905.4  126.54  4974.5  129.09
  4985.2  127.18  4990.7  121.74  4993.1  116.69  4996.3  115.74  5012.8  120.47
    5095  124.43 5099.24   127.9  5241.8  130.66  5282.2  129.05  5553.9  131.18
  5685.1  129.73  5820.1  129.44  5964.3  129.22  6066.2  132.38  6103.4  132.92
#Mann= 16 ,-1 , 0
    1354     .05       0  2140.7     .08       0  2538.7     .05       0
  2638.7     .07       0  2664.1     .09       0    2946     .09       0
  3706.3     .09       0    3932     .05       0  4032.6     .09       0
  4710.5     .07       0  4985.2    .045       0  5038.5     .07       0
  5685.1     .07       0  5820.1     .05       0  5964.3     .08       0
  6066.2     .05       0
#XS Ineff= 2 , 0
         2577.32   133.6
Permanent Ineff=
       F       F
Bank Sta=4985.2,5099.24
XS Rating Curve= 0 ,0
Exp/Cntr=0.5,0.3

Type RM Length L Ch R = 1 ,2394    ,525,543,494
BEGIN DESCRIPTION:
2000
END DESCRIPTION:
XS GIS Cut Line= 6
      1965207.68       311751.82      1967816.04       310743.84
      1968873.11       310558.63      1969058.99       310590.27
      1969290.23       310721.84      1969591.51       310635.76
#Sta/Elev= 30
  1361.1  130.55  1613.4  128.73    2026  129.73  2126.4  129.44  2537.2  129.23
  2638.3  128.94  3369.8  128.71  3614.7  128.68  3968.1  127.73  4068.8  127.32
  4589.5  126.38    4784  126.79  4808.2  129.59  4844.4   129.5  4854.2  127.23
  4941.2  130.14  4985.2  127.44  4990.7     122  4993.1  116.95  4996.3     116
  5012.8  120.73  5036.1  121.77  5038.5  124.88 5109.41  127.92  5413.1  131.17
  5556.7  129.19  5742.8  129.51  5877.7  129.36  5973.2  132.56  5999.6   132.7
#Mann= 17 ,-1 , 0
  1361.1     .07       0  1613.4     .08       0    2026     .05       0
  2126.4     .08       0  2537.2     .05       0  2638.3     .09       0
  3369.8     .09       0  3614.7     .09       0  3968.1     .05       0
  4068.8     .09       0  4589.5     .07       0  4985.2    .045       0
  5038.5     .07       0  5556.7     .07       0  5742.8     .05       0
  5877.7     .08       0  5973.2     .05       0
#XS Ineff= 2 , 0
         2887.89  133.77
Permanent Ineff=
       F       F
Bank Sta=4985.2,5109.41
XS Rating Curve= 0 ,0
Exp/Cntr=0.3,0.1

Type RM Length L Ch R = 1 ,1851    ,279,266,273
BEGIN DESCRIPTION:
1851
END DESCRIPTION:
XS GIS Cut Line= 5
      1965218.23       311762.71      1966155.43       311596.49
      1967529.01       311352.88       1968908.6       311091.35
      1969668.19       310685.74
#Sta/Elev= 30
    1249  130.64  1477.3  130.41  1935.5  129.53  2040.5  129.92  2415.8   129.2
  2516.3  129.63  3373.1  129.51  4322.7   127.1  4775.9  127.02    4894  125.37
  4949.4  128.71  4985.2  127.18  4990.7  121.74  4993.1  116.69  4996.3  115.74
    5001  115.97  5012.8  120.47  5036.1  121.51  5038.5  124.62  5048.3  127.35
  5081.3  126.97  5094.9  123.73    5135  122.12  5303.7  122.84  5360.5  123.46
  5379.9  126.15    5411  127.76  5766.3  129.02  5835.5  132.12  5861.1  132.55
#Mann= 15 ,-1 , 0
    1249     .07       0  1477.3     .08       0  1935.5     .05       0
  2040.5     .08       0  2415.8     .05       0  2516.3     .09       0
  3373.1     .08       0  4322.7     .08       0  4985.2    .045       0
  5038.5     .08       0    5135     .07       0  5303.7     .07       0
    5411     .05       0  5766.3     .08       0  5835.5     .05       0
#XS Ineff= 2 , 0
         3371.13  132.47
Permanent Ineff=
       F       F
Bank Sta=4985.2,5048.3
XS Rating Curve= 0 ,0
Exp/Cntr=0.3,0.1

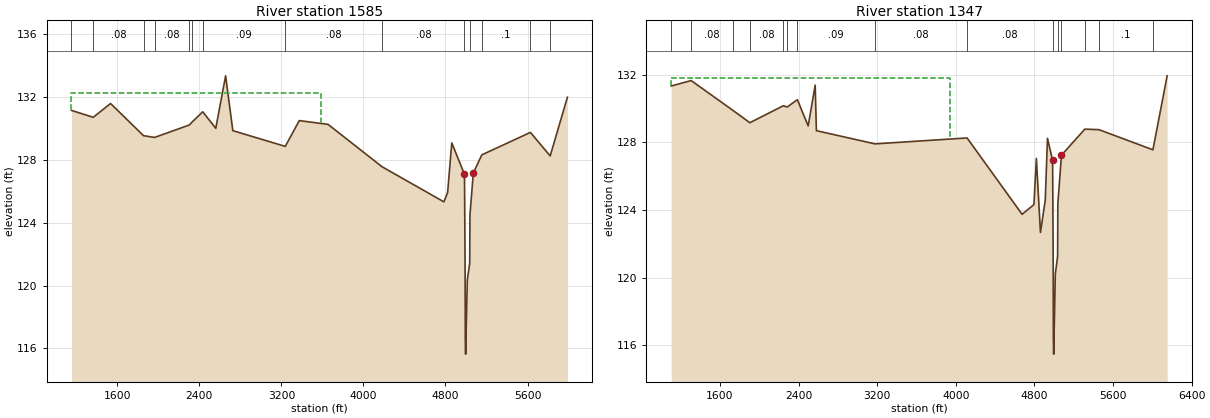
Type RM Length L Ch R = 1 ,1585    ,222,238,230
BEGIN DESCRIPTION:
1577
END DESCRIPTION:
XS GIS Cut Line= 5
       1965231.1       311785.21      1966313.52       311705.34
      1967882.87       311589.56       1969050.8       311320.36
      1969911.31       310856.72
#Sta/Elev= 30
  1153.6  131.15  1366.1  130.71  1534.7  131.59  1856.1  129.54  1964.4  129.43
    2302  130.22  2331.3  130.42  2433.3  131.06  2560.5  130.01  2656.4  133.35
  2726.7  129.86  3237.9  128.86  3374.6   130.5  3654.9  130.26  4182.3  127.56
  4784.5  125.33  4820.8  125.93  4861.4  129.08  4985.2  127.08  4990.7  121.64
  4993.1  116.59  4996.3  115.64  5012.8  120.37  5036.1  121.41  5038.5  124.52
 5071.25  127.16  5153.9  128.32    5628  129.75  5820.6  128.25  5988.6  131.99
#Mann= 14 ,-1 , 0
  1153.6     .07       0  1366.1     .08       0  1856.1     .05       0
  1964.4     .08       0    2302     .07       0  2331.3     .05       0
  2433.3     .09       0  3237.9     .08       0  4182.3     .08       0
  4985.2    .045       0  5038.5     .08       0  5153.9      .1       0
    5628     .07       0  5820.6     .05       0
#XS Ineff= 2 , 0
         3583.76  132.27
Permanent Ineff=
       F       F
Bank Sta=4985.2,5071.25
XS Rating Curve= 0 ,0
Exp/Cntr=0.3,0.1

Type RM Length L Ch R = 1 ,1347    ,0,0,0
BEGIN DESCRIPTION:
1347
END DESCRIPTION:
XS GIS Cut Line= 5
      1965240.72       311839.24      1966329.07       311739.04
      1968067.48        311759.4       1969110.5       311549.55
      1970120.85       310999.03
#Sta/Elev= 30
  1104.6  131.33  1307.7  131.65  1732.6  129.89  1904.7  129.16  2244.8  130.16
  2285.5  130.09  2388.2  130.52  2498.3  128.97  2569.6  131.38  2581.9  128.69
  3178.3  127.91  4115.2  128.26  4674.6  123.75    4795  124.32    4820  127.05
  4861.5  122.68  4910.5  124.58  4932.9  128.24  4985.2  126.93  4990.7  121.49
  4993.1  116.44  4996.3  115.49  5012.8  120.22  5036.1  121.26  5038.5  124.37
  5075.2  127.24  5312.9  128.78  5456.7  128.75  6005.8  127.56  6150.6  131.93
#Mann= 15 ,-1 , 0
  1104.6     .07       0  1307.7     .08       0  1732.6     .05       0
  1904.7     .08       0  2244.8     .07       0  2285.5     .05       0
  2388.2     .09       0  3178.3     .08       0  4115.2     .08       0
  4985.2    .045       0  5038.5     .08       0  5075.2      .1       0
  5312.9     .05       0  5456.7      .1       0  6005.8     .05       0
#XS Ineff= 2 , 0
         3938.14  131.78
Permanent Ineff=
       F       F
Bank Sta=4985.2,5075.2
XS Rating Curve= 0 ,0
Exp/Cntr=0.3,0.1

Chan Stop Cuts=-1
Use User Specified Reach Order=0